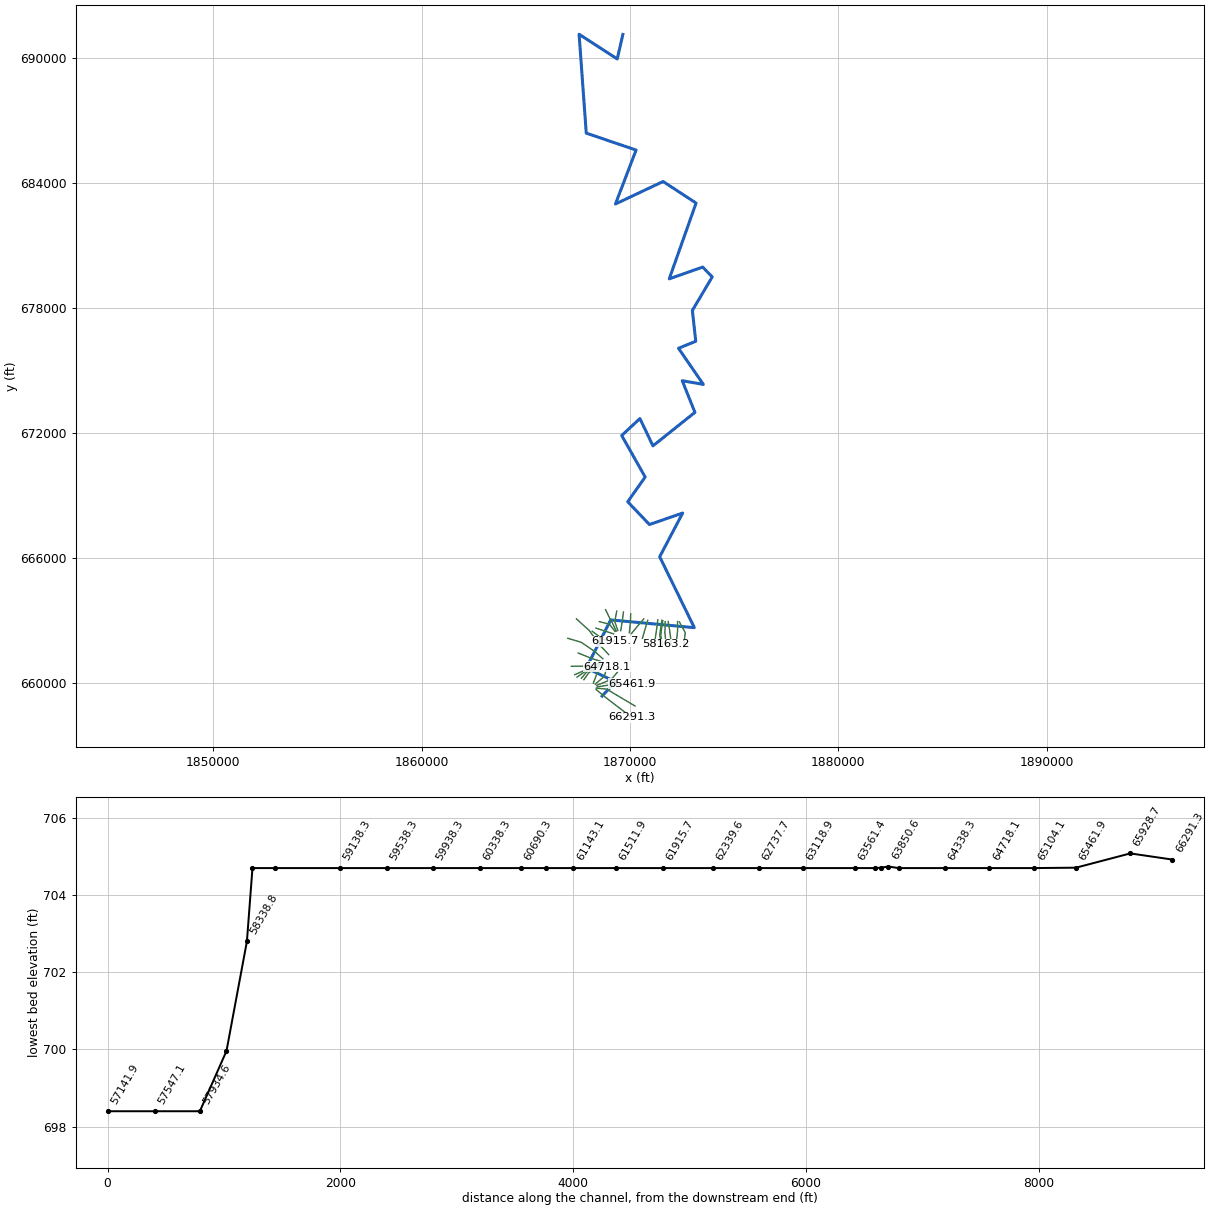
--- SpringCrk2.prj (project) ---

Proj Title=SpringCrk2
Current Plan=p01
Default Exp/Contr=0,0
English Units
Geom File=g01
Flow File=f01
Plan File=p01
BEGIN DESCRIPTION:
AMEC Environment & Infrastructure, 2013
Projection: NAD 1983 State Plane West Virginia South FIPS 4702 (US Feet)
Vertical Datum: NAVD 1988
END DESCRIPTION:
DSS Export Rating Curves= 0
DSS Export Rating Curve Sorted= 0
DSS Export Volume Flow Curves= 0
DXF OffsetX= 0
DXF OffsetY= 0
DXF ScaleX= 0
DXF ScaleY= 0

--- SpringCrk2.p01 (plan) ---

Plan Title=Floodplain
Program Version=4.00
Geom File=g01
Flow File=f01
K Sum by GR=0
Std Step Tol=0.01
Critical Tol=0.01
Num of Std Step Trials=20
Max Error Tol=0.3
Flow Tol Ratio=0.001
Split Flow NTrial=30
Split Flow Tol=0.02
Split Flow Ratio=0.02
Log Output Level=0
Friction Slope Method=1
Unsteady Friction Slope Method=2
Unsteady Bridges Friction Slope Method=1
Global Log Level=0
CheckData=False
Run HTab=0
Run UNet=0
Run PostProcess=0
UNET Theta=0
UNET Theta Warmup=0
UNET ZTol=0
UNET ZSATol=0
UNET MxIter=0
UNET MaxInSteps=0
UNET DtIC=0
UNET DtMin=0
UNET MaxCRTS=0
UNET WFStab=0
UNET SFStab=0
UNET WFX=0
UNET SFX=0
UNET DSS MLevel=0
UNET DZMax Abort=0
UNET Convert EG Bridges=0
UNET Use Existing IB Tables=0
UNET Froude Limit=0
UNET Froude Power=0
Write IC File=0
Echo Input=False
Echo Output=False
Write Detailed=0

--- SpringCrk2.f01 (steady flow) ---

Flow Title=NFF Regression Equation
Program Version=4.10
Number of Profiles= 1
Profile Names=P100yr
River Rch & RM=SpringCrk2,Main            ,66291.3
7096.928
River Rch & RM=SpringCrk2,Main            ,62737.7
7161.471
River Rch & RM=SpringCrk2,Main            ,62339.6
 7328.63
River Rch & RM=SpringCrk2,Main            ,54459.4
7422.252
River Rch & RM=SpringCrk2,Main            ,53943.7
7620.523
River Rch & RM=SpringCrk2,Main            ,52476.2
7634.287
River Rch & RM=SpringCrk2,Main            ,51940.7
7667.061
River Rch & RM=SpringCrk2,Main            ,46963.5
7733.457
River Rch & RM=SpringCrk2,Main            ,46745.1
 7821.56
River Rch & RM=SpringCrk2,Main            ,37232.7
7897.737
River Rch & RM=SpringCrk2,Main            ,36397.5
8194.884
River Rch & RM=SpringCrk2,Main            ,19938.3
8411.332
River Rch & RM=SpringCrk2,Main            ,19558.7
9476.099
River Rch & RM=SpringCrk2,Main            ,9541.8
9718.641
River Rch & RM=SpringCrk2,Main            ,8733.5
9955.497
River Rch & RM=SpringCrk2,Main            ,85.6
 10209.9
Boundary for River Rch & Prof#=SpringCrk2,Main            , 1
Up Type= 0
Dn Type= 3
Dn Slope=0.0003
DSS Import GetInterval= 0
DSS Import GetPeak= 0
DSS Import FillOption= 0

--- SpringCrk2.g01 (geometry) ---

Geom Title=USGS 3m DEM
Program Version=4.10

River Reach=SpringCrk2      ,Main
Reach XY= 30
      1868660.82      659362.514     1869304.652      660044.947
     1867899.577      660711.789     1869073.507      663014.799
     1873087.591      662644.797     1871424.179      666046.895
     1872527.666       668145.39     1870932.197      667594.115
     1869890.008      668687.341     1870726.544       669873.38
     1869601.008      671867.134     1870474.775      672679.846
     1871101.458       671369.05     1873114.441      672977.122
     1872506.489      674496.768     1873519.039      674319.671
     1872327.517       676052.91     1873155.942       676389.89
     1872992.605      677869.617     1873946.011      679477.927
     1873487.475      679950.307      1871882.72      679385.765
     1873171.212      683022.659     1871587.207      684057.695
     1869301.583        682978.2     1870291.478      685566.888
     1867899.877      686379.565      1867555.71       691124.45
     1869386.358      689940.068     1869657.227      691117.628

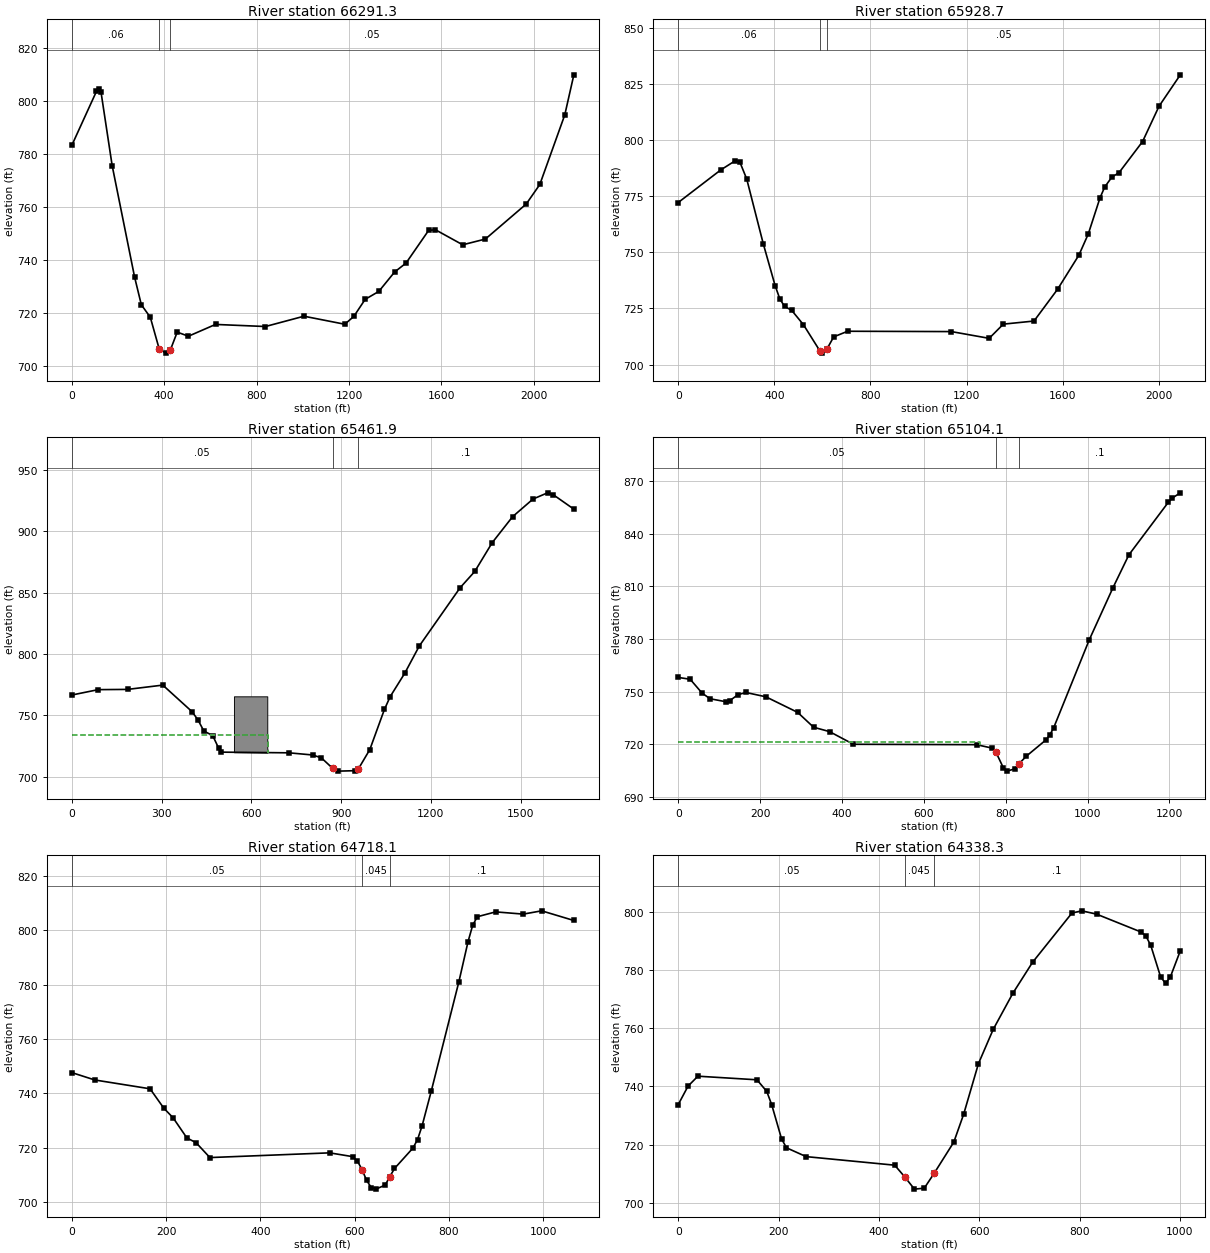
Type RM Length L Ch R = 1 ,66291.3 ,359.7,362.6,365.6
XS GIS Cut Line= 4
     1868371.678      659673.079     1868672.544      659427.254
     1868798.226      659320.478     1870084.002      658335.095
#Sta/Elev= 30
       0  783.29   106.8  803.69   116.6  804.78   126.3   803.6   174.8   775.7
     272   733.6   301.1  723.18     340  718.45   378.8  706.38   407.9  704.92
   427.3  706.21   456.4  712.85   504.9   711.3   622.2  715.75   838.2  714.96
  1005.1  718.85  1181.8  715.82    1221  718.78  1270.1  725.22    1329   728.2
  1397.8  735.56  1446.9  738.89    1545  751.26  1574.5  751.46  1692.3   745.8
  1790.5  747.97  1967.2  761.18  2026.1  768.56  2134.1  794.81  2173.4  809.94
#Mann= 3 , 0 , 0
       0     .06       0   378.8    .045       0   427.3     .05       0
Bank Sta=378.8,427.3
XS Rating Curve= 0 ,0
Exp/Cntr=0.3,0.1

Type RM Length L Ch R = 1 ,65928.7 ,451.9,466.8,480.3
XS GIS Cut Line= 4
     1868378.106       659741.95     1868896.936      659693.602
     1869074.887      659576.415     1870240.252      658884.314
#Sta/Elev= 30
       0  772.21     177  786.74     236  790.74   255.6  790.46   285.1  782.66
   353.9  753.82   403.1   735.2   422.8  729.25   442.4  725.91   471.9  724.18
   521.1  717.75   588.9  706.18   598.6  705.08   617.9  706.73     647  712.33
   705.1  714.83  1136.8  714.68    1294  711.67  1352.9     718  1480.6  719.38
  1578.8  733.56  1667.2  748.71  1706.5  758.19  1755.6  774.39  1775.2  779.17
  1804.7  783.54  1834.2  785.48  1932.4  799.37  2001.1  815.15  2089.5  829.12
#Mann= 3 , 0 , 0
       0     .06       0   588.9    .045       0   617.9     .05       0
Bank Sta=588.9,617.9
XS Rating Curve= 0 ,0
Exp/Cntr=0.3,0.1

Type RM Length L Ch R = 1 ,65461.9 ,342.2,357.8,374.9
XS GIS Cut Line= 4
     1868427.524       659802.02     1869261.085      659931.189
     1869393.898      659933.793     1870094.419      659959.835
#Sta/Elev= 30
       0  766.61    88.3  770.99   186.4  771.19   304.1  774.68   402.1  753.02
   421.8  746.28   441.4  737.29   470.8  733.64   490.4  723.54   500.2  720.16
   725.8   719.6   804.3  717.85   833.7  715.55     872  706.89     891  704.71
   947.9  705.08   957.4  706.46   995.8  722.27  1044.5  754.88    1064   765.4
  1112.6  784.39  1161.3   806.6  1297.6  853.94  1346.3   867.1  1404.7  890.56
  1472.9  911.71    1541  926.04  1589.7  931.09  1609.2  929.45  1677.4  917.81
#Mann= 3 , 0 , 0
       0     .05       0     872    .045       0   957.4      .1       0
#XS Ineff= 2 , 0
          656.19  734.31
Permanent Ineff=
       F       F
#Block Obstruct= 1 ,-1
  541.81  653.18  765.56
Bank Sta=872,957.4
XS Rating Curve= 0 ,0
Exp/Cntr=0.3,0.1

Type RM Length L Ch R = 1 ,65104.1 ,374.4,386,397.2
XS GIS Cut Line= 4
     1868401.042      659877.026     1869060.565      660139.956
     1869182.092      660257.144     1869407.787      660521.901
#Sta/Elev= 30
       0  758.11    29.2  757.05    58.4  749.13    77.8  745.95   116.7  744.24
   126.4  744.94   145.9  748.25   165.3  749.52     214  747.07   291.8  738.18
   330.7  729.71   369.6  727.23     428     720   728.8  719.78   766.3  717.85
   775.7  715.77   794.4  706.54   803.8   704.7   822.6  706.06   831.9  708.74
   850.7  713.26   898.2  722.45   907.8  725.27   917.5  729.52  1004.5  779.68
  1062.4  809.35  1101.1  827.98  1197.7  858.02  1207.4  860.38  1226.7  863.31
#Mann= 3 , 0 , 0
       0     .05       0   775.7    .045       0   831.9      .1       0
#XS Ineff= 2 , 0
          738.39  721.47
Permanent Ineff=
       F       F
Bank Sta=775.7,831.9
XS Rating Curve= 0 ,0
Exp/Cntr=0.3,0.1

Type RM Length L Ch R = 1 ,64718.1 ,381.2,379.8,370.9
XS GIS Cut Line= 4
      1868330.15        659934.2     1868762.387      660300.546
      1868797.11      660413.394     1868900.118      660779.711
#Sta/Elev= 30
       0  747.62    48.8   744.9   166.1  741.65   195.4  734.48   214.9  730.99
   244.2  723.56   263.8  721.79   293.1  716.32   547.1  718.06   596.1  716.66
     606  715.04   615.8  711.92   625.6  707.88   635.5  705.27   645.3   704.7
     665   706.2   674.8  709.32   684.7   712.3   723.7   719.8   733.5  722.91
   743.2  727.98   762.7   740.8   821.3  781.08   840.8  795.89   850.5  801.82
   860.3  805.01   899.3   806.8   957.9  805.98   996.9  807.19  1065.2  803.63
#Mann= 3 , 0 , 0
       0     .05       0   615.8    .045       0   674.8      .1       0
Bank Sta=615.8,674.8
XS Rating Curve= 0 ,0
Exp/Cntr=0.3,0.1

Type RM Length L Ch R = 1 ,64338.3 ,405.6,400,392.5
XS GIS Cut Line= 3
     1868238.238      659980.356     1868409.188      660429.505
     1868718.559      660847.692
#Sta/Elev= 30
       0  733.74    19.6  740.08    39.2  743.48   156.9  742.24   176.5  738.24
   186.4  733.63     206  721.94   215.8  718.89     255  715.86   431.5  712.92
   451.2  708.96   470.8   704.7   490.4  705.02     510   710.1   549.3  720.85
   568.9   730.4   598.4  747.78   627.8  759.54   667.1  771.98   706.3  782.59
   784.8   799.5   804.5  800.26   833.9  799.12   922.2  793.01   932.1  791.66
   941.9  788.38   961.5   777.6   971.3  775.34   981.1  777.62  1000.8  786.55
#Mann= 3 , 0 , 0
       0     .05       0   451.2    .045       0     510      .1       0
Bank Sta=451.2,510
XS Rating Curve= 0 ,0
Exp/Cntr=0.3,0.1

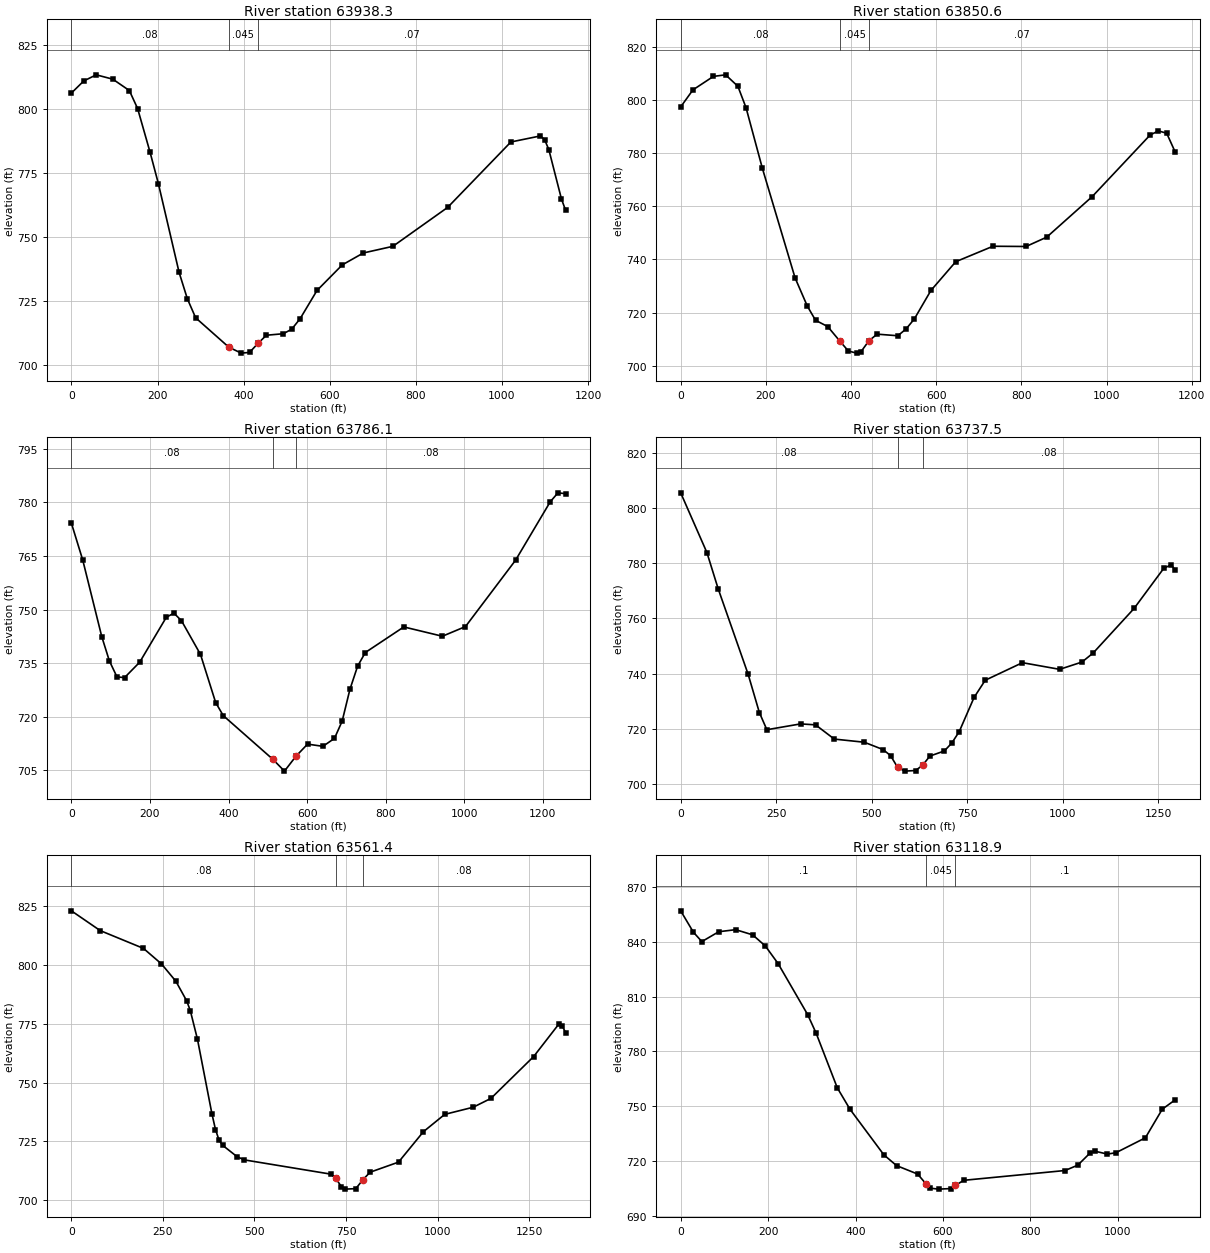
Type RM Length L Ch R = 1 ,63938.3 ,94.2,87.6,90.2
XS GIS Cut Line= 3
     1867785.663      660147.018     1868018.163      660477.368
     1868640.373      660885.236
#Sta/Elev= 30
       0  806.32    28.8  811.06    57.7  813.45    96.2  811.75   134.6  807.31
   153.9  800.24   182.8  783.15     202  770.96   250.1  736.28   269.3  725.95
   288.6  718.51   365.5  707.04   394.4   704.7   413.8  704.98   433.3   708.5
   452.9  711.69   492.1  712.28   511.6  714.04   531.2  718.15   570.4  729.18
   629.1  739.18   678.1  743.84   746.6  746.43   873.8  761.64  1020.7  787.21
  1089.2  789.57    1099  788.11  1108.8  784.23  1138.2  764.88  1147.9  760.46
#Mann= 3 , 0 , 0
       0     .08       0   365.5    .045       0   433.3     .07       0
Bank Sta=365.5,433.3
XS Rating Curve= 0 ,0
Exp/Cntr=0.3,0.1

Type RM Length L Ch R = 1 ,63850.6 ,67.2,64.5,62.1
XS GIS Cut Line= 4
     1867667.769      660214.175     1867886.953      660481.102
     1867978.099      660552.717     1868590.078      660891.258
#Sta/Elev= 30
       0  797.41    28.8  803.81    76.8  808.88   105.5  809.47   134.3  805.16
   153.5  797.07   191.9  774.24   268.6  733.06   297.4  722.42   316.6  717.11
   345.4  714.72   374.4  709.13   393.7  705.55     413  704.74   422.7  705.12
     442  709.38   461.3  711.88   509.9  711.28   529.3  713.84   548.7  717.61
   587.6  728.32   645.9  739.14   733.3  744.96     811  744.87   859.6  748.39
   966.4  763.66  1102.4  786.83  1121.8  788.37  1141.2   787.5  1160.7  780.59
#Mann= 3 , 0 , 0
       0     .08       0   374.4    .045       0     442     .07       0
Bank Sta=374.4,442
XS Rating Curve= 0 ,0
Exp/Cntr=0.3,0.1

Type RM Length L Ch R = 1 ,63786.1 ,51.1,48.7,45.8
XS GIS Cut Line= 4
     1867453.794      660268.862      1867826.19      660528.845
     1867992.856       660631.71     1868539.731      660897.335
#Sta/Elev= 30
       0  774.21      29  763.83    77.3  742.41    96.6  735.63     116  731.12
   135.3  730.91   173.9  735.24   241.6  747.82   260.9  748.99   280.2  746.86
   328.6  737.41   367.2  723.93   386.5  720.27   512.9  708.01   542.3  704.71
   571.7   708.9   601.1  712.28   640.2  711.66   669.6  713.89   689.2  718.74
   708.9  727.62   728.5  734.13   748.1  737.95   846.1  745.12   944.2  742.51
    1003  745.22  1130.5  763.82  1218.8   780.2  1238.4   782.7    1258  782.46
#Mann= 3 , 0 , 0
       0     .08       0   512.9    .045       0   571.7     .08       0
Bank Sta=512.9,571.7
XS Rating Curve= 0 ,0
Exp/Cntr=0.3,0.1

Type RM Length L Ch R = 1 ,63737.5 ,184.7,176,167.9
XS GIS Cut Line= 4
     1867348.759      660387.786     1867852.231       660606.97
     1867971.589      660661.224     1868529.315      660916.432
#Sta/Elev= 30
       0  805.45    68.6  783.83    98.1  770.71   176.5  739.77   205.9  725.91
   225.5  719.69   313.8   721.8     353  721.45     402   716.3   480.5  715.16
   529.5  712.51   549.1  710.34   567.8  706.04   586.6   704.7   614.7  704.92
   633.4  706.86   652.1  710.15     690     712   709.4  714.85   728.9  718.98
   767.8  731.37     797   737.6   894.4  743.96   991.8  741.55  1050.2  744.19
  1079.4  747.45  1186.5  763.58  1264.4  778.15  1283.8  779.39  1293.6  777.56
#Mann= 3 , 0 , 0
       0     .08       0   567.8    .045       0   633.4     .08       0
Bank Sta=567.8,633.4
XS Rating Curve= 0 ,0
Exp/Cntr=0.3,0.1

Type RM Length L Ch R = 1 ,63561.4 ,452.3,442.5,432.1
XS GIS Cut Line= 4
      1867182.96      660789.696     1867832.266       660796.64
     1867988.516      660807.057     1868516.294      660938.133
#Sta/Elev= 30
       0  822.96    78.7  814.56   196.8     807     246  800.41   285.3  793.04
   314.8  784.73   324.7  780.59   344.4  768.32   383.7  736.79   393.5  730.03
   403.4  725.46   413.2   723.3   452.6  718.47   472.2  717.13   708.1  711.08
     722   709.3   737.4  705.71   747.2   704.7   776.6   704.9   796.2   708.7
   815.6  711.88   893.3  716.17   961.3   729.1  1019.6  736.47  1097.3   739.5
  1145.8  743.26  1262.4  761.04  1330.3  774.67    1340  774.12  1349.8   771.2
#Mann= 3 , 0 , 0
       0     .08       0     722    .045       0   796.2     .08       0
Bank Sta=722,796.2
XS Rating Curve= 0 ,0
Exp/Cntr=0.3,0.1

Type RM Length L Ch R = 1 ,63118.9 ,387.9,381.2,374.4
XS GIS Cut Line= 4
     1867511.953      661426.415     1867988.516       661236.31
      1868147.37      661168.602     1868571.849       661035.79
#Sta/Elev= 30
       0  856.87      29   845.2    48.4  840.05    87.1  845.45   125.8  846.56
   164.6  843.74   193.6  837.64   222.7  828.05   290.4  800.12   309.8  789.95
   358.2  760.07   387.2  748.38   464.7  723.45   493.7  717.56   541.9  712.94
     561  707.59   570.6  705.22   589.8   704.7   618.6  705.01   628.2  706.73
   647.4  709.52   879.1  714.88   908.2   717.8   937.2  724.66   946.8  725.48
   975.8  723.86   995.2  724.58  1062.8  732.76  1101.5  748.42  1130.5  753.44
#Mann= 3 , 0 , 0
       0      .1       0     561    .045       0   628.2      .1       0
Bank Sta=561,628.2
XS Rating Curve= 0 ,0
Exp/Cntr=0.3,0.1

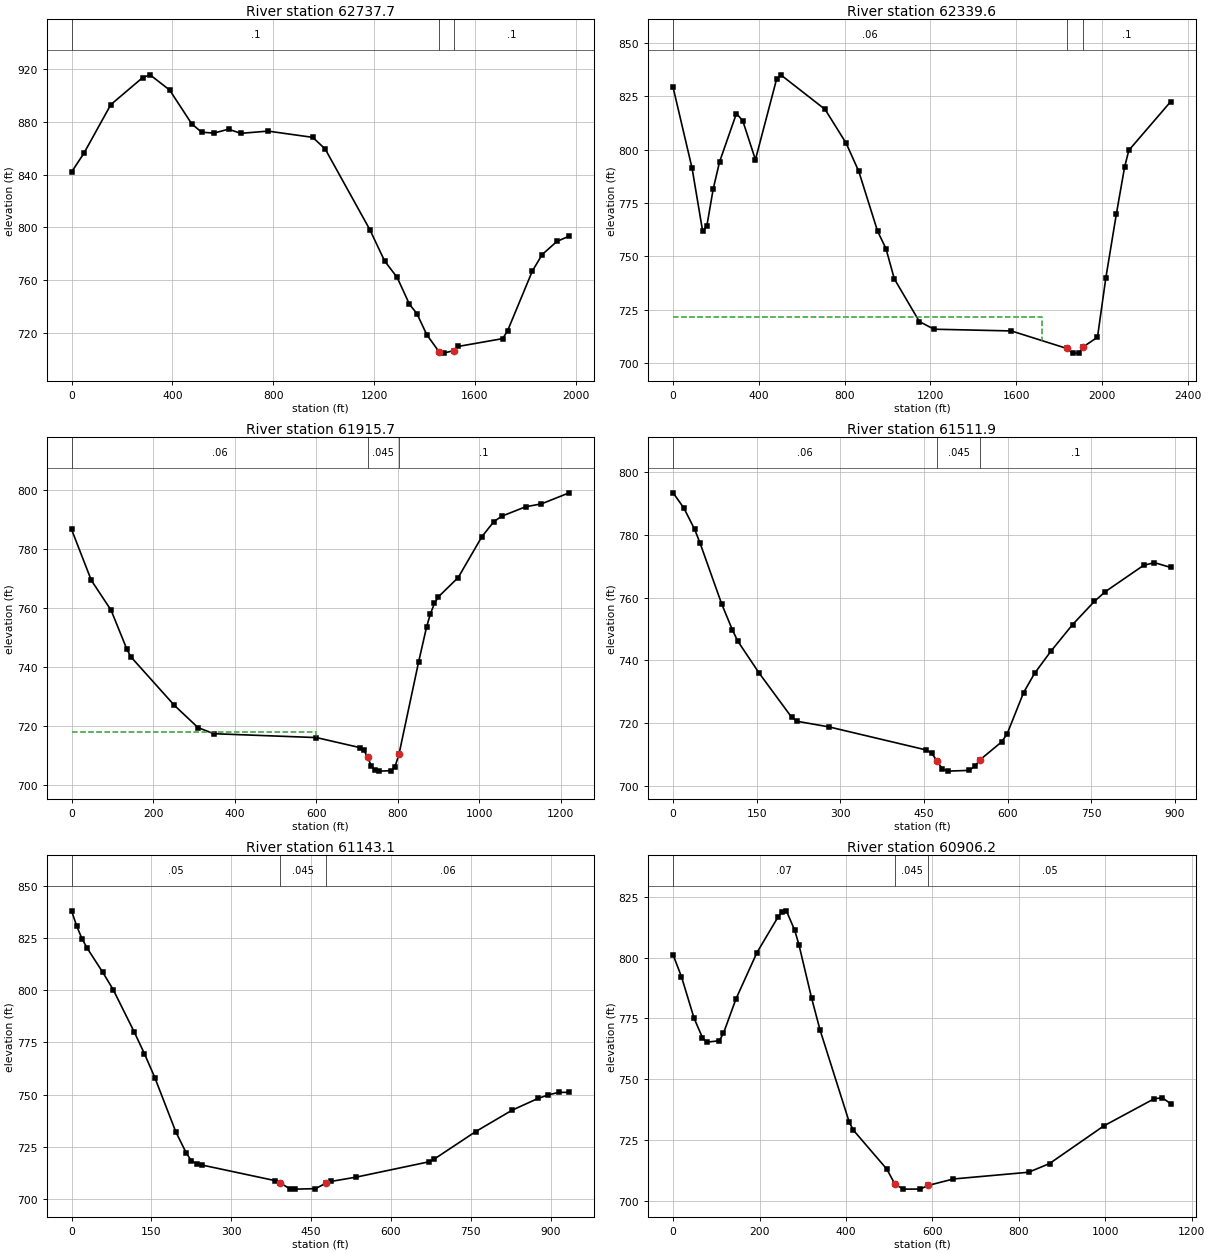
Type RM Length L Ch R = 1 ,62737.7 ,399.9,398.2,396.4
XS GIS Cut Line= 5
     1867017.548      662134.547     1867660.482      661940.939
     1868261.719      661530.153     1868389.558      661426.849
      1868694.93      661153.055
#Sta/Elev= 30
       0  841.97    48.7  856.07   155.7  893.04   282.2  913.56   311.4  915.64
   389.2   904.1   476.8  878.49   515.8  872.16   564.4  871.48   622.8  874.42
   671.4  871.29   779.7  872.98   956.8  868.24    1006  859.47  1183.1  798.37
  1242.2  774.46  1291.4   762.2  1340.6   741.7  1370.1  734.63  1409.3  718.65
  1457.6  705.81  1475.8   704.7  1515.6  706.57    1535   709.8  1710.5   715.7
    1730  721.74  1827.6  766.73  1866.7  779.37  1925.3  789.32  1974.1  793.42
#Mann= 3 , 0 , 0
       0      .1       0  1457.6    .045       0  1515.6      .1       0
Bank Sta=1457.6,1515.6
XS Rating Curve= 0 ,0
Exp/Cntr=0.3,0.1

Type RM Length L Ch R = 1 ,62339.6 ,414,423.8,433.7
XS GIS Cut Line= 5
     1867429.875       663065.97     1868047.541      662501.697
     1868582.849      661758.207     1868704.662      661642.994
     1868977.109       661349.85
#Sta/Elev= 30
       0  829.22    88.6  791.31   137.8  761.84   157.5   764.4     187  781.64
   216.5  794.31   295.3  817.02   324.8  813.62   383.9  795.37   482.3  833.03
     502  835.15   708.7  818.95   807.1  803.07   865.8  789.91   953.6  761.84
   992.6  753.71  1031.5  739.53  1148.5  719.49  1216.7  715.91  1577.3   715.1
  1836.6  706.88  1862.6   704.7  1892.5   704.7  1911.1  707.55    1979  712.14
    2018  739.97  2066.8  769.74  2105.9  792.14  2125.4  799.79  2320.6  822.61
#Mann= 3 , 0 , 0
       0     .06       0  1836.6    .045       0  1911.1      .1       0
#XS Ineff= 2 , 0
         1722.41  721.62
Permanent Ineff=
       F       F
Bank Sta=1836.6,1911.1
XS Rating Curve= 0 ,0
Exp/Cntr=0.3,0.1

Type RM Length L Ch R = 1 ,61915.7 ,403.6,403.8,404
XS GIS Cut Line= 4
     1868183.828      662473.724     1868662.995      662111.744
     1868910.391      662031.015      1869268.05      661994.369
#Sta/Elev= 30
       0  786.53    48.4  769.32    96.9  759.19   135.6     746   145.3  743.42
   251.8  727.02     310  719.45   348.7  717.37   600.5  716.06   706.6  712.68
   716.2  711.93   725.8  709.51   735.5  706.33   745.1  704.93   754.7   704.7
   783.6  704.85   793.3  706.24   802.9  710.39   851.1  741.66   870.5  753.42
   880.2  758.04   889.9  761.46   899.6   763.7   948.2  770.25  1006.5  784.12
  1035.7  789.18  1055.1  791.01  1113.4  794.19  1152.3  795.18  1220.3  798.92
#Mann= 3 , 0 , 0
       0     .06       0   725.8    .045       0   802.9      .1       0
#XS Ineff= 2 , 0
          600.45  718.07
Permanent Ineff=
       F       F
Bank Sta=725.8,802.9
XS Rating Curve= 0 ,0
Exp/Cntr=0.3,0.1

Type RM Length L Ch R = 1 ,61511.9 ,370.4,368.8,367.2
XS GIS Cut Line= 4
      1868366.12      662623.029     1868806.658       662477.63
     1868917.102      662441.996     1869214.644      662345.251
#Sta/Elev= 30
       0  793.39    19.3  788.54    38.7  781.73    48.3  777.39      87  758.05
   106.3  749.74     116  746.13   154.6  735.88   212.6  721.88   222.3  720.59
   280.3  718.77   454.2  711.44   463.9  710.39   473.6  707.97   483.2  705.32
   492.9   704.7   531.6  704.94   541.3  706.28     551  708.36   589.7  714.05
   599.5  716.66   628.8  729.72   648.4  735.82   677.7  742.89   716.8  751.42
     756  758.82   775.5   761.9     844  770.26   863.5  771.15   892.8  769.61
#Mann= 3 , 0 , 0
       0     .06       0   473.6    .045       0     551      .1       0
Bank Sta=473.6,551
XS Rating Curve= 0 ,0
Exp/Cntr=0.3,0.1

Type RM Length L Ch R = 1 ,61143.1 ,252.3,236.9,221.2
XS GIS Cut Line= 4
      1868527.55      662933.669     1868906.485      662835.703
     1869030.183       662785.79     1869281.919      662462.439
#Sta/Elev= 30
       0  837.93     9.8  830.56    19.6  824.57    29.4  820.04    58.7  808.47
    78.3  800.16   117.4   780.1     137  769.49   156.6  757.96   195.7  732.19
   215.3  722.08     225  718.31   234.8   716.9   244.6  716.26   381.6  708.81
   391.4   707.8   410.4  704.77     420   704.7   458.1  704.92   477.1  707.46
   486.7  708.36   534.5  710.44   671.1  717.77   680.9  719.04     759  732.24
   827.2  742.46     876  748.11   895.5  749.81   915.1  751.02   934.6  751.04
#Mann= 3 , 0 , 0
       0     .05       0   391.4    .045       0   477.1     .06       0
Bank Sta=391.4,477.1
XS Rating Curve= 0 ,0
Exp/Cntr=0.3,0.1

Type RM Length L Ch R = 1 ,60906.2 ,230,215.9,202
XS GIS Cut Line= 4
      1868826.19      663510.616     1869004.141      663143.862
     1869130.009      662915.998     1869338.342        662479.8
#Sta/Elev= 30
       0   801.1    19.4  792.08    48.5  775.03    67.9  767.04    77.6  765.16
   106.8  765.76   116.5  768.82   145.6  783.03   194.1  802.07   242.6  816.62
   252.4  818.81   262.1  819.22   281.5  811.16   291.2  805.24   320.3  783.43
   339.7  770.36   407.6  732.22   417.3  728.92   494.4  712.95   513.7  706.61
     533   704.7   571.6  704.72   590.8  706.25   648.7  708.88   822.6  711.65
     871  715.22   996.7  730.73  1112.7  741.85    1132  742.31  1151.4  739.81
#Mann= 3 , 0 , 0
       0     .07       0   513.7    .045       0   590.8     .05       0
Bank Sta=513.7,590.8
XS Rating Curve= 0 ,0
Exp/Cntr=0.3,0.1

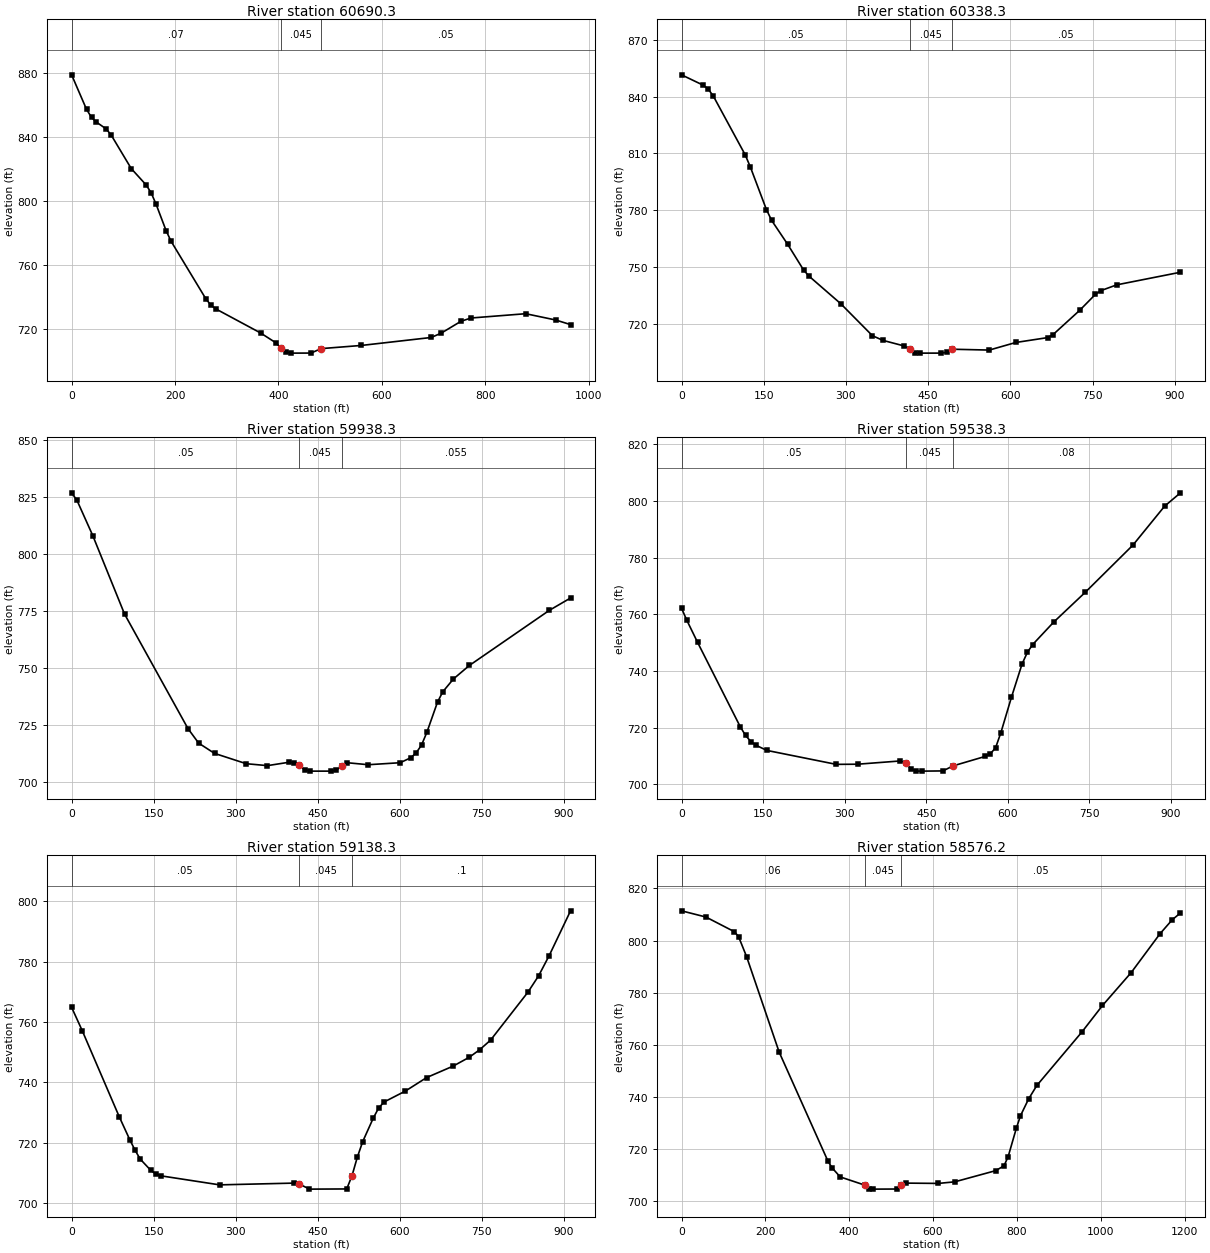
Type RM Length L Ch R = 1 ,60690.3 ,352.1,352,350.9
XS GIS Cut Line= 4
      1869363.57      663438.075      1869291.12      663060.327
     1869273.759      662914.493     1869416.015      662504.967
#Sta/Elev= 30
       0  878.96    28.8  857.38    38.5  852.28    48.1  849.32    67.3  844.99
    76.9  841.05   115.4  820.23   144.2  809.99   153.8   805.1   163.5  797.84
   182.7  781.44   192.3  774.78   259.6  738.72   269.2  734.81   278.9  732.39
   365.4  717.34   394.4   711.3   404.2  708.19     414  705.43   423.8   704.7
     463  704.74   482.5  707.52   560.4  709.51   695.3  714.49   714.5  717.15
   753.1  724.64   772.4  726.69   878.3  729.38   936.1  725.45     965  722.57
#Mann= 3 , 0 , 0
       0     .07       0   404.2    .045       0   482.5     .05       0
Bank Sta=404.2,482.5
XS Rating Curve= 0 ,0
Exp/Cntr=0.3,0.1

Type RM Length L Ch R = 1 ,60338.3 ,398,400,401.2
XS GIS Cut Line= 3
     1869684.833      663397.956     1869628.431      662946.548
      1869553.42        662497.3
#Sta/Elev= 30
       0  851.47    38.7  846.12    48.4  844.08    58.1  840.21   116.2  809.26
   125.8   802.7   154.9   780.4   164.5  774.65   193.6  762.11   222.6  748.59
   232.3  745.37   290.4  730.79   348.4  713.87   367.8   711.4   406.5  708.46
   416.2  706.79   425.9  704.77   435.6   704.7   474.3  704.71     484  705.15
   493.7  706.76   561.5  706.31     610  710.32   668.1  712.89   677.8  714.44
   726.3  727.21   755.3  735.72     765  737.64   794.1  740.71   910.4  747.36
#Mann= 3 , 0 , 0
       0     .05       0   416.2    .045       0   493.7     .05       0
Bank Sta=416.2,493.7
XS Rating Curve= 0 ,0
Exp/Cntr=0.3,0.1

Type RM Length L Ch R = 1 ,59938.3 ,415.1,400,386.8
XS GIS Cut Line= 3
     1870032.969       663312.53     1870016.563      662857.927
     1869966.655       662403.11
#Sta/Elev= 30
       0  826.69     9.7  823.45    38.7  807.94    96.8  773.55   212.9   723.3
   232.3  716.98   261.3  712.48   319.4  707.95   358.1  707.11   396.8  708.56
   406.5  708.45   416.2  707.24   425.9   705.3   435.5   704.7   474.4   704.7
   484.1   705.1   493.8  706.88   503.6  708.39   542.5  707.51   600.9  708.39
   620.4  710.59   630.1  712.72   639.9  716.13   649.6  721.68   669.1  734.95
   678.8  739.49   698.3  745.12   727.5  751.04   873.5  775.16   912.4  780.59
#Mann= 3 , 0 , 0
       0     .05       0   416.2    .045       0   493.8    .055       0
Bank Sta=416.2,493.8
XS Rating Curve= 0 ,0
Exp/Cntr=0.3,0.1

Type RM Length L Ch R = 1 ,59538.3 ,390.6,400,409.2
XS GIS Cut Line= 3
      1870658.11      663064.837     1870358.638        662714.4
     1870069.747      662360.968
#Sta/Elev= 30
       0  762.19     9.8  757.91    29.4  750.19   107.9  720.39   117.7  717.29
   127.5  715.14   137.3  713.79   156.9  712.01   284.4  707.09   323.7  707.14
   402.1  708.29   411.9  707.67   421.7  705.49   431.5  704.71   441.4   704.7
   480.4  704.77   499.8  706.58   558.1  709.88   567.8   710.8   577.5  712.97
   587.2  718.29   606.6  730.77   626.1   742.5   635.8  746.59   645.5  749.35
   684.4  757.32   742.6  767.87     830  784.48   888.3  798.23   917.4  802.93
#Mann= 3 , 0 , 0
       0     .05       0   411.9    .045       0   499.8     .08       0
Bank Sta=411.9,499.8
XS Rating Curve= 0 ,0
Exp/Cntr=0.3,0.1

Type RM Length L Ch R = 1 ,59138.3 ,558.8,562.1,565.1
XS GIS Cut Line= 3
     1870850.624       662997.79     1870718.768      662563.117
     1870593.845       662122.53
#Sta/Elev= 30
       0  764.84    19.3  757.17      87  728.68   106.3  721.07     116  717.56
   125.6   714.6     145  710.87   154.6  709.63   164.3  709.07   270.6  706.11
   405.9  706.69   415.6  706.45   434.9   704.7     503  704.76   512.7  709.17
   522.4  715.29   532.2  720.42   551.7  728.27   561.4  731.54   571.2  733.52
   610.1  737.13   649.1  741.61   697.8  745.42   727.1  748.33   746.5  750.88
     766     754   834.2  769.84   853.7  775.23   873.2  781.98   912.2  796.77
#Mann= 3 , 0 , 0
       0     .05       0   415.6    .045       0   512.7      .1       0
Bank Sta=415.6,512.7
XS Rating Curve= 0 ,0
Exp/Cntr=0.3,0.1

Type RM Length L Ch R = 1 ,58576.2 ,188.7,189.6,189.3
XS GIS Cut Line= 4
     1871334.848      663019.202     1871277.557      662576.494
     1871260.476       662460.45     1871167.748      661840.817
#Sta/Elev= 30
       0  811.42    58.2  809.04   126.2   803.4   135.9  801.57   155.3  793.81
   232.9  757.24   349.4  715.39   359.1  712.87   378.5  709.38   436.7  706.26
   446.4  704.89   456.2   704.7   514.8  704.74   524.6   706.4   534.4  707.01
   612.6  706.89   651.8   707.5   749.7   711.8   769.3  713.66   779.1  717.15
   798.6     728   808.4  732.79     828  739.31   847.6  744.45   955.3     765
  1004.2  775.12  1072.8  787.77  1141.3  802.61  1170.6     808  1190.2   810.6
#Mann= 3 , 0 , 0
       0     .06       0   436.7    .045       0   524.6     .05       0
Bank Sta=436.7,524.6
XS Rating Curve= 0 ,0
Exp/Cntr=0.3,0.1

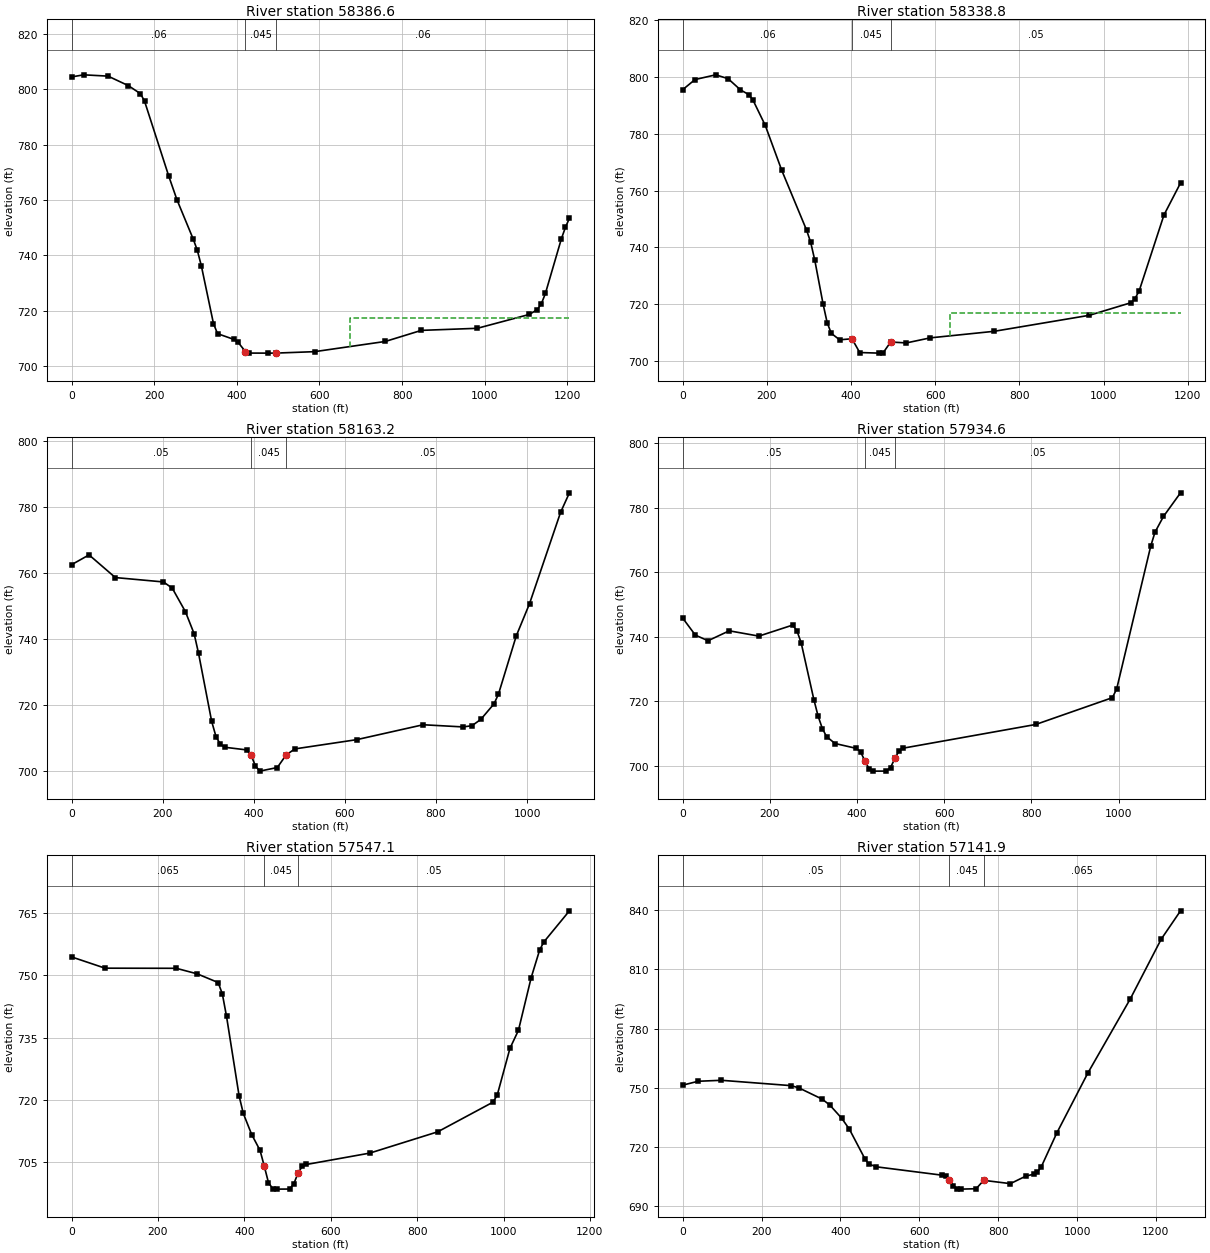
Type RM Length L Ch R = 1 ,58386.6 ,47.8,47.8,47.8
XS GIS Cut Line= 5
     1871526.037      662994.921     1871468.203      662596.785
      1871453.57      662487.454     1871429.466      662280.921
     1871515.404      661804.359
#Sta/Elev= 30
       0  804.48    29.4  805.24    88.3  804.77   137.4  801.34   166.8  798.42
   176.6  795.73   235.5  768.51   255.1  760.09   294.4   745.9   304.2  741.91
     314  736.29   343.4   715.4   353.2  711.74   392.5  709.67   402.3  708.73
   420.7  705.27   429.9  704.72   475.8   704.7   494.2  704.71   588.2  705.23
   759.3  708.92   846.5  712.92     982  713.67    1108  718.69  1127.3  720.45
    1137  722.58  1146.7  726.27  1185.4  746.04  1195.1  750.12  1204.8  753.45
#Mann= 3 , 0 , 0
       0     .06       0   420.7    .045       0   494.2     .06       0
#XS Ineff= 2 , 0
                          674.25          717.35
Permanent Ineff=
       F       F
Bank Sta=420.7,494.2
XS Rating Curve= 0 ,0
Exp/Cntr=0.3,0.1

Type RM Length L Ch R = 1 ,58338.8 ,173.5,175.6,177.6
XS GIS Cut Line= 5
     1871572.912      662984.504     1871515.078      662586.368
     1871500.445      662477.038     1871476.341      662270.505
     1871554.466      661814.775
#Sta/Elev= 30
       0  795.51    29.4  799.08    78.5  800.74   107.9  799.39   137.4  795.44
     157  793.79   166.8  791.94   196.2  782.96   235.5   767.1   294.4   746.1
   304.2  741.78     314  735.44   333.6  720.12   343.4  713.48   353.2  709.76
   372.9  707.49   402.3  707.85   420.7  703.01   466.7   702.8   475.8  702.81
   494.2  706.71   531.5  706.39   588.2  708.17   740.2  710.48   966.5  716.12
  1064.9  720.53  1074.7     722  1084.6  724.69  1143.6  751.43  1182.9  762.67
#Mann= 3 , 0 , 0
       0     .06       0   402.3    .045       0   494.2     .05       0
#XS Ineff= 2 , 0
                          634.11          716.76
Permanent Ineff=
       F       F
Bank Sta=402.3,494.2
XS Rating Curve= 0 ,0
Exp/Cntr=0.3,0.1

Type RM Length L Ch R = 1 ,58163.2 ,224.8,228.6,232.5
XS GIS Cut Line= 4
     1871686.411       662929.72     1871682.071      662593.349
      1871673.39      662411.057      1871731.55      661839.877
#Sta/Elev= 30
       0   762.5    38.4  765.47    96.1   758.6   201.8  757.27   221.1  755.38
   249.9  748.28   269.1  741.58   278.7  735.71   307.6  715.03   317.2  710.37
   326.8  708.08   336.4  707.19   384.4  706.39     394  704.81   403.6  701.57
   413.2  699.96   451.7  701.05   470.9  704.82   490.1  706.69   625.9  709.49
   771.9  714.01   859.5  713.35     879  713.72   898.4  715.62   927.6  720.37
   937.3  723.32   976.3  740.93  1005.4  750.68  1073.6  778.36    1093  784.27
#Mann= 3 , 0 , 0
       0     .05       0     394    .045       0   470.9     .05       0
Bank Sta=394,470.9
XS Rating Curve= 0 ,0
Exp/Cntr=0.3,0.1

Type RM Length L Ch R = 1 ,57934.6 ,392.5,387.5,382.5
XS GIS Cut Line= 4
     1871832.535      662941.816     1871895.612      662558.627
      1871921.26       662363.67     1871991.966      661811.231
#Sta/Elev= 30
       0  745.79    29.1  740.51    58.2  738.77   106.8  741.84   174.8   740.2
   252.4  743.62   262.1  741.85   271.8  738.13     301  720.51   310.7  715.41
   320.4  711.58   330.1  709.08   349.5  706.95   398.2  705.45     408  704.38
   417.8  701.62   427.7   699.1   437.5   698.4     467  698.41   476.8  699.52
   486.7  702.32   496.5  704.72   506.3  705.52   809.7  712.84   985.6  721.14
   995.4  723.82  1073.5  768.02  1083.3  772.36  1102.8  777.25  1141.9  784.56
#Mann= 3 , 0 , 0
       0     .05       0   417.8    .045       0   486.7     .05       0
Bank Sta=417.8,486.7
XS Rating Curve= 0 ,0
Exp/Cntr=0.3,0.1

Type RM Length L Ch R = 1 ,57547.1 ,404.8,405.1,405.4
XS GIS Cut Line= 4
     1872281.105      662943.651     1872283.633       662516.96
     1872268.008      662342.481     1872202.904      661795.606
#Sta/Elev= 30
       0  754.48    77.6  751.76   242.4  751.73   290.9  750.39   339.4  748.29
   349.1  745.53   358.8   740.1   387.9  720.91   397.6  716.68     417  711.59
   436.4  707.75   446.2  703.93   455.9  699.96   465.6  698.54   475.4   698.4
   504.6  698.42   514.3  699.63     524  702.19   533.8  703.89   543.5  704.35
   690.4   707.1   847.7  712.24   975.6   719.4   985.4  721.09  1014.9  732.39
  1034.6  736.76  1064.1  749.49  1083.8  756.19  1093.6  758.12  1152.6  765.61
#Mann= 3 , 0 , 0
       0    .065       0   446.2    .045       0     524     .05       0
Bank Sta=446.2,524
XS Rating Curve= 0 ,0
Exp/Cntr=0.3,0.1

Type RM Length L Ch R = 1 ,57141.9 ,253.1,264.4,275.5
XS GIS Cut Line= 4
      1872369.66      662923.313     1872650.821      662404.981
     1872622.175      662165.397     1872583.112       661735.71
#Sta/Elev= 30
       0  751.23    39.3  753.21    98.3   753.7   275.2  750.98   294.8  749.83
   353.8  744.13   373.5  741.04     403  734.48   422.6   728.9   461.9  713.89
   471.7  711.17   491.4  709.73   657.2   705.5   666.9   704.9   676.5  702.96
   686.2  700.24   695.8  698.69   705.5   698.4   744.1   698.6   763.4  702.87
     831  701.19   870.2  705.02   889.8  705.97   899.6   707.1   909.4  709.77
   948.6   726.9  1027.1  757.27    1135  795.06  1213.4  825.41  1262.4  839.81
#Mann= 3 , 0 , 0
       0     .05       0   676.5    .045       0   763.4    .065       0
Bank Sta=676.5,763.4
XS Rating Curve= 0 ,0
Exp/Cntr=0.3,0.1