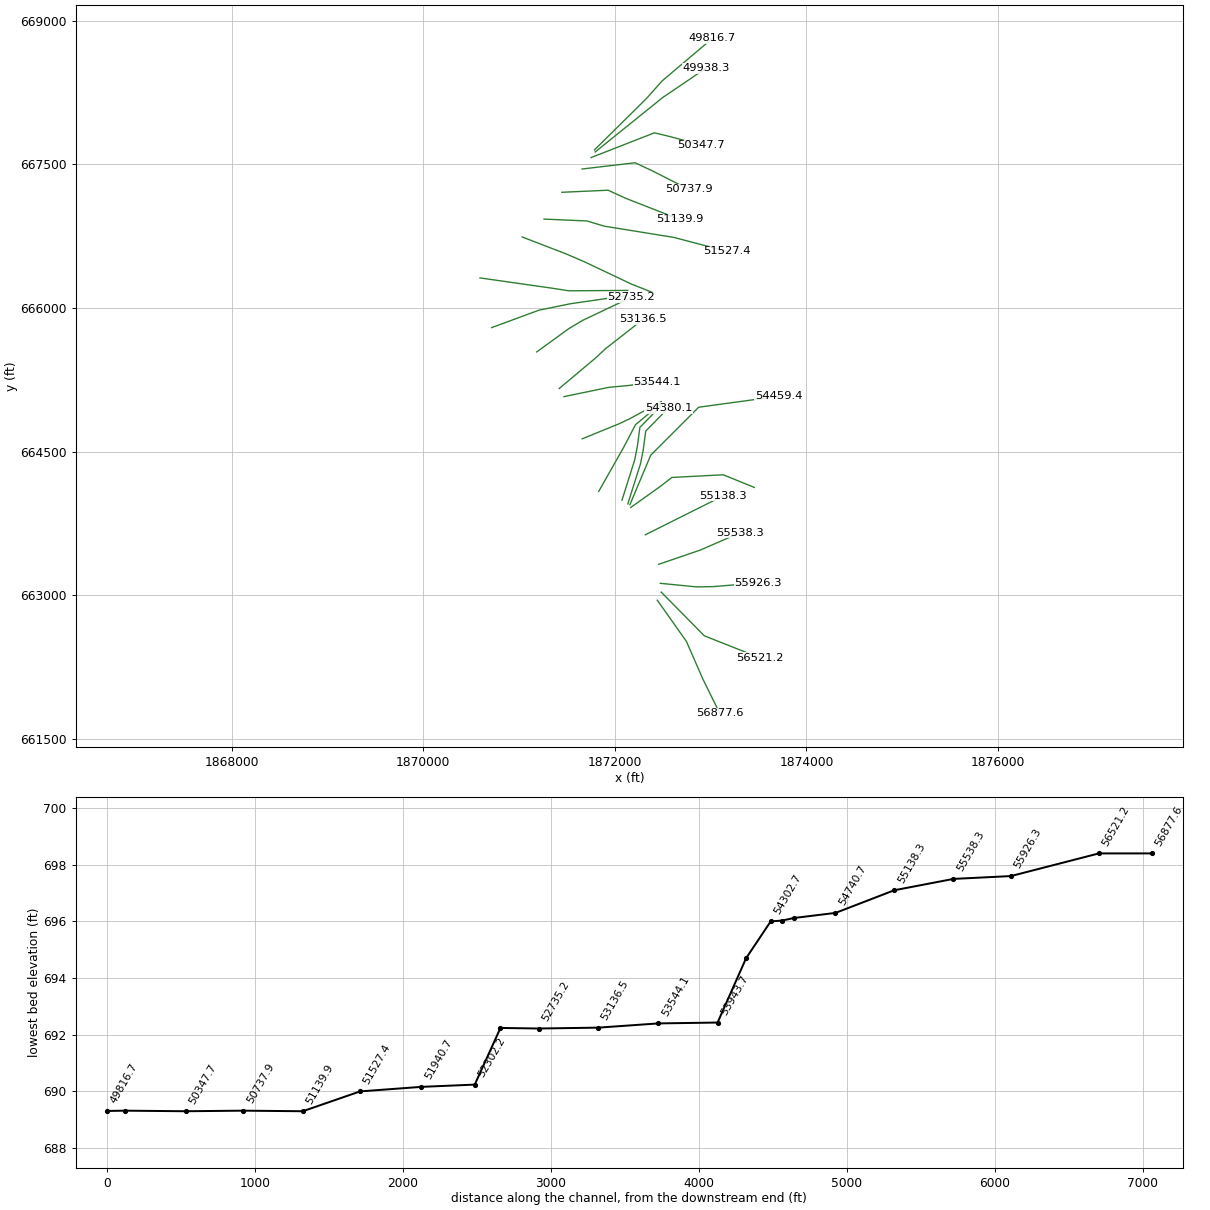
HEC-RAS study SpringCrk2.prj: SpringCrk2

--- SpringCrk2.g01 (geometry) --- (continued)

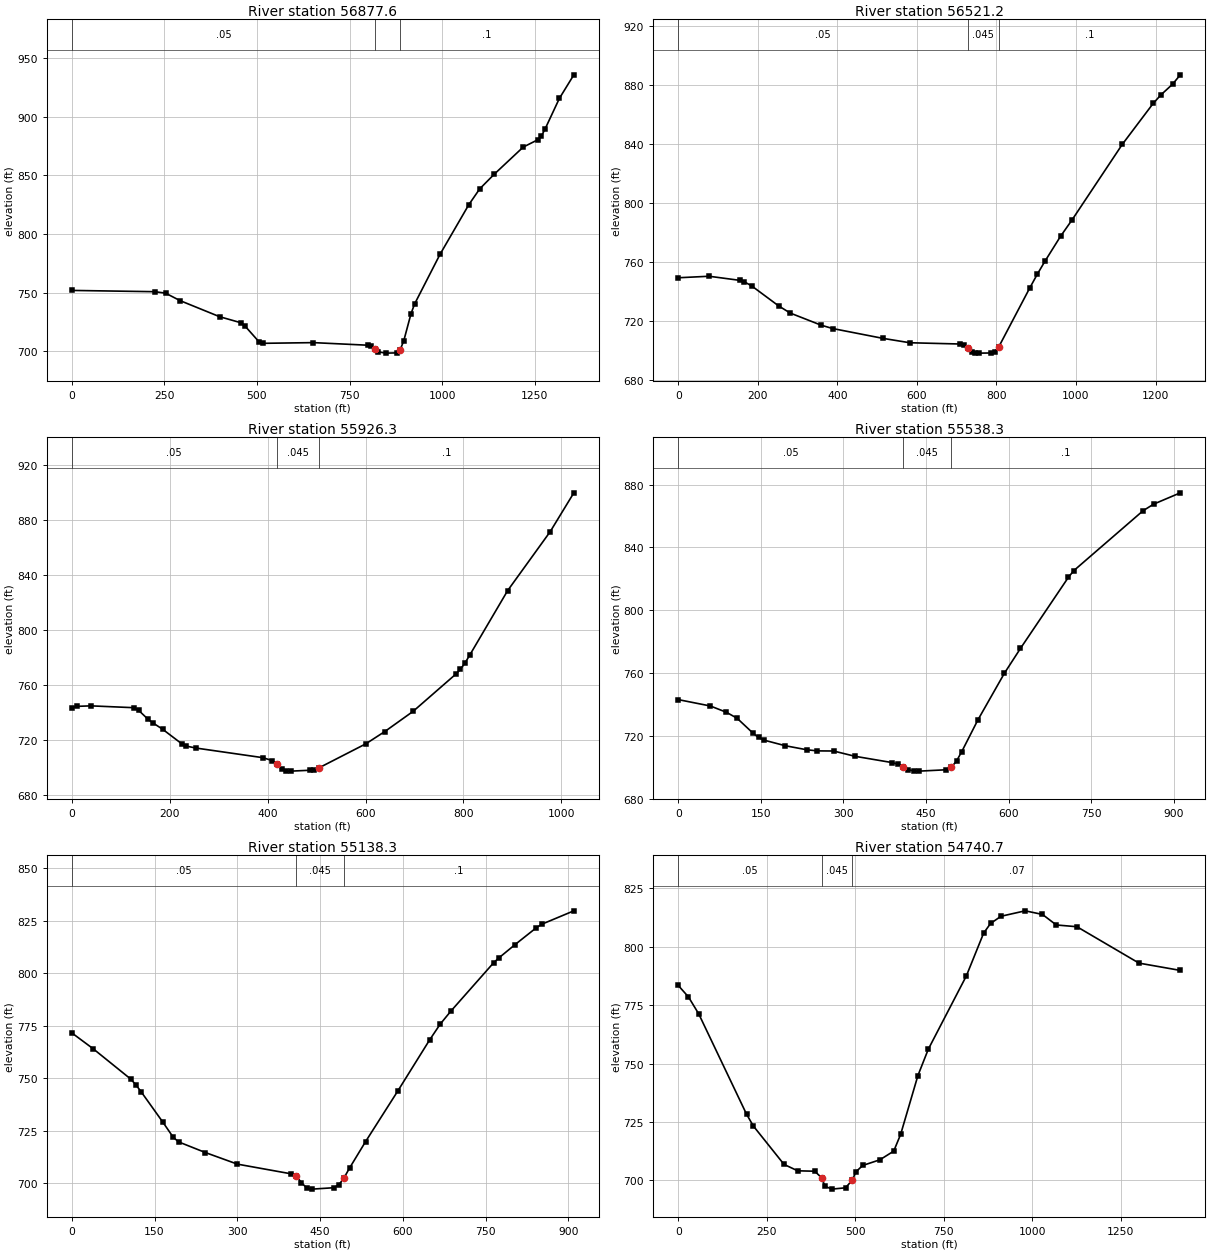
Type RM Length L Ch R = 1 ,56877.6 ,338.6,356.4,374.2
XS GIS Cut Line= 4
     1872443.403      662948.637     1872747.175      662519.564
      1872919.05      662126.335     1873096.133       661766.96
#Sta/Elev= 30
       0  751.84   223.9  750.75   253.1  749.54   292.1  743.18   399.2  729.44
   457.6   724.2   467.3  721.63   506.2  707.81     516  706.76   652.5  707.35
   798.8  705.15   808.6  704.67   818.3  702.28   828.1  699.43   847.6   698.4
   876.8   698.6   886.6  701.21   896.4  709.02   915.9  732.04   925.6  740.32
     994  782.48  1072.1  824.99  1101.4   838.4  1140.5  850.85  1218.7  873.96
  1257.8  880.17  1267.6   883.3  1277.3  889.04  1316.4  915.45  1355.5  935.57
#Mann= 3 , 0 , 0
       0     .05       0   818.3    .045       0   886.6      .1       0
Bank Sta=818.3,886.6
XS Rating Curve= 0 ,0
Exp/Cntr=0.3,0.1

Type RM Length L Ch R = 1 ,56521.2 ,585.7,594.8,603.8
XS GIS Cut Line= 3
     1872484.911      663032.652     1872934.675      662576.856
       1873512.8      662347.689
#Sta/Elev= 30
       0   749.5    77.6  750.52   155.2  747.73   164.9  746.92   184.3  744.04
   252.3  730.44   281.4  725.58     359  717.38   388.1  715.08   514.2  708.43
   582.1  705.44   708.4  704.58   718.1  704.11   727.8   702.2   737.5  699.49
   747.2   698.5     757   698.4   786.1   698.5   795.8  699.48   805.5  702.48
   883.3  742.38   902.7  751.92   922.1  760.79     961  777.56   990.2  788.79
  1116.5     840  1194.2  867.78  1213.6  873.53  1242.8  880.76  1262.2  887.09
#Mann= 3 , 0 , 0
       0     .05       0   727.8    .045       0   805.5      .1       0
Bank Sta=727.8,805.5
XS Rating Curve= 0 ,0
Exp/Cntr=0.3,0.1

Type RM Length L Ch R = 1 ,55926.3 ,381,388,396.9
XS GIS Cut Line= 4
     1872475.147      663124.777     1872853.946      663087.272
     1873025.759       663090.27     1873497.175      663128.939
#Sta/Elev= 30
       0  743.62     9.8  744.65      39  745.03   126.9  743.69   136.6  741.76
   156.2  735.14   165.9   732.6   185.4  728.08   224.5  717.51   234.2  715.77
   253.8  714.36   390.2  707.38   409.3  705.28   418.8  702.42   428.4  699.14
   437.9  697.61   447.5   697.6   485.7  698.22   495.2  698.72   504.8  699.96
   600.8  717.48   639.4  726.37   697.3  741.07   784.2  768.01   793.8  771.59
   803.5  776.37   813.1  782.05   890.4  828.84   977.2  871.61  1025.5  899.82
#Mann= 3 , 0 , 0
       0     .05       0   418.8    .045       0   504.8      .1       0
Bank Sta=418.8,504.8
XS Rating Curve= 0 ,0
Exp/Cntr=0.3,0.1

Type RM Length L Ch R = 1 ,55538.3 ,397,400,401.2
XS GIS Cut Line= 3
     1872458.713      663323.321     1872890.946      663471.121
     1873307.911      663652.436
#Sta/Elev= 30
       0  743.05    58.3  738.99    87.5  734.98   106.9  731.17   136.1  721.56
   145.8  718.95   155.5  717.27   194.4  713.67   233.3  711.11   252.7  710.39
   281.9  710.32   320.7  706.96   388.8  702.91   398.5  701.94   408.2  700.24
   417.9  698.45   427.6  697.57   437.4   697.5   485.8  698.35   495.5  699.84
   505.2  703.93   514.8  709.99   543.9  730.05   592.2  759.88   621.3  775.66
   708.3  820.94     718  825.16   843.8  863.33   863.1  867.56   911.5  874.76
#Mann= 3 , 0 , 0
       0     .05       0   408.2    .045       0   495.5      .1       0
Bank Sta=408.2,495.5
XS Rating Curve= 0 ,0
Exp/Cntr=0.3,0.1

Type RM Length L Ch R = 1 ,55138.3 ,393,397.6,402
XS GIS Cut Line= 3
     1872318.748      663631.602     1872725.712      663835.085
     1873132.676      664038.567
#Sta/Elev= 30
       0  771.54    38.7  763.98   106.5   749.6   116.2  746.78   125.8  743.45
   164.6  729.18   183.9  721.81   193.6   719.6     242  714.54   300.1  709.01
   396.9  704.42   406.6  703.31   416.3  700.24     426  697.54   435.6   697.1
   474.4  697.76     484   699.1   493.7  702.59   503.4  707.11   532.4  719.69
   590.5  743.68   648.6  768.18     668  775.78   687.3  781.95   764.8  804.99
   774.5  807.33   803.5  813.59   842.2  821.66   851.9  823.29     910  829.67
#Mann= 3 , 0 , 0
       0     .05       0   406.6    .045       0   493.7      .1       0
Bank Sta=406.6,493.7
XS Rating Curve= 0 ,0
Exp/Cntr=0.3,0.1

Type RM Length L Ch R = 1 ,54740.7 ,269.8,281.4,293
XS GIS Cut Line= 5
     1872166.956      663916.871     1872481.116      664140.658
     1872595.323      664229.943     1873132.157      664257.845
     1873456.784      664125.866
#Sta/Elev= 30
       0  783.44    28.9  778.52    57.9  771.27   192.9  728.39   212.1  723.33
   298.9  706.88   337.5  704.14   385.7  703.96     405  701.18   414.7  697.53
     434   696.3   472.7  696.87     492  700.19   501.7  703.64     521  706.41
   569.8  708.85   608.9  712.56   628.4  719.71   677.3  744.91   706.6  756.16
   814.1  787.51     863  805.84   882.5  809.94   911.9  813.03   980.3  815.36
  1029.2  813.82  1068.2  809.31  1126.6  808.56  1301.9  792.99  1418.7  789.87
#Mann= 3 , 0 , 0
       0     .05       0     405    .045       0     492     .07       0
Bank Sta=405,492
XS Rating Curve= 0 ,0
Exp/Cntr=0.3,0.1

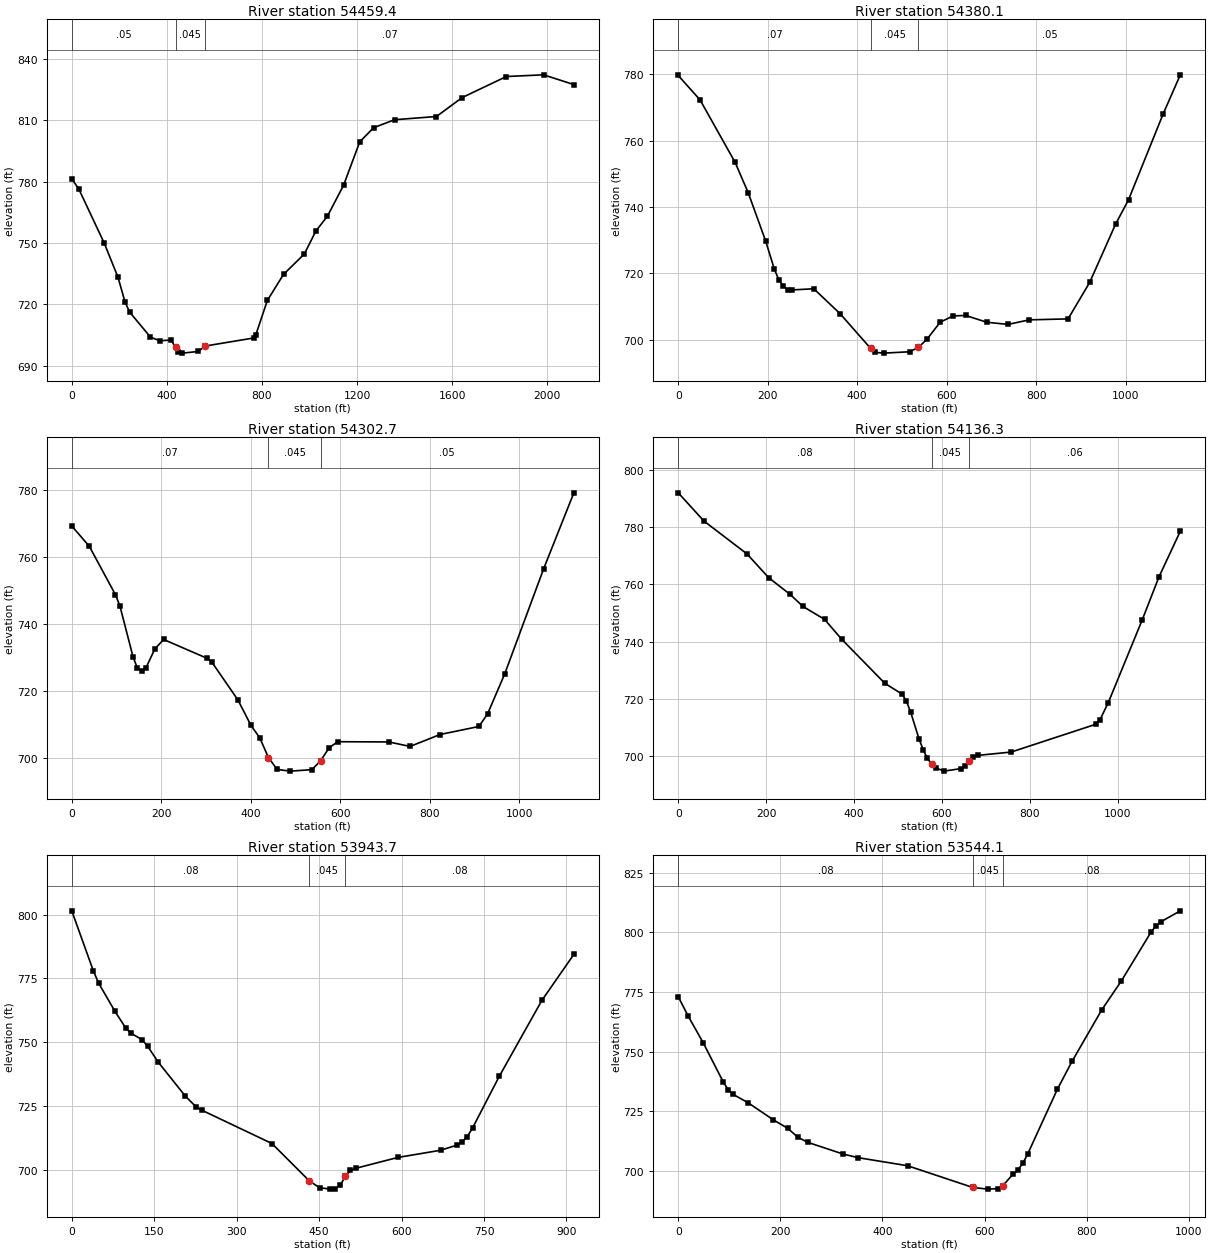
Type RM Length L Ch R = 1 ,54459.4 ,73.9,79.3,84.8
XS GIS Cut Line= 5
     1872157.765      663945.345     1872300.994      664286.057
     1872374.779      664461.838     1872876.081      664963.141
     1873710.257      665077.255
#Sta/Elev= 30
       0  781.36    29.2  776.55   136.2  750.05   194.5  733.24   223.7  721.21
   243.2  716.23   330.7  703.98   369.6  702.18   417.2  702.52   436.3  699.02
   445.8  696.58   464.9  696.12   531.6  696.92   560.2  699.57   764.2  703.52
   773.9  705.09   822.4  721.92   890.4  734.67   977.8  744.63  1026.4  755.89
    1075  763.16  1142.9  778.31  1210.9  799.56  1269.2  806.47  1357.3  810.37
  1533.5  811.95  1641.2   821.2  1827.2  831.52  1983.8  832.35  2111.1  827.58
#Mann= 3 , 0 , 0
       0     .05       0   436.3    .045       0   560.2     .07       0
Bank Sta=436.3,560.2
XS Rating Curve= 0 ,0
Exp/Cntr=0.3,0.1

Type RM Length L Ch R = 1 ,54380.1 ,77,77.4,79.1
XS GIS Cut Line= 5
     1872136.064      663954.026     1872268.384      664373.282
     1872296.654      664516.092     1872322.696      664713.575
     1872559.241       664954.46
#Sta/Elev= 30
       0  779.56    48.8  772.21     127  753.45   156.3  744.31   195.4  729.75
   214.9  721.23   224.7  718.14   234.5  716.19   244.2  715.16     254  715.04
   302.9   715.4   361.5  707.92   429.9  697.46   439.6  696.26     459  696.03
   517.3  696.44   536.7  697.77   556.1  700.25   585.2  705.31   613.7  707.21
   642.1  707.37   689.6  705.32     737  704.67   784.4  706.04   871.2  706.33
   919.5  717.31   977.3  734.82  1006.3  742.18  1083.4  767.92    1122  779.76
#Mann= 3 , 0 , 0
       0     .07       0   429.9    .045       0   536.7     .05       0
Bank Sta=429.9,536.7
XS Rating Curve= 0 ,0
Exp/Cntr=0.3,0.1

Type RM Length L Ch R = 1 ,54302.7 ,168.5,166.3,162.7
XS GIS Cut Line= 5
       1872075.3      663993.088      1872207.62      664412.344
      1872235.89      664555.154     1872261.932      664752.637
     1872498.477      664993.522
#Sta/Elev= 30
       0  769.25    39.1   763.2    97.7  748.69   107.5  745.38   136.8  730.22
   146.6  726.77   156.3  725.96   166.1  726.96   185.6  732.48   205.2  735.34
   302.9  729.68   312.6  728.66   371.2  717.29   400.6  709.64   420.1  705.95
   439.6  700.02     459   696.5   488.2     696   536.7  696.44   556.1   699.1
   575.5  703.04   594.7  704.79   708.5  704.72     756  703.38     823  706.94
   909.8  709.34   929.1  713.07   967.7  725.12  1054.5  756.46    1122  779.16
#Mann= 3 , 0 , 0
       0     .07       0   439.6    .045       0   556.1     .05       0
Bank Sta=439.6,556.1
XS Rating Curve= 0 ,0
Exp/Cntr=0.3,0.1

Type RM Length L Ch R = 1 ,54136.3 ,212.7,192.6,172.1
XS GIS Cut Line= 4
     1871832.244      664084.234     1872092.661      664544.304
     1872216.359      664780.849     1872483.286      665002.203
#Sta/Elev= 30
       0     792    58.7  782.11   156.6  770.62   205.6  762.35   254.5   756.5
   283.9  752.26   332.9  747.76     372   740.8   469.9  725.43   509.1  721.64
   518.9  719.27   528.7  715.41   547.7  706.03   557.3   702.2   566.8  699.14
   576.3  697.27   585.9  695.82   604.9   694.7   643.1  695.58   652.6  696.48
   662.1  698.13   671.7  699.58   681.2   700.2   757.5  701.37   949.7  711.06
   959.4  712.58   978.6  718.68  1055.7  747.57  1094.2  762.74  1142.4  778.57
#Mann= 3 , 0 , 0
       0     .08       0   576.3    .045       0   662.1     .06       0
Bank Sta=576.3,662.1
XS Rating Curve= 0 ,0
Exp/Cntr=0.3,0.1

Type RM Length L Ch R = 1 ,53943.7 ,407.4,399.6,391.6
XS GIS Cut Line= 4
     1871660.122      664633.214     1872042.748      664789.529
     1872153.028      664841.293     1872485.456      665021.734
#Sta/Elev= 30
       0  801.52    39.4   777.9    49.2  773.04    78.7  762.07    98.4  755.51
   108.2  753.49   127.9  751.01   137.8  748.52   157.5  742.15   206.7  728.86
   226.3  724.63   236.2  723.41   364.1  710.31   432.1  695.67   450.8     693
   469.6  692.43   478.9   692.6   488.3  693.86   497.7  697.49     507  699.74
   516.4  700.58   593.3  704.85   670.9  707.66     700  709.63   709.7  710.86
   719.4  712.98   729.1  716.38   777.6   736.6   855.2   766.4   913.4  784.44
#Mann= 3 , 0 , 0
       0     .08       0   432.1    .045       0   497.7     .08       0
Bank Sta=432.1,497.7
XS Rating Curve= 0 ,0
Exp/Cntr=0.3,0.1

Type RM Length L Ch R = 1 ,53544.1 ,392.6,407.6,422.6
XS GIS Cut Line= 4
     1871469.831      665073.818     1871938.353      665170.928
     1872133.894      665188.835     1872439.883      665227.897
#Sta/Elev= 30
       0  773.04    19.5   764.9    48.8  753.77    87.9  737.42    97.6  734.11
   107.4  732.12   136.7  728.61   185.5  721.55   214.8  717.82   234.4  714.12
   253.9  711.99   322.2  707.15   351.5  705.61   449.2   702.2   576.7  693.11
   606.1   692.4   625.8   692.6   635.6  693.79   655.2  698.58     665  700.42
   674.8  703.18   684.5  707.17   742.3  734.17   771.2  745.92   829.1  767.41
   867.6  779.57   925.5  799.95   935.1  802.65   944.8  804.39   983.3  809.03
#Mann= 3 , 0 , 0
       0     .08       0   576.7    .045       0   635.6     .08       0
Bank Sta=576.7,635.6
XS Rating Curve= 0 ,0
Exp/Cntr=0.3,0.1

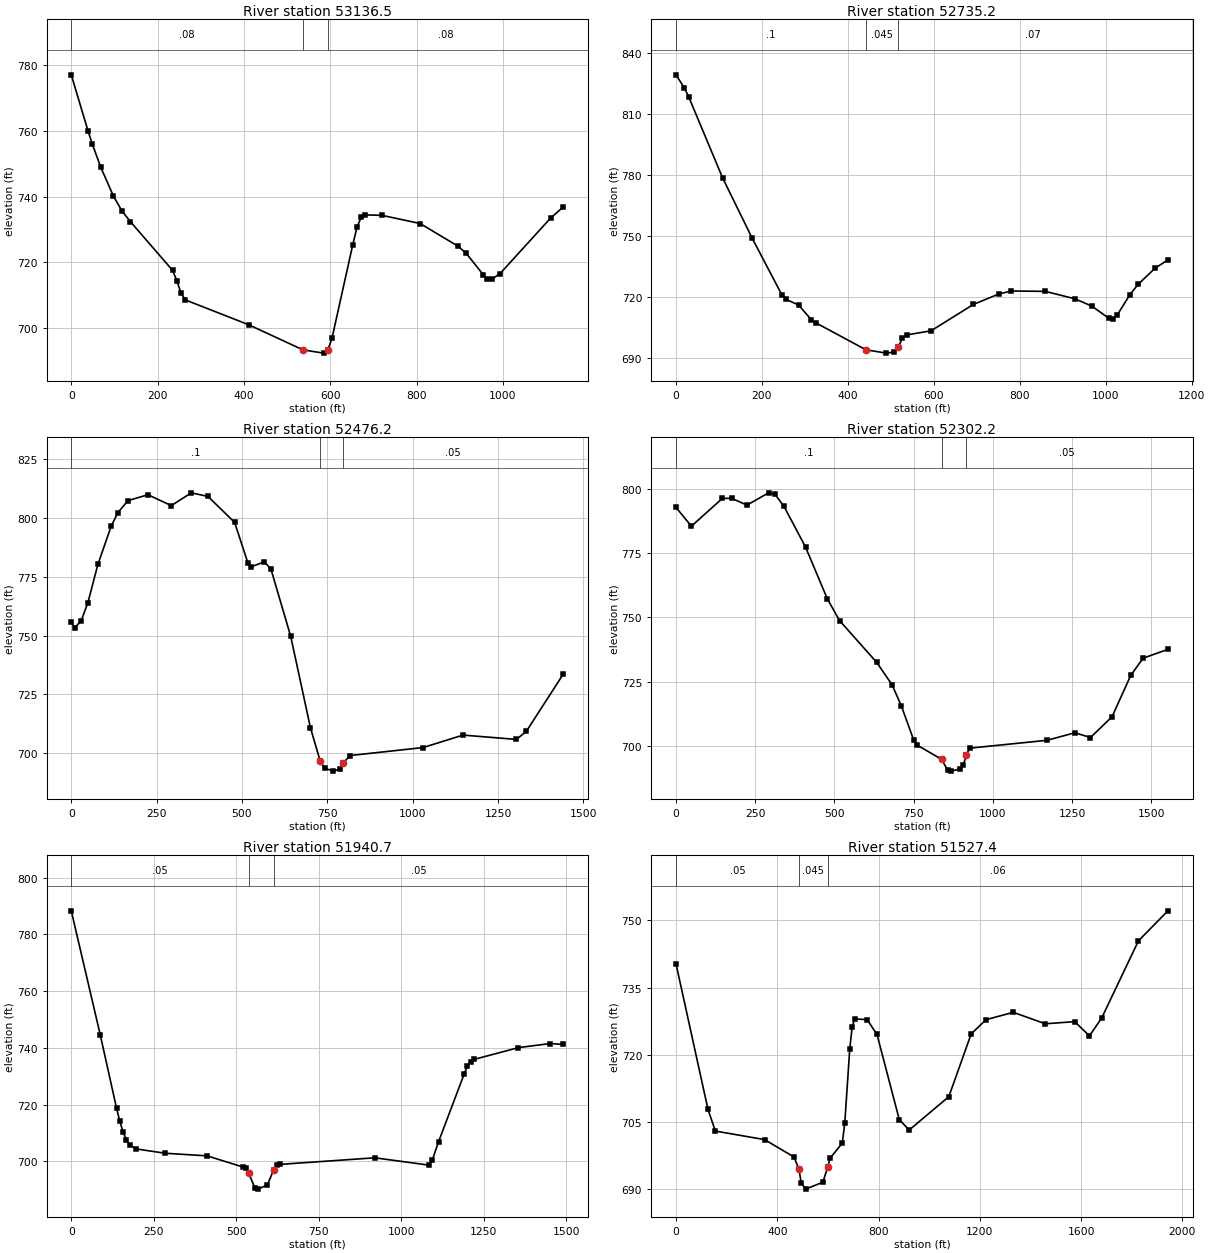
Type RM Length L Ch R = 1 ,53136.5 ,406,401.3,396.2
XS GIS Cut Line= 4
     1871419.918      665158.453     1871801.897       665479.31
     1871899.519      665570.779     1872298.824      665883.279
#Sta/Elev= 30
       0  777.13    39.1  759.91    48.9  755.94    68.5  748.89    97.8  740.12
   117.4  735.61   136.9  732.37   234.8  717.48   244.5  714.38   254.3  710.57
   264.1  708.49   410.8  700.92   537.1  693.23   584.9  692.25   594.4  693.22
     604  696.75   652.1  725.26   661.9  730.63   671.6  733.64   681.4  734.42
   720.4  734.26   808.2  731.78   895.9  724.88   915.4  722.64   954.4  716.19
   964.2  714.95   973.9  714.75   993.4   716.5  1110.4  733.42  1139.7  736.82
#Mann= 3 , 0 , 0
       0     .08       0   537.1    .045       0   594.4     .08       0
Bank Sta=537.1,594.4
XS Rating Curve= 0 ,0
Exp/Cntr=0.3,0.1

Type RM Length L Ch R = 1 ,52735.2 ,265.5,259,250.4
XS GIS Cut Line= 4
     1871185.543      665540.397     1871519.744      665783.453
     1871666.253       665870.68     1872172.956      666111.144
#Sta/Elev= 30
       0  829.43    19.7  822.85    29.5  818.59   108.2  778.75   177.1  748.94
     246  721.09   255.8  718.73   285.3  715.94   314.8   708.7   324.7  707.24
   441.7  693.89     489  692.22     508  692.75   517.4  695.38   526.9   699.5
   536.4  701.18   593.6  703.23     692  716.23     751  721.36   780.5  722.85
   859.3  722.67   928.1  719.01   967.5  715.41  1006.9  709.44  1016.7  709.28
  1026.5  710.94  1056.1  721.05  1075.7  726.22  1115.1  734.17  1144.6  738.14
#Mann= 3 , 0 , 0
       0      .1       0   441.7    .045       0   517.4     .07       0
Bank Sta=441.7,517.4
XS Rating Curve= 0 ,0
Exp/Cntr=0.3,0.1

Type RM Length L Ch R = 1 ,52476.2 ,181.8,174,166.1
XS GIS Cut Line= 4
     1870714.623      665794.304     1871209.414      665976.595
     1871539.276       666043.87     1872110.022      666126.335
#Sta/Elev= 30
       0  755.92     9.8  753.17    29.3  756.37    48.8  764.05    78.1  780.34
   117.2  796.68   136.7  802.37     166  807.44   224.6  809.96     293  805.33
   351.5  810.77   400.4  809.24   478.5  798.16   517.5   780.8   527.3  779.29
   565.8  781.41     585  778.19   642.7  749.62   700.4  710.72   729.3  696.38
   742.7  693.45   767.8  692.24     787  693.18   796.6  695.63   815.9  698.88
  1030.1  702.27  1147.4  707.59  1303.8  705.74  1333.1  709.27  1440.6  733.51
#Mann= 3 , 0 , 0
       0      .1       0   729.3    .045       0   796.6     .05       0
Bank Sta=729.3,796.6
XS Rating Curve= 0 ,0
Exp/Cntr=0.3,0.1

Type RM Length L Ch R = 1 ,52302.2 ,367.4,361.5,355.5
XS GIS Cut Line= 4
     1870593.095      666312.967     1871354.814       666204.46
     1871519.744      666178.418     1872136.064      666182.759
#Sta/Elev= 30
       0  792.73    48.7  785.44   146.1  796.21   175.3  796.29     224  793.62
   292.2   798.4   311.7  797.95   340.9  793.12     409  777.29   477.2  757.32
   516.2  748.74   633.1  732.56   681.8  723.84     711  715.68   749.9  702.45
   759.7  700.46   838.2  694.83   857.8  690.54   867.6  690.24   897.1   691.1
   906.9  692.64   916.7  696.45   926.6  699.17  1171.2  702.22  1259.2  705.16
  1308.1  703.29  1376.6  711.41  1435.3  727.45  1474.4  734.14  1552.7  737.57
#Mann= 3 , 0 , 0
       0      .1       0   838.2    .045       0   916.7     .05       0
Bank Sta=838.2,916.7
XS Rating Curve= 0 ,0
Exp/Cntr=0.3,0.1

Type RM Length L Ch R = 1 ,51940.7 ,410.3,413.4,416.7
XS GIS Cut Line= 5
     1871033.633      666740.484     1871500.213      666560.363
     1871690.289      666478.102     1872170.786      666250.033
     1872404.701      666157.116
#Sta/Elev= 30
       0  788.33    88.3  744.37   137.3  718.67   147.1   714.1   156.9  710.37
   166.7   707.6   176.5  705.83   196.1  704.35   284.4  702.82   411.9  701.89
     519  698.01   528.4  697.45   537.8  695.77   556.6  690.56     566  690.16
   594.3  691.64   613.1  696.88   622.5  698.57   631.9  698.88     920  701.21
  1084.4  698.62  1094.1  700.41  1113.4  706.96  1190.8   730.8  1200.4  733.49
  1210.1  735.16  1219.8  735.89  1355.3  740.08  1452.1  741.52  1490.8  741.19
#Mann= 3 , 0 , 0
       0     .05       0   537.8    .045       0   613.1     .05       0
Bank Sta=537.8,613.1
XS Rating Curve= 0 ,0
Exp/Cntr=0.3,0.1

Type RM Length L Ch R = 1 ,51527.4 ,391.1,387.5,384
XS GIS Cut Line= 5
     1871261.859      666927.159     1871708.546      666907.585
     1871890.838      666853.331     1872615.664      666736.144
      1873168.59      666591.144
#Sta/Elev= 30
       0  740.33   126.4  707.79   155.5  702.97   349.9  701.06   466.1  697.18
   485.2  694.53   494.7  691.41   511.8     690   580.2  691.54   599.3  694.94
   608.8  696.92   656.9  700.28   666.7  704.76   686.3  721.27     696  726.28
   705.8  728.02   754.8  727.86     794  724.55   882.1  705.52   921.2   703.2
  1077.8  710.66    1166  724.66  1224.7  727.85  1332.4  729.49  1458.8  726.93
    1575  727.41  1633.1  724.23  1681.6  728.22  1826.9  745.47  1943.2  752.16
#Mann= 3 , 0 , 0
       0     .05       0   485.2    .045       0   599.3     .06       0
#XS Ineff= 2 , 0
                          678.93          713.24
Permanent Ineff=
       F       F
Bank Sta=485.2,599.3
XS Rating Curve= 0 ,0
Exp/Cntr=0.3,0.1

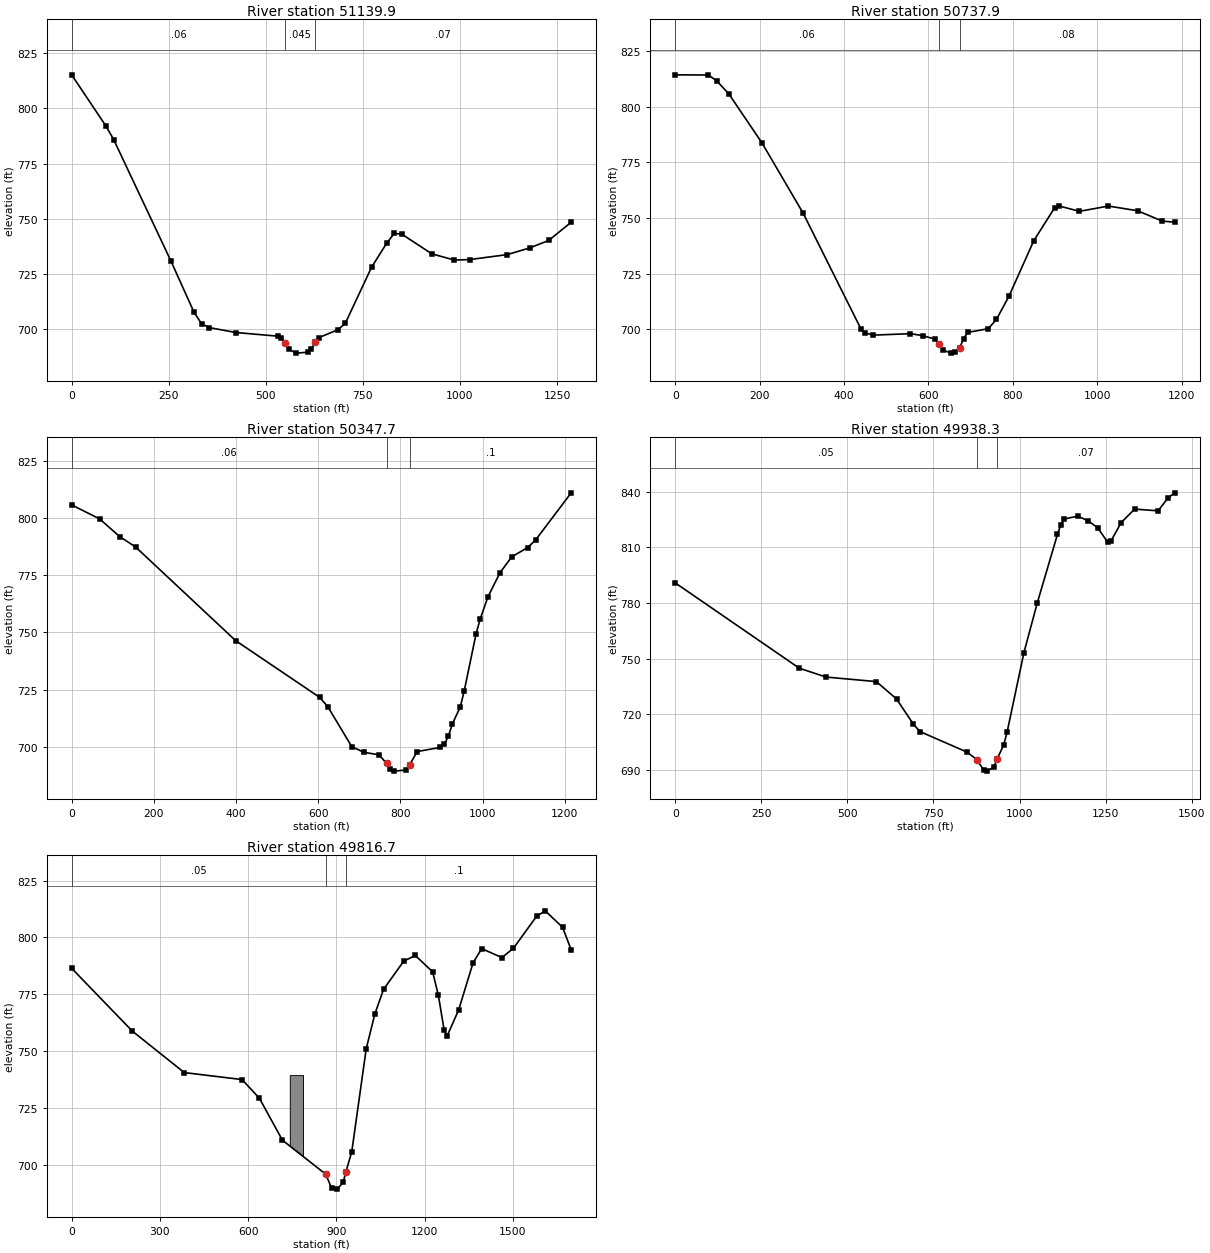
Type RM Length L Ch R = 1 ,51139.9 ,402,402,401.4
XS GIS Cut Line= 4
      1871448.13      667207.064     1871929.901      667228.766
     1872114.362       667144.13     1872674.258      666924.946
#Sta/Elev= 30
       0  815.12    88.6   791.9   108.3  785.83   255.9  730.87   314.9  707.87
   334.6  702.57   354.3  700.84   423.2  698.62   530.6  696.97   540.2  696.36
   549.9  694.08   559.6  690.97   578.9   689.3   607.9  689.72   617.6  691.24
   627.2  694.17   636.9  696.33   685.2  699.84   704.6  702.72   772.5  728.17
   811.3  738.99   830.7  743.39   850.1   743.1   927.7  734.18   985.8  731.37
  1024.6  731.58  1121.6  733.84  1179.8  736.87  1228.3  740.22  1286.5  748.46
#Mann= 3 , 0 , 0
       0     .06       0   549.9    .045       0   627.2     .07       0
Bank Sta=549.9,627.2
XS Rating Curve= 0 ,0
Exp/Cntr=0.3,0.1

Type RM Length L Ch R = 1 ,50737.9 ,385.6,390.2,394.8
XS GIS Cut Line= 4
     1871658.633       667450.12     1872212.019      667515.224
       1872387.8      667432.759     1872774.085      667237.446
#Sta/Elev= 30
       0  814.31    78.2  814.22    97.8  811.68   127.1  805.66   205.3  783.76
     303  752.17   439.9  700.22   449.7  698.44   469.2   697.4   557.2  698.06
   586.3  697.18   615.4  695.61   625.2  693.35   634.9  690.62   654.3  689.32
     664  689.67   673.7  691.57   683.4  695.85   693.1  698.62   741.7  700.29
   761.2  704.45   790.7  714.82   849.7   739.8   898.9  754.54   908.8  755.45
     958  753.01  1026.8  755.37  1095.7  753.26  1154.7  748.59  1184.2  748.14
#Mann= 3 , 0 , 0
       0     .06       0   625.2    .045       0   673.7     .08       0
Bank Sta=625.2,673.7
XS Rating Curve= 0 ,0
Exp/Cntr=0.3,0.1

Type RM Length L Ch R = 1 ,50347.7 ,388.8,409.4,428.2
XS GIS Cut Line= 4
     1871751.949      667569.477     1872413.841      667827.724
     1872576.602      667788.661     1872902.123      667699.686
#Sta/Elev= 30
       0  805.82    68.1  799.68   116.8  791.97   155.7  787.38     399  746.41
   603.4  721.58   622.9  717.57   681.3  700.07   710.5  697.54   747.7  696.46
   766.3  692.65   775.6  690.13   784.9   689.3   812.8  689.78   822.1  692.08
   840.7  697.87   897.2  699.68   906.8  701.07   916.4  704.52   926.1  709.94
   945.4  717.36     955  724.38   983.9   749.4   993.6  755.72  1012.8  765.59
  1041.8  776.06  1070.7  783.09  1109.3  787.14  1128.6  790.45  1215.3   811.1
#Mann= 3 , 0 , 0
       0     .06       0   766.3    .045       0   822.1      .1       0
Bank Sta=766.3,822.1
XS Rating Curve= 0 ,0
Exp/Cntr=0.3,0.1

Type RM Length L Ch R = 1 ,49938.3 ,117.8,121.6,127.2
XS GIS Cut Line= 3
     1871795.352      667628.071     1872500.404      668196.352
     1872952.036      668502.637
#Sta/Elev= 30
       0  790.74   360.3  744.77   438.2     740   584.2  737.56   642.7  728.18
   691.3   714.7   710.8  710.63   847.1   699.6   876.4  695.48   895.8  689.82
   905.6  689.32     925  691.49   934.8  695.85   954.3  703.55     964  710.49
  1012.8  753.24  1051.7   780.1  1110.2  816.92  1119.9  822.14  1129.7  825.18
  1168.7  826.72  1197.9  824.35  1227.1  820.49  1256.4  812.56  1266.1  813.52
  1295.3  823.24  1334.3  830.53  1402.5   829.6  1431.8  836.68  1451.3   839.3
#Mann= 3 , 0 , 0
       0     .05       0   876.4    .045       0   934.8     .07       0
Bank Sta=876.4,934.8
XS Rating Curve= 0 ,0
Exp/Cntr=0.3,0.1

Type RM Length L Ch R = 1 ,49816.7 ,132.7,144.8,156.9
XS GIS Cut Line= 4
     1871787.105      667648.904      1872331.81      668187.099
     1872495.005      668370.693     1873019.744      668814.269
#Sta/Elev= 30
       0  786.42   206.2  758.81   382.9  740.56   579.2  737.49   638.1  729.33
   716.6  710.85     864  695.87   883.6  689.79   903.3  689.31     923   692.3
   932.8  697.04   952.4  705.72  1001.6  751.06    1031  766.39  1060.5  777.15
  1129.2  789.58  1168.4  792.05  1227.3  784.88    1247  774.47  1266.6  759.14
  1276.4  756.58  1315.7  768.06  1364.8   788.8  1394.2  795.07  1462.9  791.13
  1502.2  795.24  1580.7  809.26  1610.1  811.69    1669  804.48  1698.5  794.53
#Mann= 3 , 0 , 0
       0     .05       0     864    .045       0   932.8      .1       0
#Block Obstruct= 1 ,-1
   741.7   786.8  739.44
Bank Sta=864,932.8
XS Rating Curve= 0 ,0
Exp/Cntr=0.3,0.1