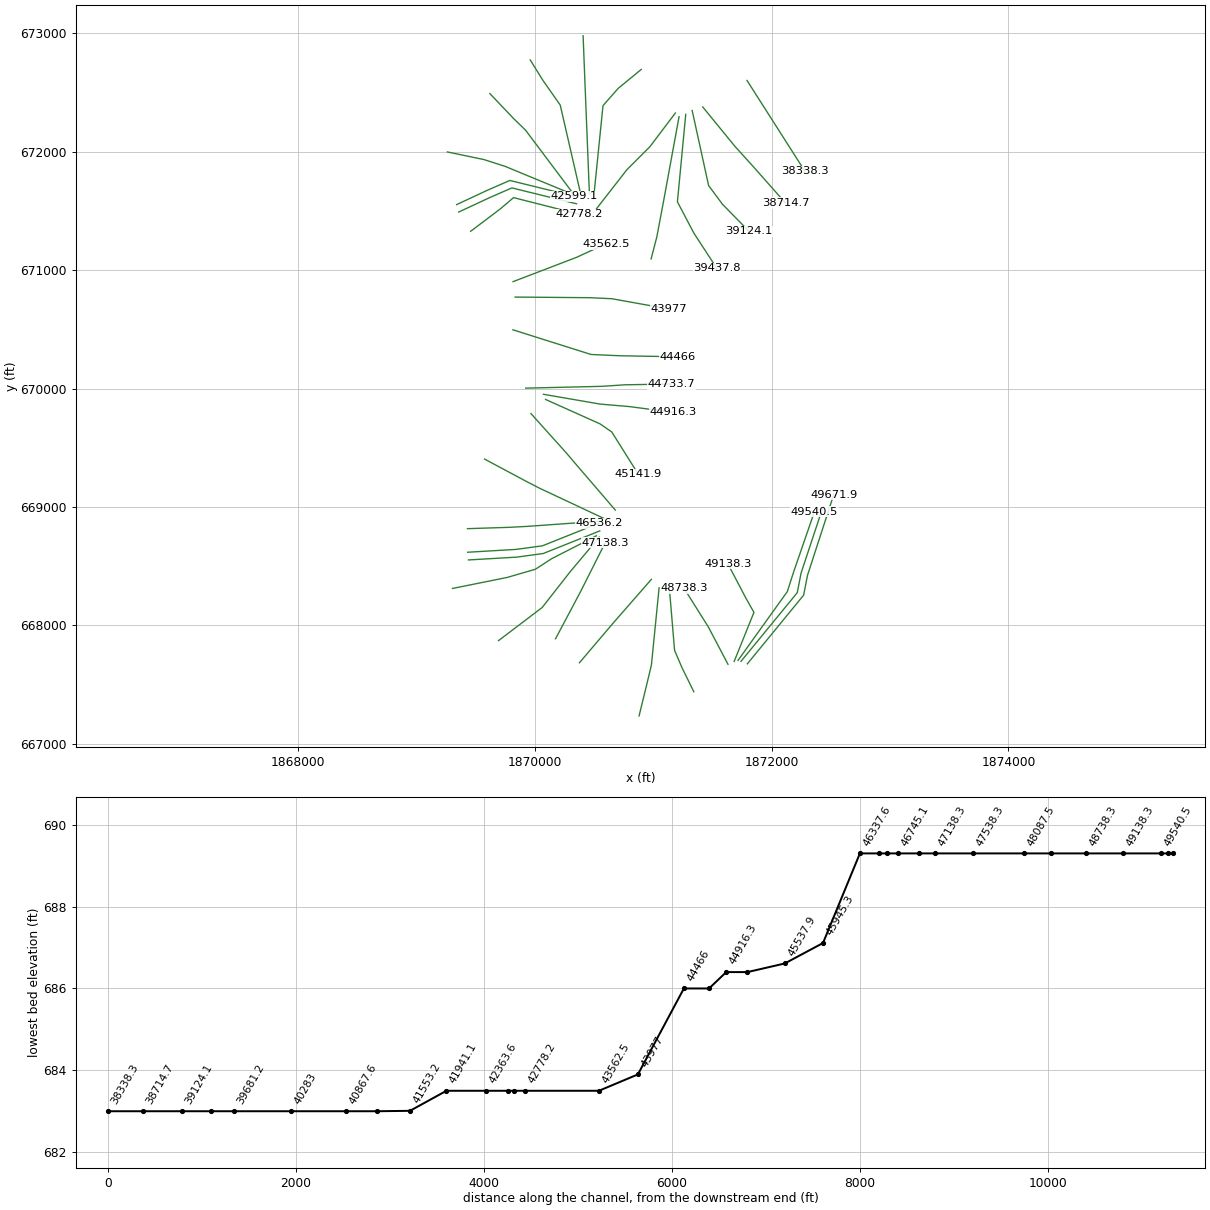
HEC-RAS study SpringCrk2.prj: SpringCrk2

--- SpringCrk2.g01 (geometry) --- (continued)

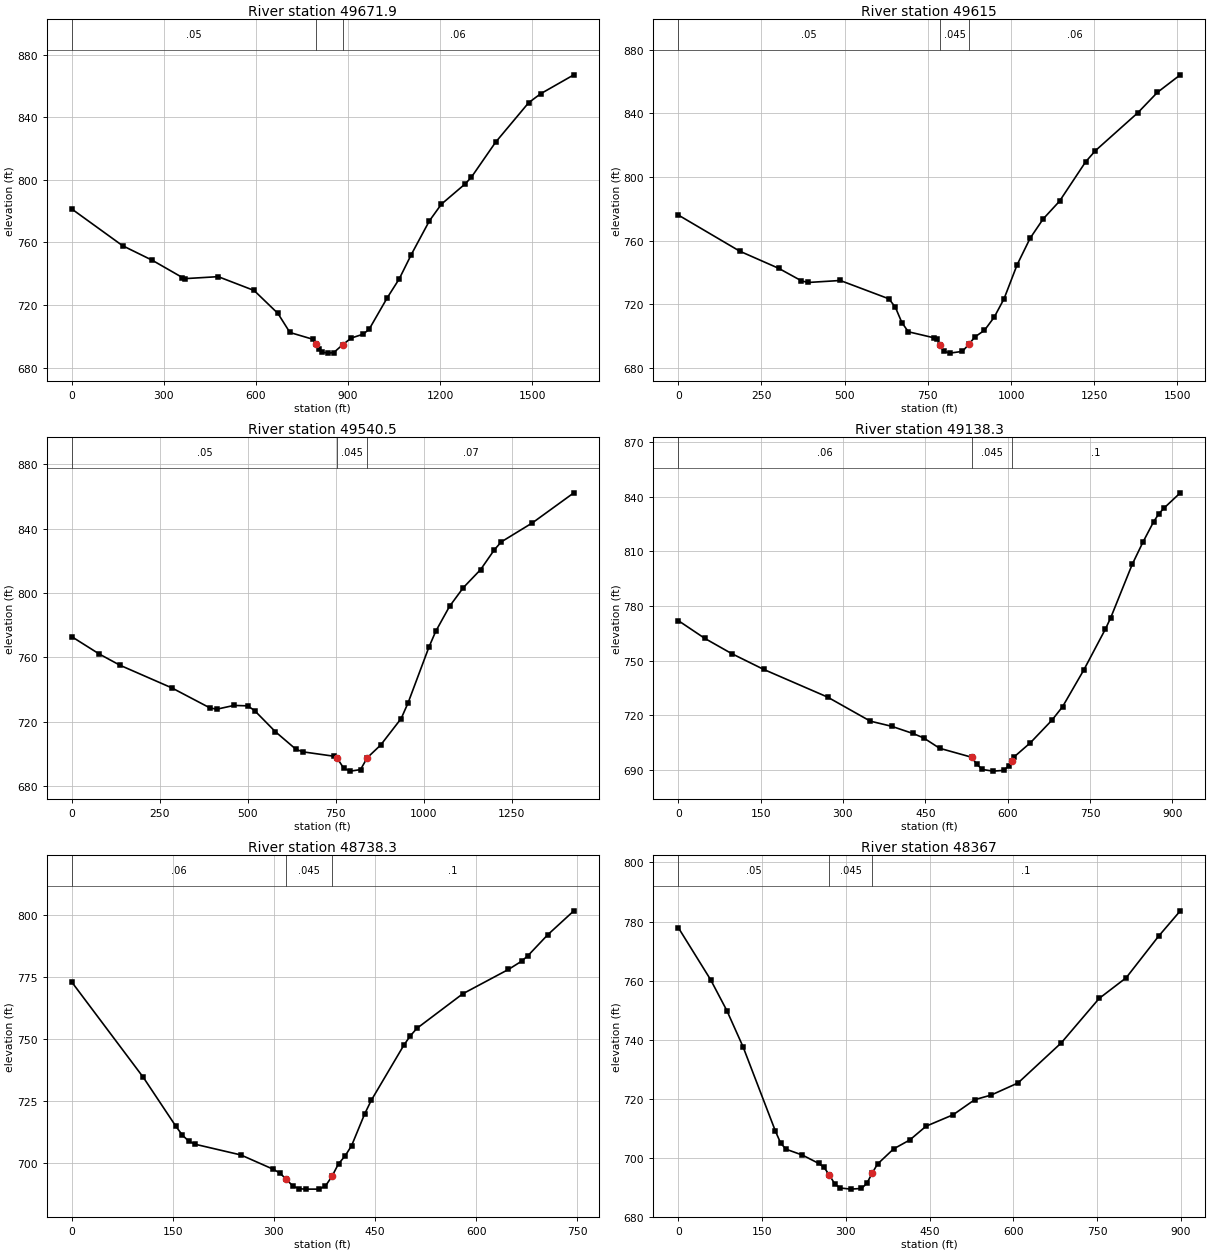
Type RM Length L Ch R = 1 ,49671.9 ,56.9,56.9,56.9
XS GIS Cut Line= 4
     1871795.786      667674.946     1872271.046      668254.807
     1872303.598      668421.908     1872524.953      669102.897
#Sta/Elev= 30
       0   781.4   165.5  757.95   262.9  748.57   360.3  737.62     370  736.91
   477.1  738.16     594  729.34   671.8  714.65   710.8  702.49   787.6  698.04
     797  695.41   806.5  691.87     816  689.91   834.9   689.3   853.8  689.66
   882.2  694.59   910.5  698.93   949.4  701.39     969  704.55  1027.9  724.64
  1067.1  736.76  1106.4  752.31  1165.2  773.78  1204.4  784.47  1282.9   797.6
  1302.5  801.81    1381  824.05  1488.9  849.34  1528.1  855.06    1636  867.12
#Mann= 3 , 0 , 0
       0     .05       0     797    .045       0   882.2     .06       0
Bank Sta=797,882.2
XS Rating Curve= 0 ,0
Exp/Cntr=0.3,0.1

Type RM Length L Ch R = 1 ,49615   ,77.4,74.4,71.8
XS GIS Cut Line= 4
     1871741.966      667695.779     1872217.227      668275.641
     1872249.779      668442.741     1872435.109      669001.335
#Sta/Elev= 30
       0  776.13     185  753.36   301.8  742.61     370  734.77   389.5   733.7
   486.8  734.96   632.9  723.44   652.4  718.14   671.8  708.54   691.3  702.72
   768.7  698.92   778.1  697.99   787.6   694.2     797  690.57     816   689.3
   853.8   690.4   872.7  694.74   891.6  699.53     920  703.62   949.4  711.92
   978.8  723.41  1018.1  744.79  1057.3  761.54  1096.5  773.66  1145.6  784.81
  1224.1  809.57  1253.5  816.58    1381  840.42  1439.9  853.25  1508.5  864.24
#Mann= 3 , 0 , 0
       0     .05       0   787.6    .045       0   872.7     .06       0
Bank Sta=787.6,872.7
XS Rating Curve= 0 ,0
Exp/Cntr=0.3,0.1

Type RM Length L Ch R = 1 ,49540.5 ,383.3,402.2,420.2
XS GIS Cut Line= 4
     1871716.793      667703.592      1872133.46      668285.189
     1872188.804      668457.674     1872361.758      668958.366
#Sta/Elev= 30
       0  772.82    78.4  762.02   137.2  755.06   284.2  741.02     392  728.63
   411.6  727.76   460.6  730.11   499.8  729.86   519.4  726.91   578.2  713.83
     637  702.84   656.6  701.28     744  698.58   753.6  697.51   772.6  691.05
   791.7   689.3   820.3  690.25   839.4  697.62   877.5   705.5   935.8  721.99
   955.4  731.72  1014.3  766.16  1033.9  776.14  1073.2  791.67  1112.4  803.31
  1161.5  814.53  1200.7  826.89  1220.3  831.74  1308.6  843.55  1426.3   862.2
#Mann= 3 , 0 , 0
       0     .05       0   753.6    .045       0   839.4     .07       0
Bank Sta=753.6,839.4
XS Rating Curve= 0 ,0
Exp/Cntr=0.3,0.1

Type RM Length L Ch R = 1 ,49138.3 ,400.8,400,401.7
XS GIS Cut Line= 4
     1871684.241      667694.911     1871851.341      668109.408
     1871784.423      668227.732     1871630.221      668521.272
#Sta/Elev= 30
       0  772.02    48.6  762.19    97.2  753.89   155.4  745.22     272  729.98
   349.8  716.76   388.6  713.94   427.5  709.98   446.9  707.56     476  701.86
   534.3  696.94     544  693.02   553.7  690.21   573.1   689.3   592.6   689.7
   602.4  692.32  607.37694.8306   612.1  697.22   641.4   704.9   680.4  717.23
   699.9  724.66   738.9  745.03   777.9  767.31   787.6  773.54   826.7  802.83
   846.2  815.04   865.7  826.26   875.4  830.75   885.2  833.97   914.4  842.21
#Mann= 3 , 0 , 0
       0     .06       0   534.3    .045       0  607.37      .1       0
Bank Sta=534.3,607.37
XS Rating Curve= 0 ,0
Exp/Cntr=0.3,0.1

Type RM Length L Ch R = 1 ,48738.3 ,373.1,371.3,367.6
XS GIS Cut Line= 3
     1871632.157       667671.04     1871465.808      667986.954
     1871259.333      668315.416
#Sta/Elev= 30
       0  772.85   106.2  734.37   154.4  714.68     164  711.13   173.7   708.6
   183.3  707.39   250.9  703.09   299.1   697.3   308.8  695.79   318.4  693.23
   328.1  690.53   337.7  689.44   347.4   689.3   366.7   689.3   376.4  690.55
   386.1  694.45   395.8  699.53   405.5  702.65   415.2  706.83   434.6  719.63
   444.3  725.08   492.8   747.4   502.5   751.2   512.2  754.18   580.1  768.09
     648  777.94   667.4  781.24   677.1  783.54   706.2  791.91     745  801.58
#Mann= 3 , 0 , 0
       0     .06       0   318.4    .045       0   386.1      .1       0
Bank Sta=318.4,386.1
XS Rating Curve= 0 ,0
Exp/Cntr=0.3,0.1

Type RM Length L Ch R = 1 ,48367   ,294,279.5,265.2
XS GIS Cut Line= 4
     1871343.529      667438.835     1871241.532      667647.168
     1871181.169      667788.443     1871138.156      668299.996
#Sta/Elev= 30
       0  777.96      58  760.27      87  749.83     116  737.56     174  708.96
   183.6   704.8   193.3  702.81   222.3  700.84   251.2  698.05   260.8  696.73
   270.4  694.13     280  691.15   289.6   689.7   308.8   689.3     328  689.53
   337.6  691.21   347.2   694.7   356.8  697.79   385.6  702.93   414.6  705.96
   443.7  710.62   492.1  714.49   530.9  719.62   559.9  721.15   608.4  725.28
   685.9  738.88   753.7  753.93   802.1  760.94   860.2  775.04     899  783.62
#Mann= 3 , 0 , 0
       0     .05       0   270.4    .045       0   347.2      .1       0
Bank Sta=270.4,347.2
XS Rating Curve= 0 ,0
Exp/Cntr=0.3,0.1

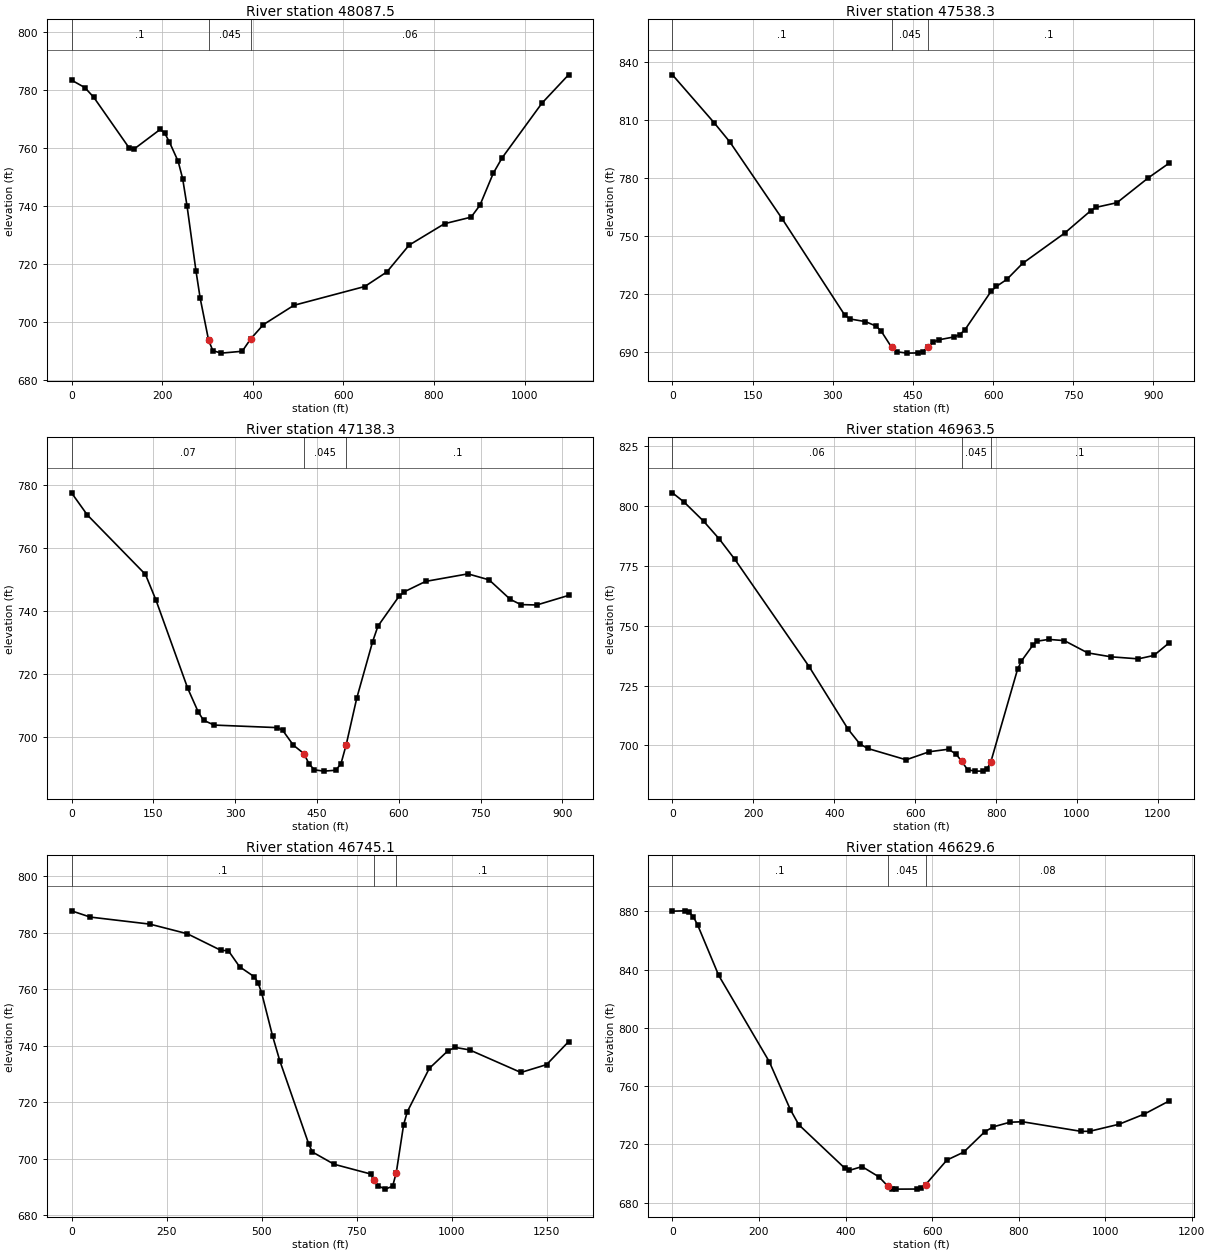
Type RM Length L Ch R = 1 ,48087.5 ,558.9,549.2,538.9
XS GIS Cut Line= 4
     1870881.289      667234.842     1870946.394      667501.769
     1870985.456      667664.529     1871050.363      668316.358
#Sta/Elev= 30
       0  783.43    29.4  780.85    49.1  777.51   127.6  759.96   137.4  759.58
   196.2  766.48   206.1  765.04   215.9  762.15   235.5  755.38   245.3  749.49
   255.1  739.96   274.8  717.59     284  708.26   302.6  693.74     312  690.15
   330.6   689.3   376.8  689.94   395.6  694.21   423.5  699.12     491  705.79
   647.4  712.27   696.3  717.31   745.2  726.53   823.4  733.92   882.1  736.18
   901.6  740.29     931   751.3   950.5  756.61  1038.5  775.48  1097.2  785.25
#Mann= 3 , 0 , 0
       0      .1       0   302.6    .045       0   395.6     .06       0
Bank Sta=302.6,395.6
XS Rating Curve= 0 ,0
Exp/Cntr=0.3,0.1

Type RM Length L Ch R = 1 ,47538.3 ,395.9,400,404.9
XS GIS Cut Line= 3
     1870377.817      667684.061     1870662.302      668018.709
     1870985.141      668388.295
#Sta/Elev= 30
       0  833.18    78.1  808.39   107.4  798.49     205   758.9   322.1  709.11
   331.9  706.97   361.1   705.6   380.7  703.33   390.4  700.78     410  692.36
   419.7  689.99   439.2   689.3   458.9   689.4   468.7  690.14   478.5  692.47
   488.3  695.01   498.1  696.16   527.6  697.71   537.4  698.86   547.2  701.32
   596.3  721.27   606.1  723.77   625.7   727.4   655.2  735.69   733.7   751.3
   782.7  762.92   792.6  764.67   831.8  767.07   890.7  779.97     930  787.63
#Mann= 3 , 0 , 0
       0      .1       0     410    .045       0   478.5      .1       0
Bank Sta=410,478.5
XS Rating Curve= 0 ,0
Exp/Cntr=0.3,0.1

Type RM Length L Ch R = 1 ,47138.3 ,178.8,174.8,170.3
XS GIS Cut Line= 3
     1870175.929      667886.648     1870389.207       668288.67
     1870594.287      668696.061
#Sta/Elev= 30
       0  777.59      29  770.57   135.6  751.69   154.9  743.52     213  715.59
   232.4  708.04   242.1  705.44   261.4  703.91   377.6   703.1   387.3   702.2
   406.7  697.54     426  694.87   435.7  691.52   445.4   689.7   462.6   689.3
   484.2  689.57   493.9  691.59   503.6  697.68     523   712.5   552.1  730.42
   561.8  735.31   600.7  744.83   610.4  746.22   649.2  749.49   726.8  751.88
   765.6  749.98   804.4  743.79   823.8  742.13     853  742.01   911.2  745.04
#Mann= 3 , 0 , 0
       0     .07       0     426    .045       0   503.6      .1       0
Bank Sta=426,503.6
XS Rating Curve= 0 ,0
Exp/Cntr=0.3,0.1

Type RM Length L Ch R = 1 ,46963.5 ,226.6,218.4,210.2
XS GIS Cut Line= 5
     1869694.223      667870.693     1870063.147      668150.641
     1870169.069      668285.985     1870297.522       668450.12
     1870544.918      668745.259
#Sta/Elev= 30
       0  805.48    28.9  801.61    77.2  793.61   115.8  786.21   154.4  777.68
   337.7  732.97   434.2  706.81   463.1   700.7   482.2  698.79   577.7  694.03
     635   697.4   682.4  698.44   701.3  696.36  714.87693.4216   729.7  689.86
   748.7   689.3   767.6  689.31   777.1  690.09   786.6  692.92     853  731.76
   862.7  735.28   891.5     742   901.2  743.54     930  744.29   968.6  743.79
  1026.3  738.67  1084.1  737.02  1151.5  736.17    1190  737.59  1228.5  742.96
#Mann= 3 , 0 , 0
       0     .06       0  714.87    .045       0   786.6      .1       0
Bank Sta=714.87,786.6
XS Rating Curve= 0 ,0
Exp/Cntr=0.3,0.1

Type RM Length L Ch R = 1 ,46745.1 ,130.3,115.5,102.2
XS GIS Cut Line= 5
     1869305.769      668311.231     1869768.008      668404.547
     1870005.862      668473.709     1870143.442      668562.967
     1870521.046      668756.109
#Sta/Elev= 30
       0   787.8    49.1  785.59   206.3  783.09   304.6  779.69     393  773.81
   412.6  773.68   442.1  768.01   481.1  764.43   490.6  762.39   500.2  758.72
   528.7  743.59   547.8  734.76     624  705.26   633.5  702.45   690.7   698.1
   786.8  694.66   796.4  692.57   806.1  690.47   825.4   689.3   844.7  690.33
   854.3  695.15   873.6   712.1   883.3   716.7   941.1  732.03   989.3  738.16
  1008.6  739.47  1047.1  738.58  1182.1  730.59  1249.6  733.36  1307.4  741.48
#Mann= 3 , 0 , 0
       0      .1       0   796.4    .045       0   854.3      .1       0
Bank Sta=796.4,854.3
XS Rating Curve= 0 ,0
Exp/Cntr=0.3,0.1

Type RM Length L Ch R = 1 ,46629.6 ,91,93.4,92.7
XS GIS Cut Line= 4
     1869440.317      668552.116     1869848.303      668575.988
     1870071.828       668606.37     1870549.258      668797.342
#Sta/Elev= 30
       0   880.1    29.2  880.33    38.9  879.34    48.6  876.11    58.4  870.53
     107  835.97   223.8   776.8   272.5  743.88   291.9  733.54     399  703.48
   408.7  702.16   438.1  704.76   477.3   697.7     497  691.56   506.8  689.54
   516.6   689.3   565.6  689.36   575.4  689.98   585.2  692.45   634.3  709.26
   673.1  714.69   721.6  728.64     741  732.01   779.8  735.23   808.9  735.54
   944.7  728.94   964.1     729    1032  733.83  1090.3   740.8  1148.5  749.93
#Mann= 3 , 0 , 0
       0      .1       0     497    .045       0   585.2     .08       0
Bank Sta=497,585.2
XS Rating Curve= 0 ,0
Exp/Cntr=0.3,0.1

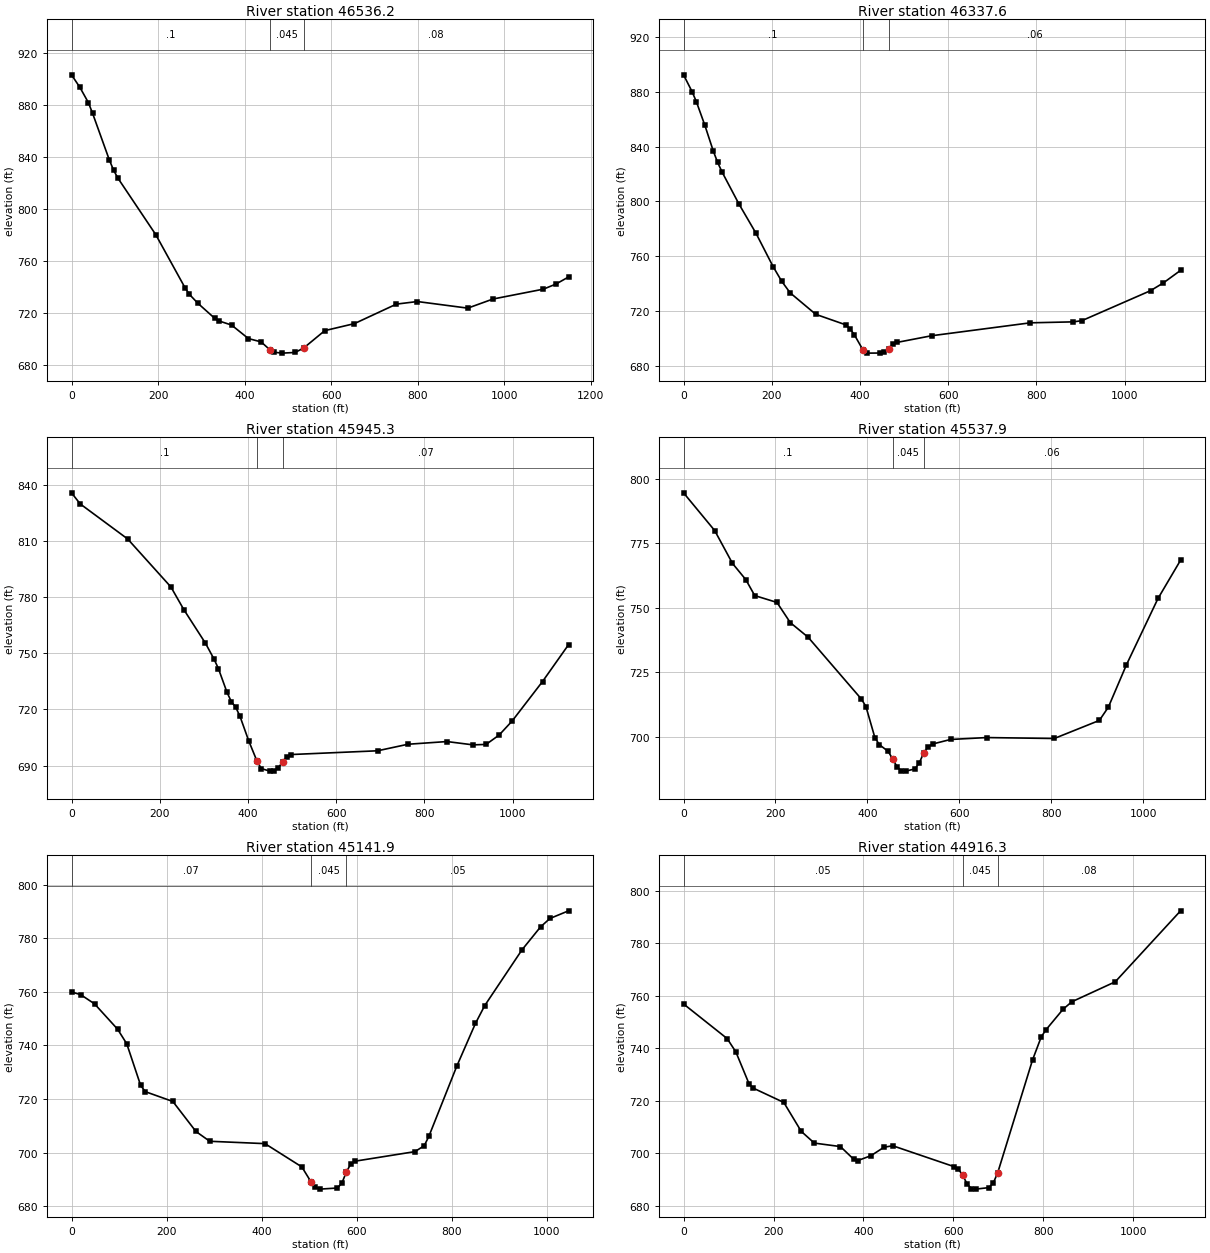
Type RM Length L Ch R = 1 ,46536.2 ,197.2,198.6,201.5
XS GIS Cut Line= 4
     1869433.807       668617.22     1869841.793      668641.092
     1870065.317      668671.474     1870542.748      668862.446
#Sta/Elev= 30
       0  902.92    19.5  893.22    38.9  881.64    48.6  873.45    87.6   837.4
    97.3  829.67     107  823.72   194.6  780.29   262.7  739.23   272.5  734.37
   291.9  727.59   330.8  716.04   340.6  714.02   369.8  710.86   408.7  700.48
   438.1  697.92   457.7  692.07   467.5  689.98   487.2   689.3   516.6  689.81
   536.2  693.14   585.2  706.57   653.7  711.95   750.7  726.92   799.2   728.9
   915.6  723.83   973.8  730.82  1090.3   738.4  1119.4  742.32  1148.5  747.75
#Mann= 3 , 0 , 0
       0      .1       0   457.7    .045       0   536.2     .08       0
Bank Sta=457.7,536.2
XS Rating Curve= 0 ,0
Exp/Cntr=0.3,0.1

Type RM Length L Ch R = 1 ,46337.6 ,404.3,392.3,380.5
XS GIS Cut Line= 4
     1869432.023      668816.307      1869789.71      668827.724
     1869935.707      668835.538     1870557.071      668879.807
#Sta/Elev= 30
       0  892.41    19.3  880.16      29  872.86    48.4   855.5    67.7  836.53
    77.4  828.43      87  821.68   125.7  798.09   164.4  776.71   203.1  752.42
   222.5  741.78   241.8  733.28   299.8  717.62   367.6  709.98   377.4  707.11
   387.1  702.79   406.6  691.77   416.4   689.3   445.6  689.37   455.3  690.15
   465.1  692.59   474.8   695.6   484.6  697.16   562.5  701.99   786.3  711.42
   883.7  712.12   903.1  712.97  1058.9  734.88  1088.1  740.57    1127   749.7
#Mann= 3 , 0 , 0
       0      .1       0   406.6    .045       0   465.1     .06       0
Bank Sta=406.6,465.1
XS Rating Curve= 0 ,0
Exp/Cntr=0.3,0.1

Type RM Length L Ch R = 1 ,45945.3 ,416.1,407.4,398.5
XS GIS Cut Line= 4
     1869576.168      669404.113     1869930.335      669214.877
     1870041.446      669157.585     1870584.848      668902.377
#Sta/Elev= 30
       0  835.59    19.6  829.69   127.3  810.97   225.3  785.38   254.6   773.3
   303.6  755.39   323.2  746.85     333  741.85   352.6  729.11   362.4  724.15
   372.2  721.25     382  716.33   401.6  703.37   420.8  692.29   430.4  688.47
   449.6  687.11   459.2  687.32   468.9  688.89   478.5  692.02   488.1  694.81
   497.7  695.96   693.9  697.96   762.8  701.45   851.3  702.89   910.4  701.12
   939.9  701.36   969.4  706.33     999  713.84  1067.9  734.91  1126.9  754.56
#Mann= 3 , 0 , 0
       0      .1       0   420.8    .045       0   478.5     .07       0
Bank Sta=420.8,478.5
XS Rating Curve= 0 ,0
Exp/Cntr=0.3,0.1

Type RM Length L Ch R = 1 ,45537.9 ,390.2,395.9,401.8
XS GIS Cut Line= 4
     1869968.529      669787.793     1870266.272      669456.673
     1870341.402      669368.164     1870680.335      668973.557
#Sta/Elev= 30
       0  794.49    67.8  779.86   106.5  767.13   135.5  760.84   154.9  754.66
   203.3     752   232.3  744.18     271  738.53   387.2  714.51   396.9  711.65
   416.3  699.64   425.9   696.9   445.3  694.26     455  691.36   464.6  688.31
   474.3  686.68     484  686.61   503.4  687.48     513  689.78   522.7  693.74
   532.4  696.05     542  697.12     581  698.88   659.5  699.62   806.8  699.26
   904.9  706.27   924.5  711.42   963.8  727.82  1032.5  753.54  1081.6  768.37
#Mann= 3 , 0 , 0
       0      .1       0     455    .045       0   522.7     .06       0
Bank Sta=455,522.7
XS Rating Curve= 0 ,0
Exp/Cntr=0.3,0.1

Type RM Length L Ch R = 1 ,45141.9 ,213.6,225.7,237.4
XS GIS Cut Line= 4
     1870091.359      669907.628     1870551.428      669701.465
     1870650.731      669632.867     1870874.779      669276.118
#Sta/Elev= 30
       0  759.96    19.4  758.93    48.5   755.5      97  746.05   116.3   740.6
   145.4  725.15   155.1  722.77   213.3  719.09   261.8  707.92   290.9  704.25
   407.2  703.37   484.8  694.68   504.2  689.07   513.4  687.06   522.7   686.4
   559.8  686.82   569.1  688.67   578.4  692.76   587.7  695.78     597  696.83
   722.8  700.39   742.4   702.6   752.2  706.12     811  732.31   850.2  748.22
   869.8  754.89   948.1  775.65   987.3  784.24  1006.9  787.35  1046.1  790.21
#Mann= 3 , 0 , 0
       0     .07       0   504.2    .045       0   578.4     .05       0
Bank Sta=504.2,578.4
XS Rating Curve= 0 ,0
Exp/Cntr=0.3,0.1

Type RM Length L Ch R = 1 ,44916.3 ,179,182.6,185.5
XS GIS Cut Line= 4
     1870073.998      669951.031     1870551.428      669868.566
     1870803.164      669846.864     1871167.748      669799.121
#Sta/Elev= 30
       0   756.9    96.9  743.72   116.3  738.64   145.4  726.59     155  724.85
   222.9   719.4   261.6   708.4   290.7  703.93   348.8   702.6   377.9  697.82
   387.6  697.28   416.7  699.14   445.7  702.36   465.1  702.91   601.1  694.98
   610.8  694.06   620.6  691.68   630.3  688.38     640  686.58   649.7   686.4
   678.9  686.98   688.6  688.76   698.3  692.58   775.9  735.63   795.2  744.36
   804.9   746.9   843.6  754.87     863  757.72   959.7  765.34  1104.9  792.36
#Mann= 3 , 0 , 0
       0     .05       0   620.6    .045       0   698.3     .08       0
Bank Sta=620.6,698.3
XS Rating Curve= 0 ,0
Exp/Cntr=0.3,0.1

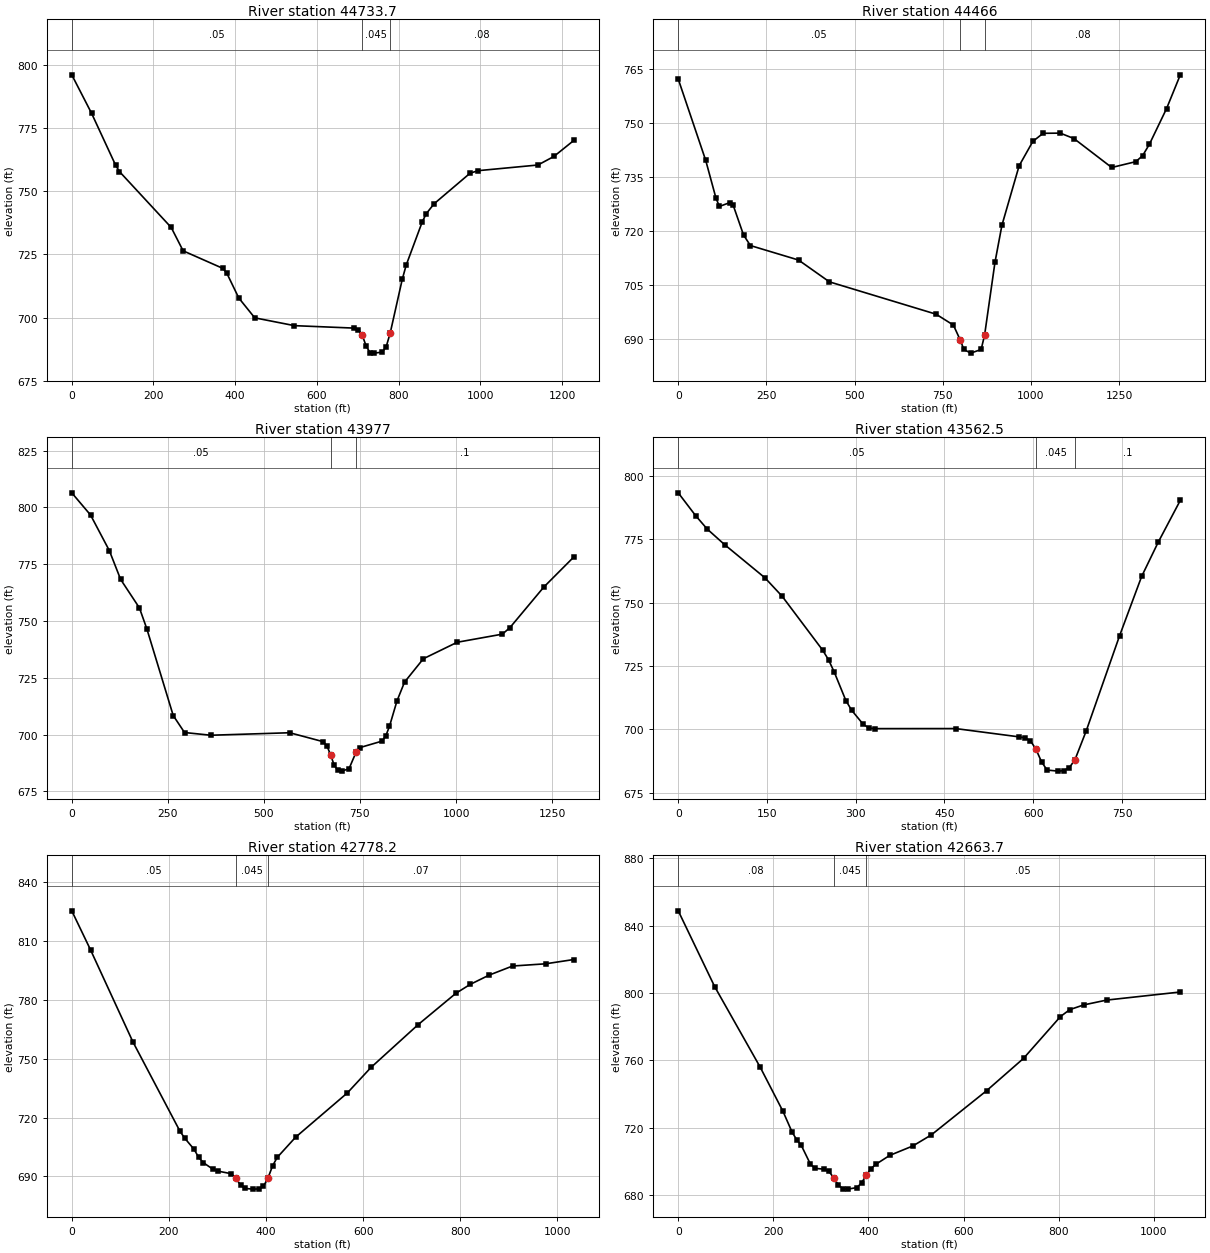
Type RM Length L Ch R = 1 ,44733.7 ,270.4,267.6,265.3
XS GIS Cut Line= 4
     1869924.258      670003.114     1870566.674      670018.293
     1870761.932      670031.326     1871152.557      670037.837
#Sta/Elev= 30
       0  796.02    48.7  780.74   107.1  760.37   116.8  757.76   243.4  735.68
   272.6  726.44     370  719.49   379.7  717.53   408.9  707.78   447.9  699.95
   545.2  696.86   691.5  695.89   701.3  695.34   711.1  693.05   720.9  688.67
   730.7  686.06   740.4     686     760   686.4   769.8   688.6   779.6  694.03
   808.9  715.13   818.7  720.84   857.8  737.85   867.6   741.1   887.1  745.07
     975  757.13   994.6  758.13  1141.1  760.37  1180.1  763.74    1229  770.09
#Mann= 3 , 0 , 0
       0     .05       0   711.1    .045       0   779.6     .08       0
Bank Sta=711.1,779.6
XS Rating Curve= 0 ,0
Exp/Cntr=0.3,0.1

Type RM Length L Ch R = 1 ,44466   ,488.7,489,489.3
XS GIS Cut Line= 4
     1869815.751      670495.736     1870475.473      670287.403
     1870720.699      670276.552      1871206.81      670267.871
#Sta/Elev= 30
       0   762.3      78  739.63   107.2  729.07   116.9  726.84   146.2  727.91
   155.9  727.15   185.1   718.9   204.6  715.95     341  711.92   428.7  705.84
   731.1  696.84   780.2   693.8   799.8   689.6   809.7  687.03   829.3     686
   858.8  687.02   868.6  691.02     898  711.28   917.7  721.59   966.5  738.16
  1005.4  744.95  1034.5   747.2  1083.2  747.25    1122  745.73    1229  737.68
  1297.1   739.3  1316.5  740.95    1336  744.18  1384.6   754.1  1423.5  763.48
#Mann= 3 , 0 , 0
       0     .05       0   799.8    .045       0   868.6     .08       0
Bank Sta=799.8,868.6
XS Rating Curve= 0 ,0
Exp/Cntr=0.3,0.1

Type RM Length L Ch R = 1 ,43977   ,404.1,414.5,424.9
XS GIS Cut Line= 4
     1869834.414      670772.212     1870460.282      670767.003
     1870651.255      670758.323     1871133.026      670671.517
#Sta/Elev= 30
       0  806.43    48.9  796.66    97.8  780.98   127.1  768.33     176  755.78
   195.6  746.43     264  708.38   293.4   700.9   361.8   699.7   567.2   700.8
   654.6  696.85   664.1  695.03   673.7  690.97   683.2   686.4   692.8  684.21
   702.4   683.9   721.5  684.94   740.6  692.54   750.2  694.28   807.5  697.12
   817.1  699.39   826.8  703.63   846.4  714.85     866  723.09     915  733.38
  1003.1  740.64  1120.6  744.21  1140.2  747.07  1228.3  764.91  1306.6   778.2
#Mann= 3 , 0 , 0
       0     .05       0   673.7    .045       0   740.6      .1       0
Bank Sta=673.7,740.6
XS Rating Curve= 0 ,0
Exp/Cntr=0.3,0.1

Type RM Length L Ch R = 1 ,43562.5 ,777.6,784.3,790.5
XS GIS Cut Line= 4
     1869817.053       670902.42     1870355.248      671108.583
     1870500.647      671175.858     1870604.814       671217.09
#Sta/Elev= 30
       0  793.36    29.3  784.38    48.8   779.1    78.2  772.94   146.5  759.82
   175.8  752.48   244.2  731.22     254  727.47   263.7   722.6   283.3  711.38
     293  707.56   312.6  701.99   322.4  700.53   332.1  700.28   468.9   700.3
   576.3  697.02   585.8  696.63   595.2  695.51   604.6  692.14     614  687.19
   623.4  683.92   642.3   683.5   651.7  683.69   661.2  684.93   670.6  688.04
   689.4  699.28   745.9  736.91   783.2  760.33   811.2  773.84   848.6  790.39
#Mann= 3 , 0 , 0
       0     .05       0   604.6    .045       0   670.6      .1       0
Bank Sta=604.6,670.6
XS Rating Curve= 0 ,0
Exp/Cntr=0.3,0.1

Type RM Length L Ch R = 1 ,42778.2 ,121.3,114.5,108.1
XS GIS Cut Line= 4
      1869458.98      671327.767     1869706.376      671514.399
     1869821.394      671612.055     1870376.949      671470.996
#Sta/Elev= 30
       0  825.32    38.7   805.4   125.9  758.54   222.7  713.07   232.4  709.52
   251.8  703.82   261.5  699.62   271.2  696.95   290.5  693.67   300.2  692.72
   328.8  691.34   338.2  688.93   347.6  685.56     357  683.85   373.4   683.5
   385.3  683.63   394.8  684.91   404.2  689.21   413.6  695.39   423.1  699.66
   460.8  709.92   567.6  732.54   616.2   745.5   713.4  767.34   791.1   783.3
   820.2  787.78   859.1  792.51   907.7  797.19   975.7  798.32    1034  800.51
#Mann= 3 , 0 , 0
       0     .05       0   338.2    .045       0   404.2     .07       0
Bank Sta=338.2,404.2
XS Rating Curve= 0 ,0
Exp/Cntr=0.3,0.1

Type RM Length L Ch R = 1 ,42663.7 ,64.6,64.6,64.6
XS GIS Cut Line= 4
     1869357.852      671490.094     1869618.269      671611.621
     1869807.071      671694.087     1870353.078      671559.972
#Sta/Elev= 30
       0  848.73    76.6  803.73   172.4  755.86   220.3  729.63   239.5  717.27
   249.1  712.82   258.6  709.53   277.8  698.41   287.4  695.85     307  695.33
   316.8  694.02   326.6  690.38   336.4  686.01   346.2  683.75     356   683.5
   375.7  684.41   385.5  687.28   395.3  691.63   405.1  695.59   414.9  698.13
   444.4  703.49   493.4  709.15   532.2  715.71   648.5  741.98     726  761.13
   803.6  785.95     823  790.04   852.1  792.84   900.5  795.73  1055.6  800.54
#Mann= 3 , 0 , 0
       0     .08       0   326.6    .045       0   395.3     .05       0
Bank Sta=326.6,395.3
XS Rating Curve= 0 ,0
Exp/Cntr=0.3,0.1

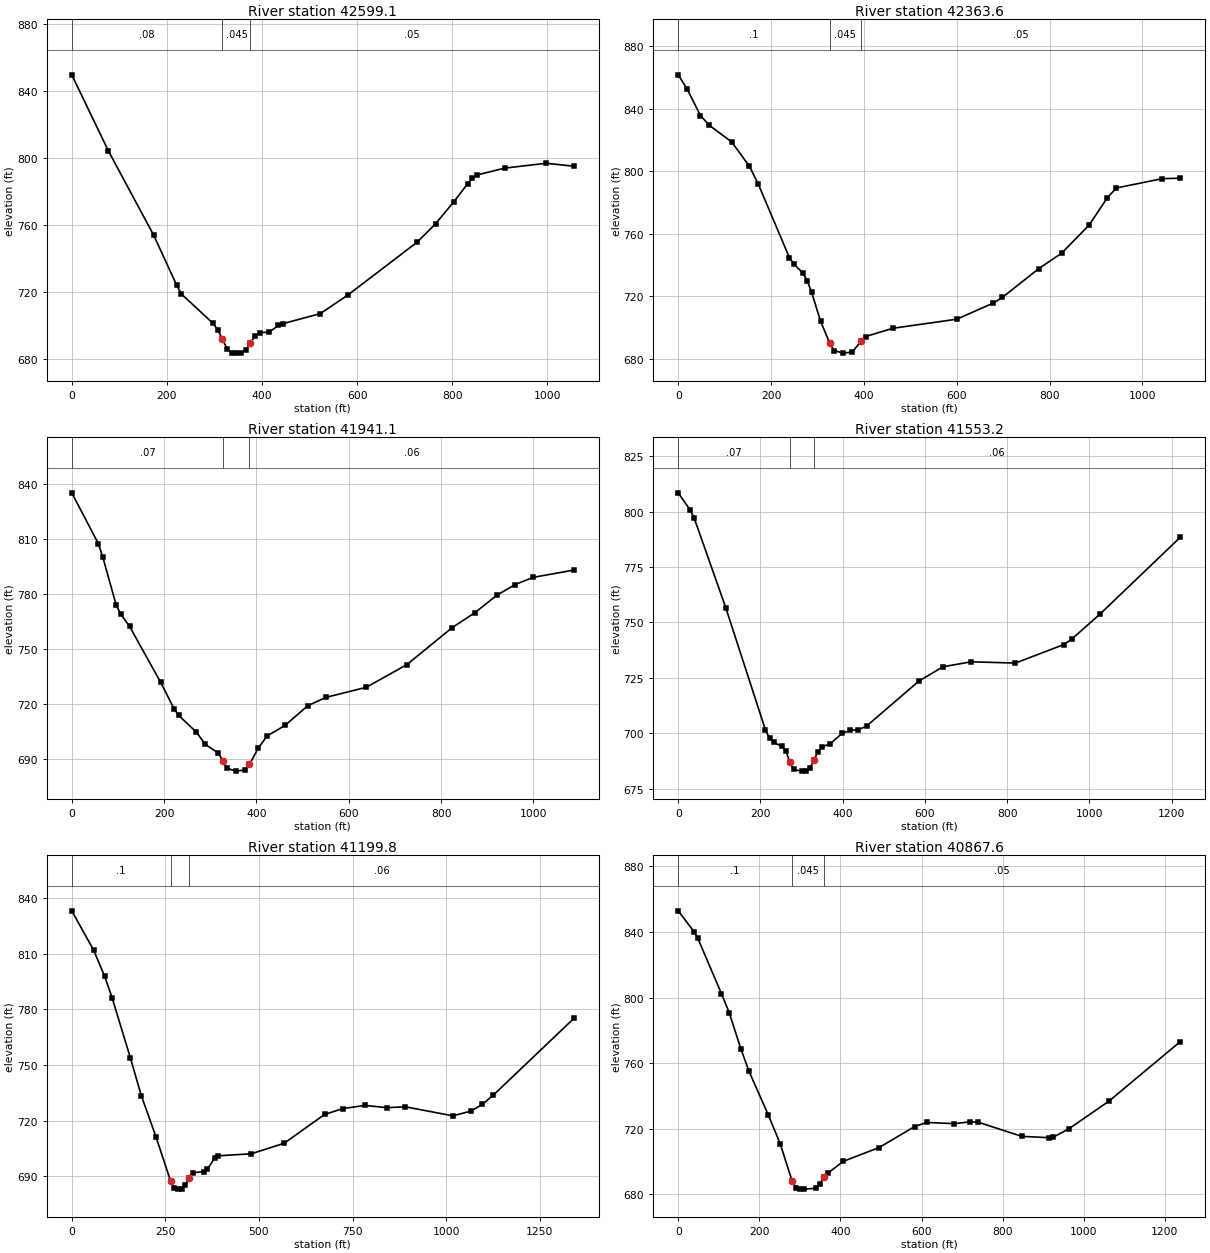
Type RM Length L Ch R = 1 ,42599.1 ,251.8,235.5,219.1
XS GIS Cut Line= 4
     1869340.491      671553.028     1869600.907      671674.555
      1869789.71      671757.021     1870335.716      671622.906
#Sta/Elev= 30
       0   849.8    76.6  804.56   172.4  753.87   220.3  724.26   229.9  718.99
   297.2  701.24     307  697.39   316.8  691.75   326.6  686.15   336.4  683.83
   346.2   683.5     356  683.75   365.9  685.45   375.7   689.6   385.5  693.98
   395.3  695.74   414.9  696.05   434.5  700.02   444.4  701.15   522.5  707.11
   580.6  718.24     726  749.78   764.8  760.78   803.6  774.04   832.7  784.86
   842.4     788   852.1  789.95   910.2  794.06   997.5  796.95  1055.6  795.19
#Mann= 3 , 0 , 0
       0     .08       0   316.8    .045       0   375.7     .05       0
Bank Sta=316.8,375.7
XS Rating Curve= 0 ,0
Exp/Cntr=0.3,0.1

Type RM Length L Ch R = 1 ,42363.6 ,432.9,422.4,411.9
XS GIS Cut Line= 4
     1869262.366      671997.906     1869571.828      671933.236
     1869748.496       671876.45     1870284.501      671655.024
#Sta/Elev= 30
       0  861.66    19.2  852.56    47.9  835.56    67.1  829.31     115  818.73
   153.3  803.19   172.4  791.73   239.5  744.66   249.1  740.46   268.2  734.96
   277.8  729.94   287.4   722.4   306.6  703.94   325.9  690.26   335.7  685.16
   355.2   683.5   374.8  684.16   394.3  691.23     404  694.14   462.6  699.41
     600  705.22   678.6  715.52   698.3  719.16   776.9  737.64   826.1   747.5
   885.1  765.44   924.4  782.94     944  789.23  1042.3  795.16  1081.7  795.51
#Mann= 3 , 0 , 0
       0      .1       0   325.9    .045       0   394.3     .05       0
Bank Sta=325.9,394.3
XS Rating Curve= 0 ,0
Exp/Cntr=0.3,0.1

Type RM Length L Ch R = 1 ,41941.1 ,392.2,387.9,383.5
XS GIS Cut Line= 4
     1869620.873      672490.962     1869820.071      672281.452
     1869922.956      672181.066     1870316.185      671657.628
#Sta/Elev= 30
       0  835.15    57.8  807.35    67.4  799.98    96.4  773.83     106   769.1
   125.3  762.31   192.7  731.82   221.6  717.48   231.3   713.9   269.8  704.77
   289.1  698.13   317.8  693.24   327.4  689.06     337  684.95   356.2   683.5
   375.3  684.13   384.9  687.14   404.1  696.14   423.2  702.67   462.2  708.45
     511  719.11   550.1  723.65     638  729.19     726  741.56   823.7  761.66
   872.6  769.72   921.4  779.46   960.5  785.18   999.6   789.1  1087.5  793.05
#Mann= 3 , 0 , 0
       0     .07       0   327.4    .045       0   384.9     .06       0
Bank Sta=327.4,384.9
XS Rating Curve= 0 ,0
Exp/Cntr=0.3,0.1

Type RM Length L Ch R = 1 ,41553.2 ,366.2,353.4,340.6
XS GIS Cut Line= 4
     1869962.019      672774.816     1870068.789      672602.941
     1870215.417      672393.558     1870386.498      671649.816
#Sta/Elev= 30
       0  808.42    28.9  800.73    38.5  797.19   115.6  756.66   212.2  701.53
     222  697.78   231.8  695.96   251.5  694.24   261.3  692.28   271.2  687.31
     281  683.77   300.3  683.01   310.5  683.13   320.3   684.4   330.2  687.98
     340  691.85   349.8  693.95   369.5  695.31     399   700.1   418.6  701.35
   438.3  701.71     458   703.3   585.2  723.59   643.9  730.03   712.4  732.28
     820   731.7   937.4  740.02     957  742.48  1025.4  753.71  1221.1   788.4
#Mann= 3 , 0 , 0
       0     .07       0   271.2    .045       0   330.2     .06       0
Bank Sta=271.2,330.2
XS Rating Curve= 0 ,0
Exp/Cntr=0.3,0.1

Type RM Length L Ch R = 1 ,41199.8 ,349,332.2,316
XS GIS Cut Line= 3
     1870408.633      672978.809     1870421.654      672646.778
     1870462.019      671638.965
#Sta/Elev= 30
       0  833.28    58.6  811.96      88  797.84   107.5  786.47   156.4  753.97
   185.7   733.5   224.8  711.32   263.9  687.36   273.6  683.68   283.4     683
   293.2  683.31     303   685.3   312.7  689.14   322.5  691.82   351.9  692.47
   361.7   693.6   381.2  699.64     391  701.01   479.2  702.07   567.3  707.78
     675  723.31     724  726.49   782.7  728.22   841.5  726.99   890.5  727.46
  1017.8  722.59  1066.7  725.18  1096.1  728.73  1125.5  733.69  1340.9  775.17
#Mann= 3 , 0 , 0
       0      .1       0   263.9    .045       0   312.7     .06       0
Bank Sta=263.9,312.7
XS Rating Curve= 0 ,0
Exp/Cntr=0.3,0.1

Type RM Length L Ch R = 1 ,40867.6 ,586.3,584.7,582.3
XS GIS Cut Line= 4
     1870899.519      672694.521     1870705.074      672534.798
     1870576.602      672388.965     1870496.741      671600.771
#Sta/Elev= 30
       0  852.92    38.7  840.24    48.4  836.07   106.5  802.42   125.8  790.67
   154.8  768.42   174.2  755.12   222.6  727.99   251.6   710.6   280.8  687.99
   290.5  683.99   300.2  683.03   309.9     683   339.1  683.48   348.8     686
   358.5  690.16   368.2  692.58   407.1  699.98   494.9  708.33   582.9  721.19
   612.3  723.69   680.7     723   719.8  724.06   739.4  723.88     847  715.24
   915.5  714.38   925.2  714.76   964.4     720  1062.2  736.72  1238.2  773.09
#Mann= 3 , 0 , 0
       0      .1       0   280.8    .045       0   358.5     .05       0
Bank Sta=280.8,358.5
XS Rating Curve= 0 ,0
Exp/Cntr=0.3,0.1

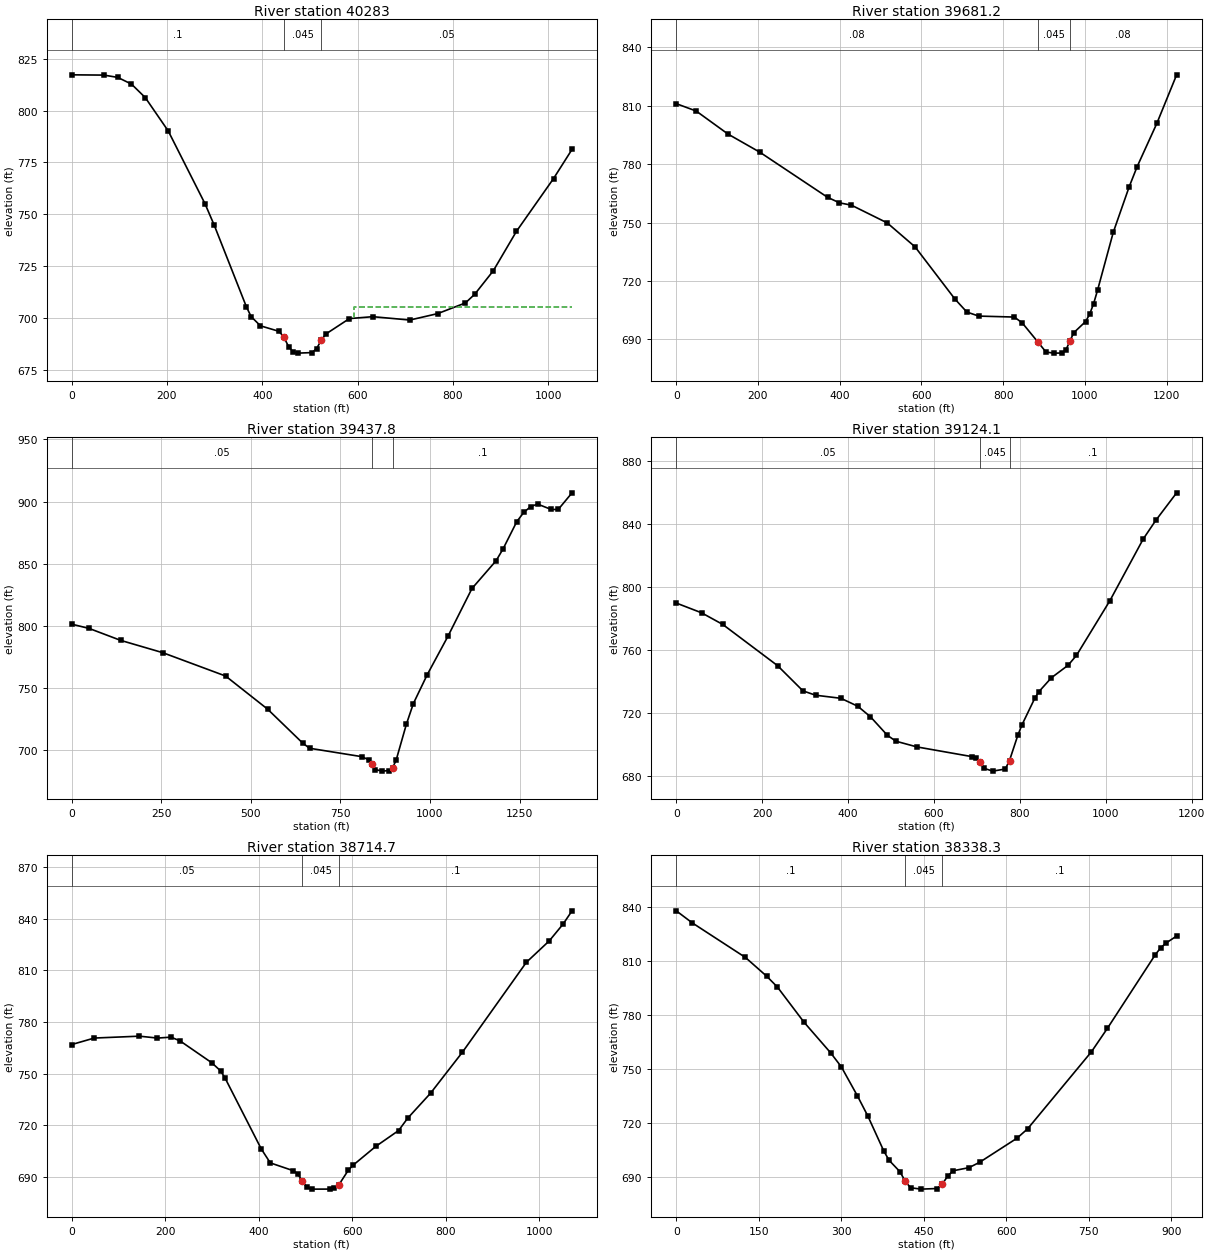
Type RM Length L Ch R = 1 ,40283   ,588.3,601.8,615.3
XS GIS Cut Line= 4
     1871187.713      672326.465     1870972.435      672041.743
     1870777.991      671847.298     1870521.046      671517.437
#Sta/Elev= 30
       0  817.24    67.5  817.11    96.5  816.01   125.4  812.78   154.4  806.27
   202.6  790.17   279.8  755.06   299.1  744.74   366.8  705.27   376.6  700.61
   396.2  696.17   435.5  693.48   445.3  690.68   455.2  686.17     465  683.51
   474.8     683   504.3  683.26   514.1  685.21   523.9   689.3   533.7  692.26
   582.8  699.66   631.9  700.58   709.7  698.96   768.1  702.06   826.4  707.22
   845.9  711.42   884.8  722.72   933.4  741.74  1011.2  767.19  1050.1  781.28
#Mann= 3 , 0 , 0
       0      .1       0   445.3    .045       0   523.9     .05       0
#XS Ineff= 2 , 0
                          591.97          705.05
Permanent Ineff=
       F       F
Bank Sta=445.3,523.9
XS Rating Curve= 0 ,0
Exp/Cntr=0.3,0.1

Type RM Length L Ch R = 1 ,39681.2 ,228.1,243.4,258.7
XS GIS Cut Line= 4
     1871218.963      672295.215     1871087.019      671576.465
     1871031.463      671281.326     1870982.852      671093.826
#Sta/Elev= 30
       0  811.02    48.7  807.25   126.7  795.41   204.6  786.11   370.2  762.98
   399.5  760.13   428.7  758.93   516.4  749.83   584.6  737.52     682  710.78
   711.3  704.08   740.4  702.01   827.6  701.51     847  698.48   885.8  688.55
   905.1  683.54   924.5     683   943.9  683.04   953.6  684.57   963.3  689.06
     973  693.48    1002  699.22  1011.7  702.89  1021.4  708.27  1031.1  715.19
  1069.8  745.07  1108.6  768.34  1127.9  778.59  1176.4  800.92  1224.8  825.82
#Mann= 3 , 0 , 0
       0     .08       0   885.8    .045       0   963.3     .08       0
Bank Sta=885.8,963.3
XS Rating Curve= 0 ,0
Exp/Cntr=0.3,0.1

Type RM Length L Ch R = 1 ,39437.8 ,310.2,313.7,317.1
XS GIS Cut Line= 4
     1871275.387       672315.18     1871205.074      671576.465
     1871343.963      671312.576     1871538.407      671013.965
#Sta/Elev= 30
       0  801.29    48.8  797.83   136.7  788.24   253.9  778.36   429.6  759.54
   546.8  732.89   644.4  705.67   663.9  701.41   809.4  694.66   828.6   692.2
   838.2  688.53   847.9  684.21   867.1     683   886.4  683.48     896   685.9
   905.6  691.82   934.4  720.95   953.7   737.4   992.2  760.52  1049.9  791.36
  1117.3  830.01  1184.7  852.39    1204  861.83  1242.5  883.89  1261.8  891.22
    1281   895.9  1300.3  897.93  1338.8  893.58  1358.1  893.63  1396.6  906.99
#Mann= 3 , 0 , 0
       0     .05       0   838.2    .045       0     896      .1       0
Bank Sta=838.2,896
XS Rating Curve= 0 ,0
Exp/Cntr=0.3,0.1

Type RM Length L Ch R = 1 ,39124.1 ,407.2,409.4,411.6
XS GIS Cut Line= 4
      1871329.64      672347.733     1871468.529      671714.052
     1871584.795      671556.856      1871809.26      671327.924
#Sta/Elev= 30
       0  789.89      59  783.67   108.1   776.3   235.9  750.07   294.9  734.04
   324.4  731.27   383.3  729.31   422.6  724.26   452.1  717.56   491.5  705.79
   511.1  702.05   560.3  698.39   687.8  692.25   697.6  691.25   707.4   688.6
   717.2  684.74   736.7     683     766  684.34   775.8  689.75   795.4  705.97
   805.1  712.59   834.5  729.25   844.2  733.52   873.4  742.39   912.2  750.32
   931.7  756.59  1009.4  791.33  1087.1  830.61  1116.3  842.44  1164.9  859.98
#Mann= 3 , 0 , 0
       0     .05       0   707.4    .045       0   775.8      .1       0
Bank Sta=707.4,775.8
XS Rating Curve= 0 ,0
Exp/Cntr=0.3,0.1

Type RM Length L Ch R = 1 ,38714.7 ,380.1,376.4,372.6
XS GIS Cut Line= 4
     1871418.931      672377.809     1871687.713      672048.687
     1871852.085      671866.787     1872117.401      671566.917
#Sta/Elev= 30
       0   766.9    48.3  770.67   144.9  771.76   183.5  770.66   212.5  771.19
   231.8  769.03   299.4  756.39   318.7   751.6   328.4  747.32   405.6  706.32
   424.9  698.23     474   693.7   483.8  691.87   493.6  687.47   503.4  684.09
   513.2     683   552.4  683.02   562.2  683.53     572  685.68   591.6  693.89
   601.4  696.74   650.5  707.78   699.4     717   718.9  724.17   767.8  738.67
   836.1  762.51   972.8  814.63  1021.7  827.05    1051  836.69  1070.5   844.5
#Mann= 3 , 0 , 0
       0     .05       0   493.6    .045       0     572      .1       0
Bank Sta=493.6,572
XS Rating Curve= 0 ,0
Exp/Cntr=0.3,0.1

Type RM Length L Ch R = 1 ,38338.3 ,400.8,400,399.2
XS GIS Cut Line= 3
     1871792.662      672601.607     1872037.389      672218.027
     1872282.115      671834.446
#Sta/Elev= 30
       0  837.81      29  831.13   125.8  811.87   164.6  801.39   183.9  795.43
   232.3  775.86   280.7  758.84   300.1  751.07   329.2  735.03   348.5   723.6
   377.6  704.08   387.2  698.99   406.6  692.76   416.3  687.49     426  683.76
   445.3     683   474.4  683.34     484  685.89   493.7  690.26   503.4  693.21
   532.4  694.95   551.8  697.95   619.6  711.31   638.9  716.52   755.1  759.42
   784.2  772.49   871.3  813.46     881  817.24   890.6  819.85     910   823.8
#Mann= 3 , 0 , 0
       0      .1       0   416.3    .045       0     484      .1       0
Bank Sta=416.3,484
XS Rating Curve= 0 ,0
Exp/Cntr=0.3,0.1