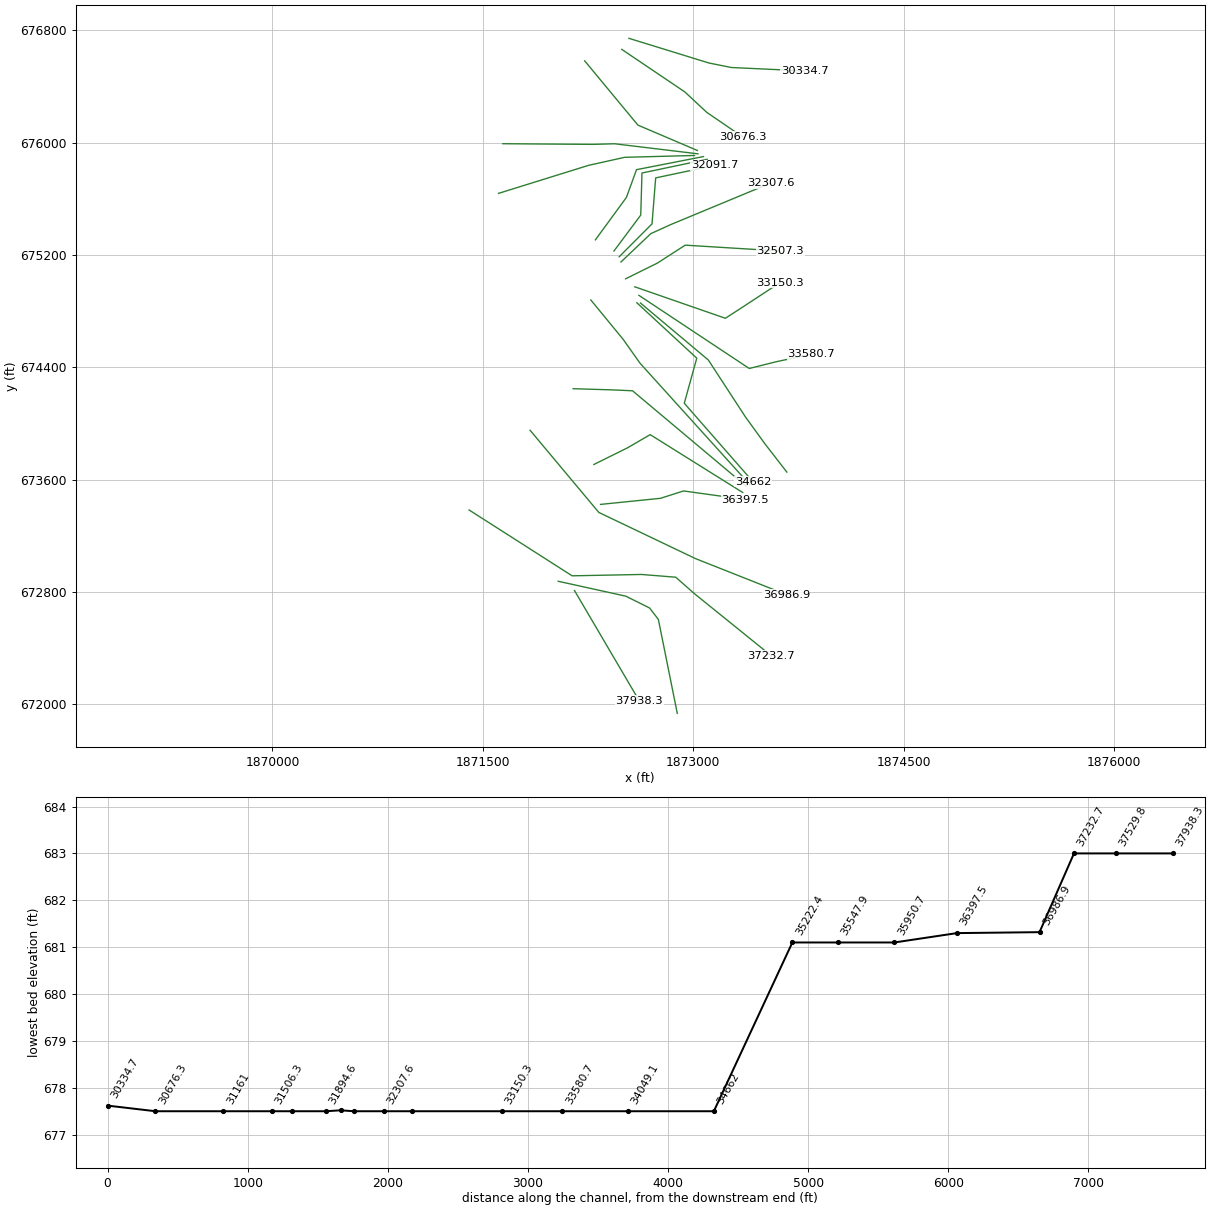
HEC-RAS study SpringCrk2.prj: SpringCrk2

--- SpringCrk2.g01 (geometry) --- (continued)

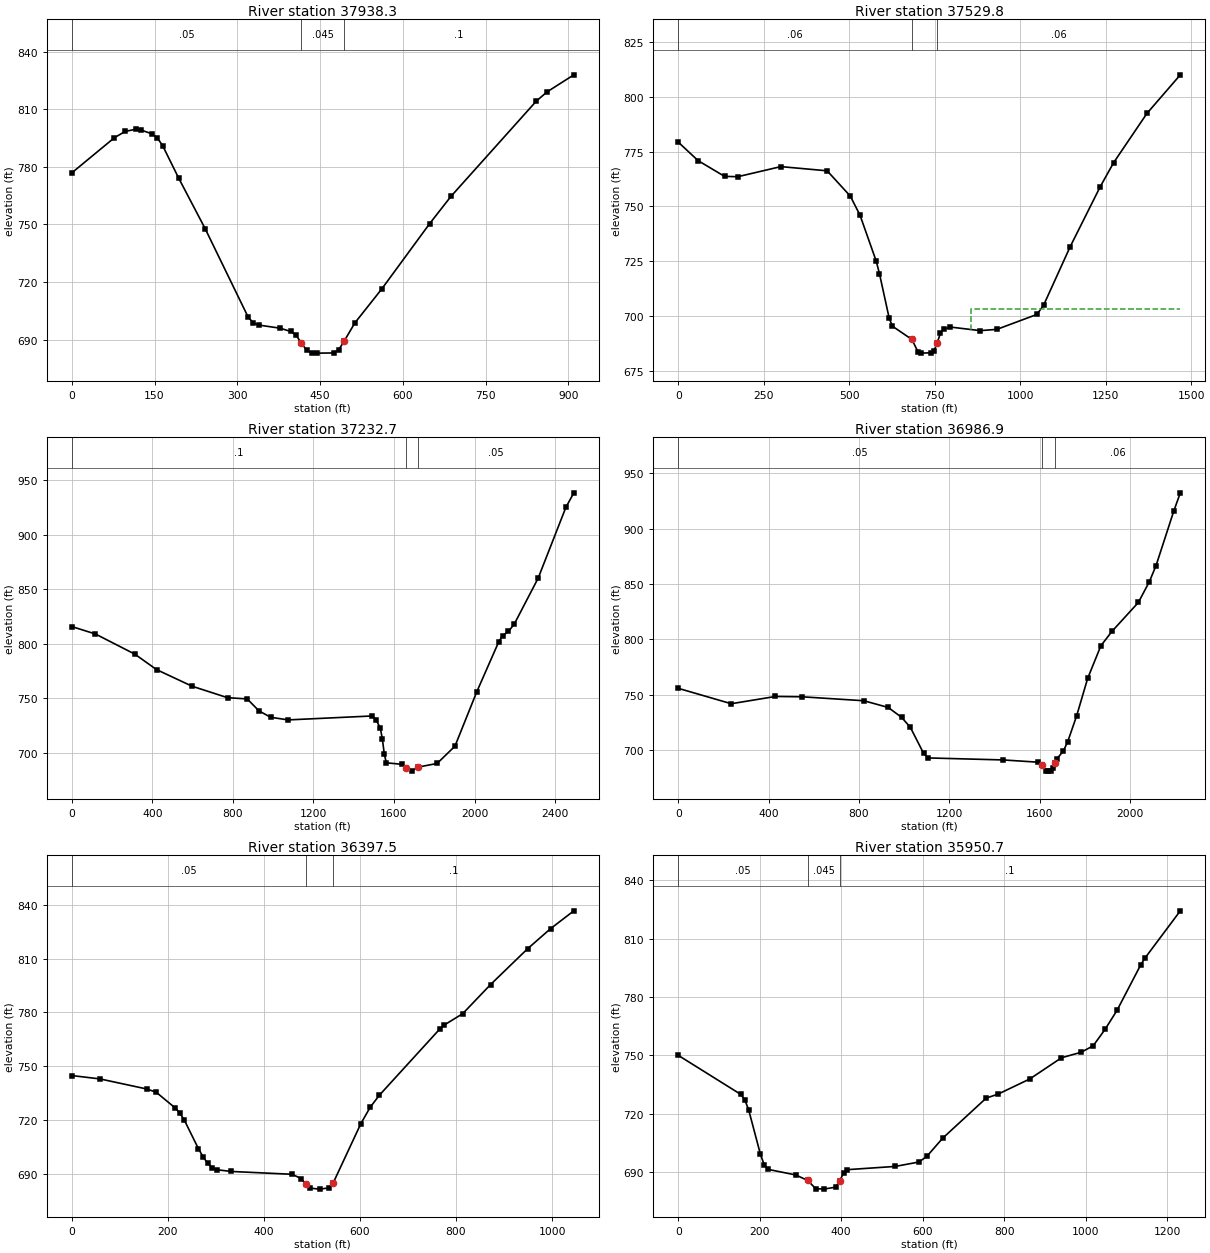
Type RM Length L Ch R = 1 ,37938.3 ,405.7,408.5,411.3
XS GIS Cut Line= 3
     1872153.896      672809.031     1872384.434      672416.759
     1872614.972      672024.488
#Sta/Elev= 30
       0  776.81    77.4  795.16    96.8  798.39   116.2  799.55   125.8  799.11
   145.2  797.14   154.9  795.11   164.6  791.06   193.6  774.18     242  747.65
   319.5  701.86   329.2  698.69   338.8  697.61   377.6  695.98   396.9  694.26
   406.6  692.32   416.3  688.16     426  684.42   435.6  683.04   445.3     683
   474.4  683.09     484  684.81   493.7  689.24   513.1  698.73   561.5  716.27
   648.6  750.38   687.3   764.6   842.2  814.25   861.6  819.01     910  827.86
#Mann= 3 , 0 , 0
       0     .05       0   416.3    .045       0   493.7      .1       0
Bank Sta=416.3,493.7
XS Rating Curve= 0 ,0
Exp/Cntr=0.3,0.1

Type RM Length L Ch R = 1 ,37529.8 ,292.7,297.1,301.4
XS GIS Cut Line= 5
     1872037.948      672875.215     1872519.984      672768.978
     1872689.601      672684.553     1872751.775      672603.492
      1872886.65      671934.119
#Sta/Elev= 30
       0  779.41    58.1  770.95   135.5  763.76   174.2  763.61     300  768.22
   435.5   766.3   503.1  754.75   531.5  746.03   578.9  725.04   588.3  719.37
   616.8  698.99   626.2  695.31   683.1  689.26   701.6  683.44   710.9     683
   738.8  683.16   748.1  684.14   757.4  687.81   766.7   692.1   775.9  693.81
     795  694.93   882.8  693.28   931.6  693.85  1048.6  700.67  1068.1  704.81
  1146.2  731.68  1233.9  759.03    1273  770.01  1370.5  792.53  1468.1  810.16
#Mann= 3 , 0 , 0
       0     .06       0   683.1    .045       0   757.4     .06       0
#XS Ineff= 2 , 0
                          856.19          703.33
Permanent Ineff=
       F       F
Bank Sta=683.1,757.4
XS Rating Curve= 0 ,0
Exp/Cntr=0.3,0.1

Type RM Length L Ch R = 1 ,37232.7 ,238.1,245.9,253.7
XS GIS Cut Line= 6
     1871402.531      673383.027      1872136.96      672914.098
     1872630.573      672923.702     1872875.799      672904.171
     1873006.007      672789.153     1873557.223      672344.275
#Sta/Elev= 30
       0  815.65   117.5  808.82   313.3  790.31     421  776.14   597.2  760.92
   773.5  750.38   871.4  749.24   929.4  738.31   987.5  732.41  1074.7     730
    1493  733.62  1512.7  729.58  1532.4  722.34  1542.2   712.6    1552  698.64
  1561.9  690.65    1640  689.22  1659.3  685.74  1688.3     683  1717.2  686.59
  1814.3  690.04  1902.9  705.92  2011.1  755.76  2119.3  801.25    2139  807.33
  2168.5  811.11    2198  818.13  2316.1   860.1  2453.8  925.09  2493.2  938.34
#Mann= 3 , 0 , 0
       0      .1       0  1659.3    .045       0  1717.2     .05       0
Bank Sta=1659.3,1717.2
XS Rating Curve= 0 ,0
Exp/Cntr=0.3,0.1

Type RM Length L Ch R = 1 ,36986.9 ,573.6,589.3,604.8
XS GIS Cut Line= 5
     1871837.427      673950.736     1872327.341      673365.493
     1873016.858      673036.549     1873164.092      672978.248
     1873663.559      672780.473
#Sta/Elev= 30
       0  755.97   234.8  742.08   430.5  748.63     548  748.33     822  744.76
   929.7  738.71   988.5  729.88  1027.7  720.75  1086.4   697.3    1106  693.22
    1439   691.4  1592.4  689.38    1611  687.22  1629.7  681.64    1639  681.32
  1648.3  681.83  1657.6  684.09  1666.9  688.38  1676.2  692.31  1705.1   699.5
  1724.6  708.01  1763.7  731.09  1812.5  764.85  1871.1  794.35    1920  807.26
  2037.2   833.4    2086  852.22  2115.3  866.57  2193.4  915.49  2222.8   932.2
#Mann= 3 , 0 , 0
       0     .05       0    1611    .045       0  1666.9     .06       0
Bank Sta=1611,1666.9
XS Rating Curve= 0 ,0
Exp/Cntr=0.3,0.1

Type RM Length L Ch R = 1 ,36397.5 ,442,446.9,451.9
XS GIS Cut Line= 4
     1872339.775      673422.834     1872767.292      673466.237
     1872931.457      673518.666     1873370.591      673457.556
#Sta/Elev= 30
       0  744.74    58.6  742.86   156.3  737.22   175.8  735.42   214.9  726.74
   224.6  723.94   234.4  719.82   263.7   703.9   273.4  699.34   283.2  695.64
     293  693.14   302.8  692.11     332  691.17   458.4   689.6   477.6  687.23
   487.2  684.21   496.7  681.84   515.9   681.3     535  681.96   544.6  684.92
     602  717.93   621.3     727   640.6  733.79   765.9  770.63   775.5  772.94
   814.1  779.32   871.9  795.54     949  815.53   997.2  826.84  1045.4  836.74
#Mann= 3 , 0 , 0
       0     .05       0   487.2    .045       0   544.6      .1       0
Bank Sta=487.2,544.6
XS Rating Curve= 0 ,0
Exp/Cntr=0.3,0.1

Type RM Length L Ch R = 1 ,35950.7 ,415.6,402.8,389.9
XS GIS Cut Line= 4
     1872292.032      673707.122     1872532.917       673826.48
     1872693.507      673919.796      1873353.23      673507.469
#Sta/Elev= 30
       0  749.98   153.6  729.86   163.2  727.13   172.8  721.98   201.6  699.15
   211.2  693.57   220.8  691.25   288.4   688.4   317.7  685.58   337.3  681.38
   356.8   681.1   386.1  682.09   395.9  685.07   405.7  689.41   415.5  691.13
   532.4  692.78   590.7  695.04   610.2  697.94   649.1  707.31     756  727.96
   785.2  730.01     863  737.81   940.8  748.72   989.4  751.58  1018.6  754.89
  1047.8  763.34    1077  773.07  1135.3  796.55    1145  799.82  1232.5  824.36
#Mann= 3 , 0 , 0
       0     .05       0   317.7    .045       0   395.9      .1       0
Bank Sta=317.7,395.9
XS Rating Curve= 0 ,0
Exp/Cntr=0.3,0.1

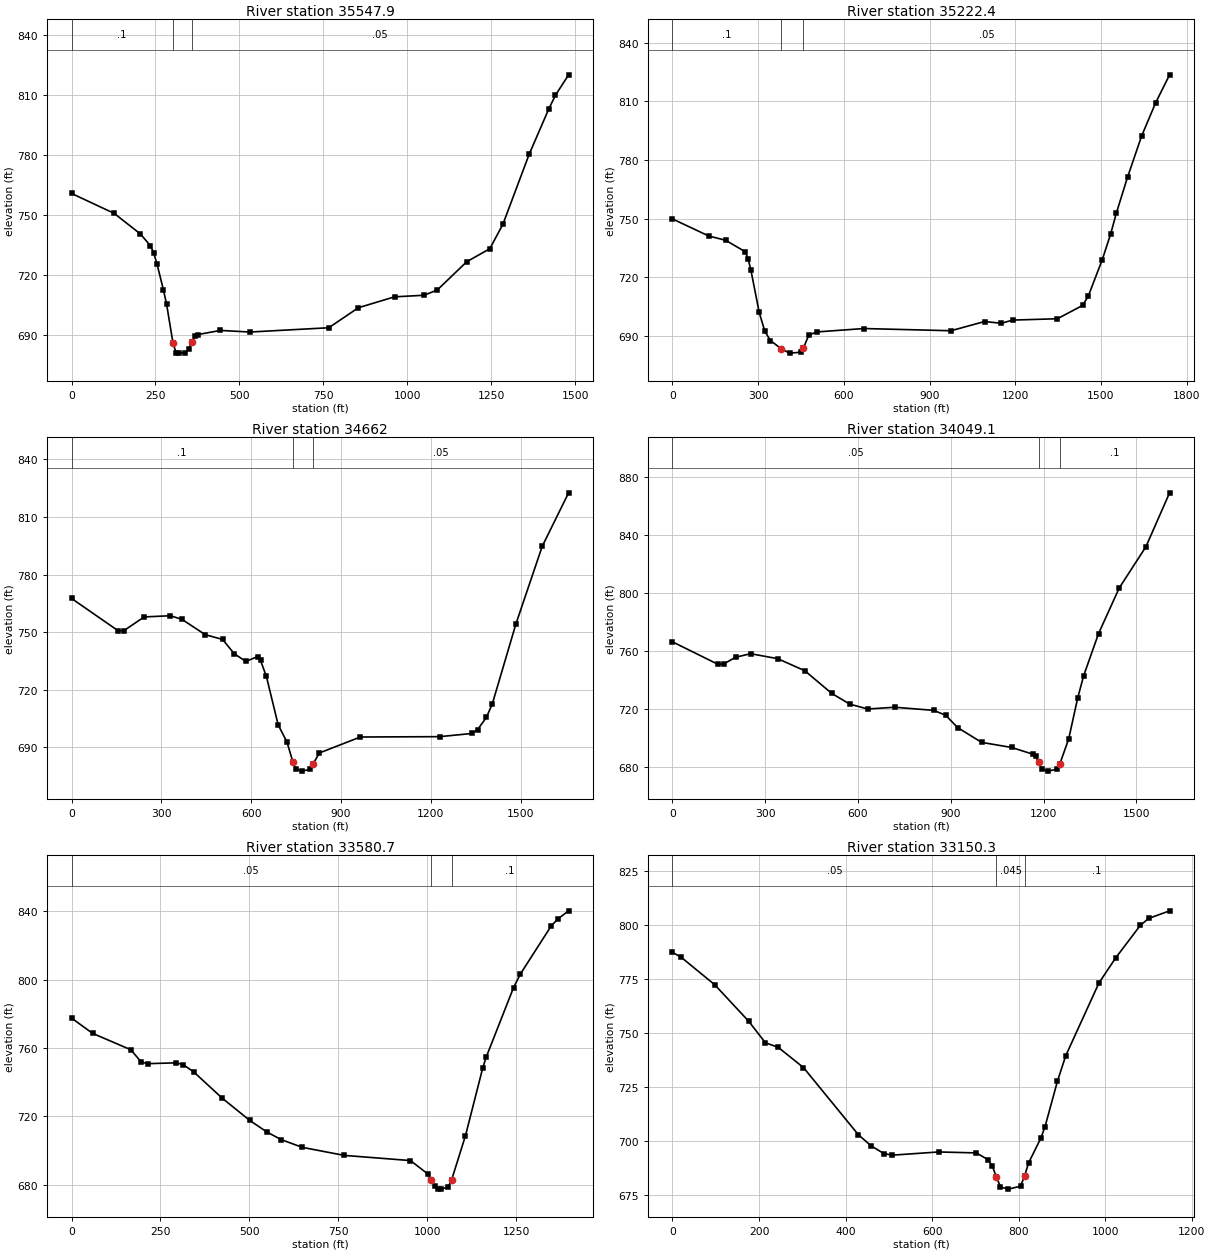
Type RM Length L Ch R = 1 ,35547.9 ,346.1,325.4,304.5
XS GIS Cut Line= 4
     1872144.168      674247.052       1872417.9      674238.806
     1872567.639      674232.296     1873377.101      673553.042
#Sta/Elev= 30
       0  760.88   127.2  750.89   205.4   740.6   234.7   734.8   244.5   731.3
   254.3  725.79   273.9  712.59   283.2  705.47     302  686.39   311.3  681.26
   320.7   681.1   339.4  681.37   348.8  683.08   358.2   686.7   367.5  689.53
   376.9   690.4   443.3  692.44   531.4  691.64   766.2  693.78   854.2  703.77
   961.9  709.22  1049.9  710.01  1089.1  712.61  1177.1  726.77  1245.6  733.24
  1284.8  745.49    1363  780.47  1421.7  803.21  1441.3  809.93  1480.4  820.13
#Mann= 3 , 0 , 0
       0      .1       0     302    .045       0   358.2     .05       0
Bank Sta=302,358.2
XS Rating Curve= 0 ,0
Exp/Cntr=0.3,0.1

Type RM Length L Ch R = 1 ,35222.4 ,579,560.4,541.3
XS GIS Cut Line= 4
      1872270.33      674878.997     1872500.365      674599.049
     1872621.893      674427.608     1873405.313      673561.723
#Sta/Elev= 30
       0  749.84   127.3  741.08   186.1  738.91   254.6  733.04   264.4  729.54
   274.2  723.85   303.6  701.93   323.2   692.3   342.8  687.56   381.4  683.24
   410.1   681.1   448.3  681.54   457.9   683.5     477  690.33   505.6  691.96
   670.6   693.7   974.8  692.57  1092.5  697.28  1151.4   696.4  1190.7  698.02
  1347.7  698.72    1436  705.57  1455.6  710.31  1504.7  729.02  1534.1  742.21
  1553.7  752.75    1593  771.21    1642  792.19  1691.1  809.23  1740.2  823.66
#Mann= 3 , 0 , 0
       0      .1       0   381.4    .045       0   457.9     .05       0
Bank Sta=381.4,457.9
XS Rating Curve= 0 ,0
Exp/Cntr=0.3,0.1

Type RM Length L Ch R = 1 ,34662   ,594.1,612.9,632.7
XS GIS Cut Line= 4
     1872598.021      674859.466     1873025.539        674464.5
     1872936.563       674143.32     1873427.014      673583.424
#Sta/Elev= 30
       0  767.55   155.2  750.75   174.6  750.71   242.5   757.9   329.8  758.52
   368.6  756.66   446.2  748.66   504.4  746.16   543.2  738.73     582  734.69
   621.2  737.23     631  735.24   650.6  726.88   689.9  701.62   719.3  692.68
   738.9  682.39   748.7  678.61   768.3   677.5   797.7  678.46   807.5  681.44
   827.1  686.94   964.3  695.29  1228.7  695.47  1336.4  697.12    1356   699.2
  1385.4  705.57    1405  712.62  1483.4  754.09  1571.5  794.71  1659.6  822.61
#Mann= 3 , 0 , 0
       0      .1       0   738.9    .045       0   807.5     .05       0
Bank Sta=738.9,807.5
XS Rating Curve= 0 ,0
Exp/Cntr=0.3,0.1

Type RM Length L Ch R = 1 ,34049.1 ,441.1,468.4,495.1
XS GIS Cut Line= 5
     1872624.063      674857.296     1873108.004       674451.48
     1873372.761      674045.664      1873509.48      673856.862
       1873667.9      673652.869
#Sta/Elev= 30
       0  766.58   145.8  751.22   165.2  751.28     204  755.95   252.6  758.42
   340.1  754.98   427.5  746.73     515  731.05   573.3  723.66   631.6  720.31
   718.8  721.52   844.8  719.36   883.5  715.98   922.3  707.47   999.8   697.3
  1096.7   693.8  1164.7  689.21  1174.4  687.75  1184.1  683.81  1193.8  678.87
  1213.2   677.5  1242.4  678.76  1252.1  682.19  1281.2  699.62  1310.4  727.92
  1329.8  743.32  1377.9  772.33  1444.9  803.77    1531  832.13  1607.5  869.26
#Mann= 3 , 0 , 0
       0     .05       0  1184.1    .045       0  1252.1      .1       0
Bank Sta=1184.1,1252.1
XS Rating Curve= 0 ,0
Exp/Cntr=0.3,0.1

Type RM Length L Ch R = 1 ,33580.7 ,422.9,430.4,437.9
XS GIS Cut Line= 4
     1872613.212      674911.983      1873399.67       674391.15
      1873587.17      674438.025     1873842.379      674492.712
#Sta/Elev= 30
       0   777.5      59  768.58     167  758.94   196.5  751.65   216.2  750.85
   294.8  751.33   314.4  750.23   343.9  745.95   422.5  730.89   501.1  717.64
   550.2  710.78   589.6  706.44   648.5  701.94   766.4  697.23     953  694.19
  1001.3  686.44  1010.9   683.1  1020.6  679.45  1030.3  677.72  1039.9   677.5
  1059.2  678.86  1068.9  683.02  1107.6  708.72  1155.9  748.09  1165.6  754.49
  1242.9  795.36  1262.2   803.3  1349.2   831.5  1368.6  835.63  1397.6  840.18
#Mann= 3 , 0 , 0
       0     .05       0  1010.9    .045       0  1068.9      .1       0
Bank Sta=1010.9,1068.9
XS Rating Curve= 0 ,0
Exp/Cntr=0.3,0.1

Type RM Length L Ch R = 1 ,33150.3 ,643.6,643,641.3
XS GIS Cut Line= 4
     1872583.698      674972.747     1873229.532      674748.789
     1873370.157      674839.934     1873619.146      675003.131
#Sta/Elev= 30
       0  787.31    19.5  785.15    97.6  772.29   175.8  755.44   214.8  745.37
   244.1   743.3   302.7  733.89   429.7   702.7     459  697.59   488.3  694.01
   507.8  693.25   615.2  694.74   702.2   694.3   730.1  691.07   739.4  688.05
   748.7  683.08     758   678.5   776.2   677.5   804.6  678.88   813.9  683.77
   823.2  689.75   851.1  701.06   860.8  706.36   889.6  727.52   908.8  739.36
   985.6  773.13    1024  784.68  1081.6  799.94  1100.8  803.07  1148.8  806.58
#Mann= 3 , 0 , 0
       0     .05       0   748.7    .045       0   813.9      .1       0
Bank Sta=748.7,813.9
XS Rating Curve= 0 ,0
Exp/Cntr=0.3,0.1

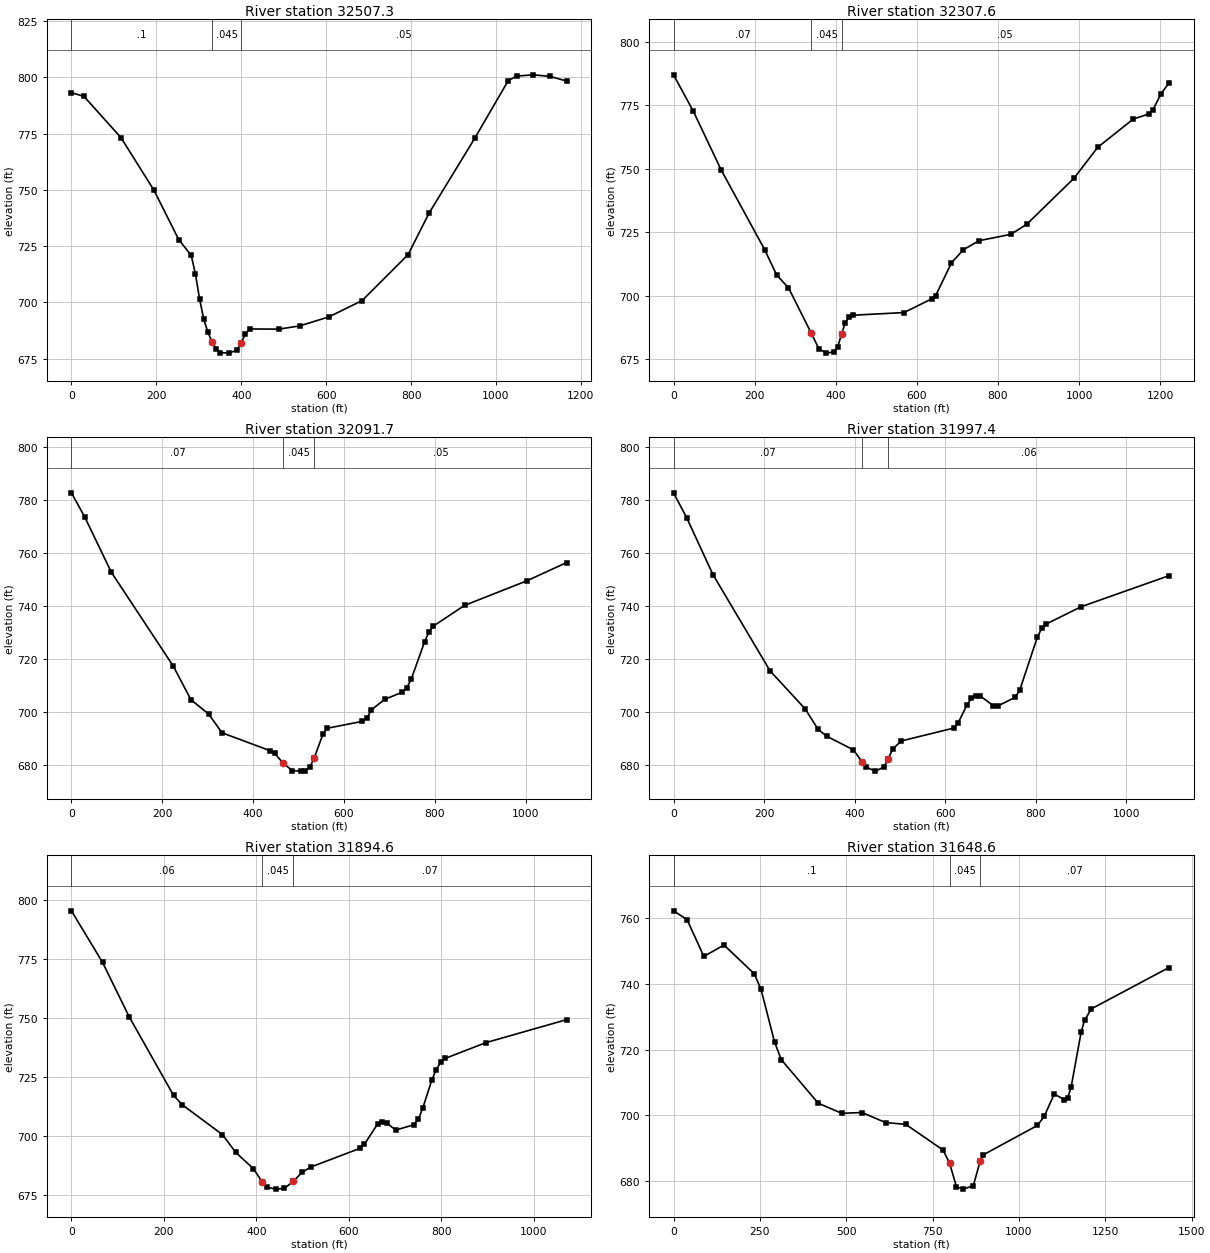
Type RM Length L Ch R = 1 ,32507.3 ,202.8,199.7,198.5
XS GIS Cut Line= 4
     1872518.594      675030.039     1872745.157      675142.018
     1872943.073      675269.622     1873620.157      675227.955
#Sta/Elev= 30
       0  793.12    29.2  791.59   116.6  773.24   194.4  749.84   252.7  727.95
   282.2  720.88     292  712.72   301.8  701.63   311.6  692.61   321.4  686.79
   331.2   682.5     341  679.34   350.8  677.76   370.5   677.5   390.1  678.82
   399.9  682.12   409.7  686.01   419.5  688.24   488.2  688.15   537.4  689.58
   606.2  693.58   684.8  700.85     793  721.26   842.1  739.59   950.3  773.03
  1028.9  798.53  1048.6  800.54  1087.9   801.1  1127.2  800.41  1166.6  798.33
#Mann= 3 , 0 , 0
       0      .1       0   331.2    .045       0   399.9     .05       0
Bank Sta=331.2,399.9
XS Rating Curve= 0 ,0
Exp/Cntr=0.3,0.1

Type RM Length L Ch R = 1 ,32307.6 ,189.7,215.9,240.2
XS GIS Cut Line= 4
     1872485.174       675149.83     1872697.848      675351.653
     1872841.925      675417.028     1873552.882      675711.896
#Sta/Elev= 30
       0  786.99    48.9  772.61   117.3   749.6   224.8  718.16   254.1  708.25
   283.4  703.19   339.7  685.29   358.3  679.22     377   677.5   395.6     678
   404.9  680.06   414.2  684.98   423.5  689.54   432.8  691.79   442.1  692.41
   568.3  693.47   636.5  698.85   646.3  700.15   685.2  713.02   714.5  718.17
   753.4  721.74   831.4  724.23   870.4  728.14   987.3  746.31  1045.7  758.45
  1133.4  769.59  1172.4  771.63  1182.1  773.24  1201.6  779.49  1221.1  783.71
#Mann= 3 , 0 , 0
       0     .07       0   339.7    .045       0   414.2     .05       0
Bank Sta=339.7,414.2
XS Rating Curve= 0 ,0
Exp/Cntr=0.3,0.1

Type RM Length L Ch R = 1 ,32091.7 ,94.9,94.3,94.7
XS GIS Cut Line= 4
     1872472.153      675186.723     1872706.528      675421.098
      1872732.57      675748.789     1873153.577      675837.764
#Sta/Elev= 30
       0  782.59    29.2   773.5    87.7  752.65   224.2  717.16   263.2  704.44
   302.2  699.05   331.5  691.98   437.8  685.19   447.5  684.18   466.8  680.43
   486.2   677.7   505.1   677.5   515.2  677.68   524.8  678.99   534.5  682.42
   553.8  691.49   563.5   693.7   640.8   696.3   650.5  697.48   660.2  700.58
   689.5  704.59   728.6  707.31   738.4     709   748.2  712.23   777.5   726.3
   787.3  730.14   797.1  732.29   865.6  740.08  1002.5  749.35  1090.5  756.27
#Mann= 3 , 0 , 0
       0     .07       0   466.8    .045       0   534.5     .05       0
Bank Sta=466.8,534.5
XS Rating Curve= 0 ,0
Exp/Cntr=0.3,0.1

Type RM Length L Ch R = 1 ,31997.4 ,108.2,102.8,98.3
XS GIS Cut Line= 4
     1872435.261      675227.955     1872626.233      675484.032
     1872634.914      675783.511     1873099.323      675881.167
#Sta/Elev= 30
       0  782.61      29  773.21    87.1  751.71     213  715.41   290.4  701.05
   319.4  693.24   338.8  690.64   396.8  685.58   416.1  681.12   425.8  679.02
   445.1  677.52   464.4  679.02   474.1   682.2   483.8  685.86   503.1  688.92
     619  693.79   628.7  695.82   648.1   702.6   657.8  704.98   667.5  705.84
   677.2  705.89   706.2  702.22   715.9   702.1   754.6  705.42   764.3  708.06
   803.1  728.02   812.8  731.41   822.4  733.04   899.9  739.59  1093.6  751.31
#Mann= 3 , 0 , 0
       0     .07       0   416.1    .045       0   474.1     .06       0
Bank Sta=416.1,474.1
XS Rating Curve= 0 ,0
Exp/Cntr=0.3,0.1

Type RM Length L Ch R = 1 ,31894.6 ,270.7,246,218.2
XS GIS Cut Line= 4
     1872302.905      675307.488     1872524.236        675609.9
     1872595.851      675807.382     1873073.282      675900.698
#Sta/Elev= 30
       0  795.27    67.3  773.45   124.9  750.44     221  717.14   240.2  713.13
   326.7  700.56   355.5  693.01   393.8  686.12     413  680.44   422.5  678.35
   441.6   677.5   460.7  677.81   479.8  680.75   498.9   684.6     518  686.87
   623.7  694.72   633.5   696.4   662.6  705.16   672.4  705.96   682.1  705.38
   701.6   702.5   740.5  704.72   750.2     707     760  711.81   779.4  723.62
   789.1  728.12   798.9  731.19   808.6  732.83   896.2  739.47  1071.3  749.23
#Mann= 3 , 0 , 0
       0     .06       0     413    .045       0   479.8     .07       0
Bank Sta=413,479.8
XS Rating Curve= 0 ,0
Exp/Cntr=0.3,0.1

Type RM Length L Ch R = 1 ,31648.6 ,145.2,142.3,138.6
XS GIS Cut Line= 4
     1871612.344      675638.546     1872254.271      675838.198
     1872512.084       675895.49      1873009.48      675908.511
#Sta/Elev= 30
       0  762.24      39  759.58    87.7  748.36   146.1  751.82   233.8  743.05
   253.3   738.3   292.3  722.35   311.8  716.94   418.9  703.66   487.1  700.58
   545.6  700.83   613.8  697.77   672.3  697.22   779.9  689.43   799.4  685.37
     819  678.21   838.5   677.5   867.9  678.56   887.4  685.92   897.2  687.97
  1053.4  696.89    1073  699.62  1102.2  706.47  1131.5  704.72  1141.2  705.34
    1151  708.53  1180.3  725.45    1190  728.88  1209.5  732.38  1433.9  744.95
#Mann= 3 , 0 , 0
       0      .1       0   799.4    .045       0   887.4     .07       0
Bank Sta=799.4,887.4
XS Rating Curve= 0 ,0
Exp/Cntr=0.3,0.1

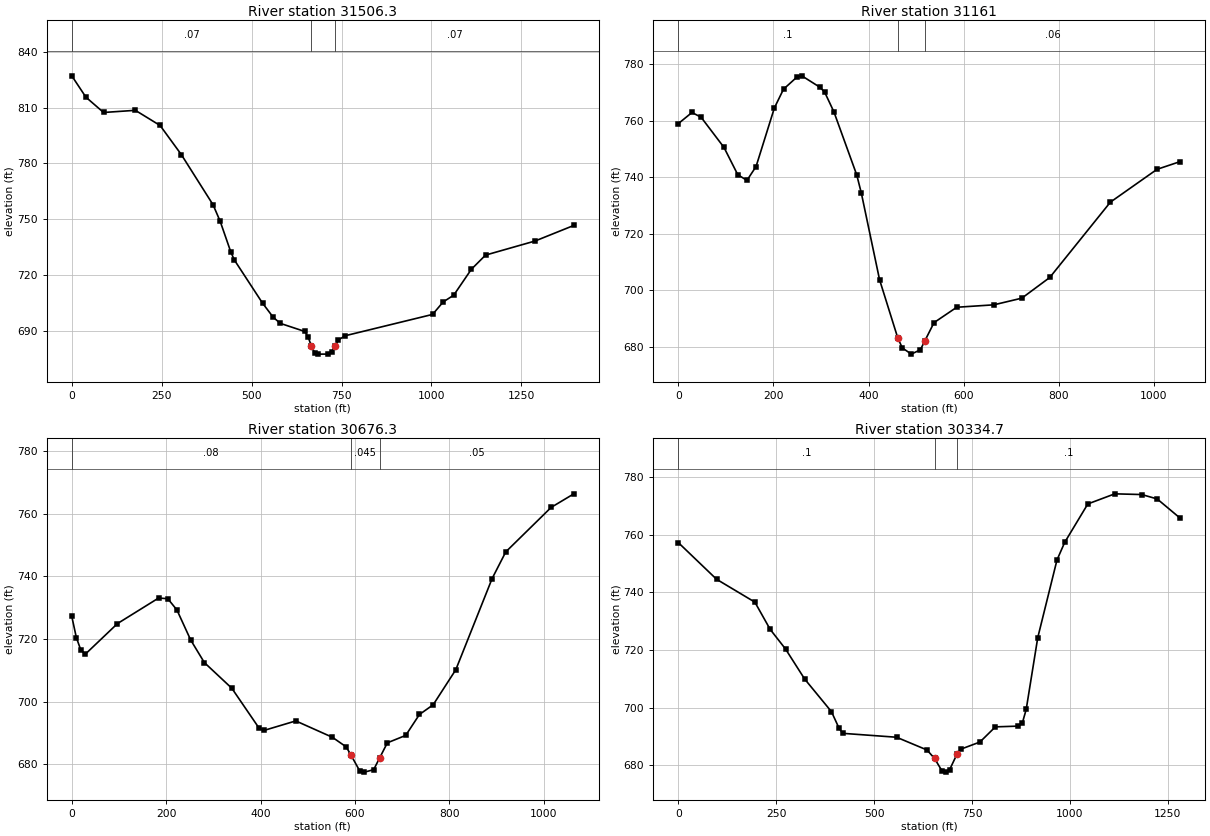
Type RM Length L Ch R = 1 ,31506.3 ,365.6,345.3,325.2
XS GIS Cut Line= 4
     1871642.726      675992.278     1872281.181      675987.504
     1872439.601      675991.844     1873034.219       675920.23
#Sta/Elev= 30
       0  827.07    39.3   815.6    88.4  807.37   176.8  808.53   245.6  800.38
   304.5  784.77   392.9  757.74   412.6  748.89     442  732.49   451.8  728.16
   530.4   704.9   559.9  697.36   579.5  694.05   647.8  689.68   657.1  686.73
   666.4  681.74   675.8  678.08   685.1   677.5     713  677.51   722.4  678.38
   731.7  681.61     741  685.07   759.7  687.36  1003.1  698.84  1032.6  705.54
    1062   709.2  1111.1  723.13  1150.4  730.72  1287.9  738.28  1395.9  746.67
#Mann= 3 , 0 , 0
       0     .07       0   666.4    .045       0   731.7     .07       0
Bank Sta=666.4,731.7
XS Rating Curve= 0 ,0
Exp/Cntr=0.3,0.1

Type RM Length L Ch R = 1 ,31161   ,481.3,484.7,487.4
XS GIS Cut Line= 4
     1872226.493      676582.556      1872478.23      676278.737
     1872606.268      676124.657     1873029.879      675944.101
#Sta/Elev= 30
       0  758.97    28.9  762.93    48.1  761.24    96.2  750.57   125.1  740.95
   144.4  738.92   163.6  743.83   202.1  764.54   221.3  771.17   250.2  775.56
   259.8  775.89   298.3   771.8     308  770.04   327.2  763.17   375.3  740.82
   384.9  734.42   423.2  703.81   461.3  683.32   470.9  679.71     490   677.5
     509  679.05   518.6  682.26   537.7  688.64   585.4  694.07   663.5  694.93
   722.3  697.29     781   704.6   908.4  731.23  1006.4  742.83  1055.4  745.59
#Mann= 3 , 0 , 0
       0      .1       0   461.3    .045       0   518.6     .06       0
Bank Sta=461.3,518.6
XS Rating Curve= 0 ,0
Exp/Cntr=0.3,0.1

Type RM Length L Ch R = 1 ,30676.3 ,329.7,341.6,353.7
XS GIS Cut Line= 4
      1872490.79       676664.37     1872940.469      676361.202
     1873096.719      676215.803     1873350.625      676042.191
#Sta/Elev= 30
       0  727.21     9.7  720.43    19.4  716.37      29  715.18    96.8   724.9
     184  733.06   203.4  732.83   222.7  729.25   251.8  719.68   280.8  712.46
     339  704.26   397.1  691.45   406.8  690.79   474.5  693.84     552  688.62
   581.1  685.57   590.8   683.1   610.2   677.8   619.9   677.5   639.4  678.28
   652.4  682.13   668.4  686.85   707.3  689.22   736.4   695.9   765.4  698.98
   813.4  710.18   890.3  739.27   919.2  747.77  1015.3  761.97  1063.4   766.3
#Mann= 3 , 0 , 0
       0     .08       0   590.8    .045       0   652.4     .05       0
Bank Sta=590.8,652.4
XS Rating Curve= 0 ,0
Exp/Cntr=0.3,0.1

Type RM Length L Ch R = 1 ,30334.7 ,358.1,372.6,388.3
XS GIS Cut Line= 4
     1872541.913      676742.991      1873111.91      676567.365
     1873272.553      676535.151     1873793.334      676510.941
#Sta/Elev= 30
       0  757.26    97.8  744.52   195.6  736.58   234.7  727.13   273.8  720.34
   322.7  709.91   391.1   698.6   410.7  692.79   420.4  691.07   557.3  689.72
     635   685.3   654.3  682.35   673.5  677.99   683.2  677.62   692.8  678.49
   712.1  684.02   721.7   685.6   770.1  688.06   809.5  693.32   868.5  693.58
   878.3  694.63   888.2  699.36   917.7  724.27   966.8   751.2   986.5  757.32
  1045.5  770.64  1114.4  774.15  1183.3   773.9  1222.6  772.37  1281.6  765.66
#Mann= 3 , 0 , 0
       0      .1       0   654.3    .045       0   712.1      .1       0
Bank Sta=654.3,712.1
XS Rating Curve= 0 ,0
Exp/Cntr=0.3,0.1