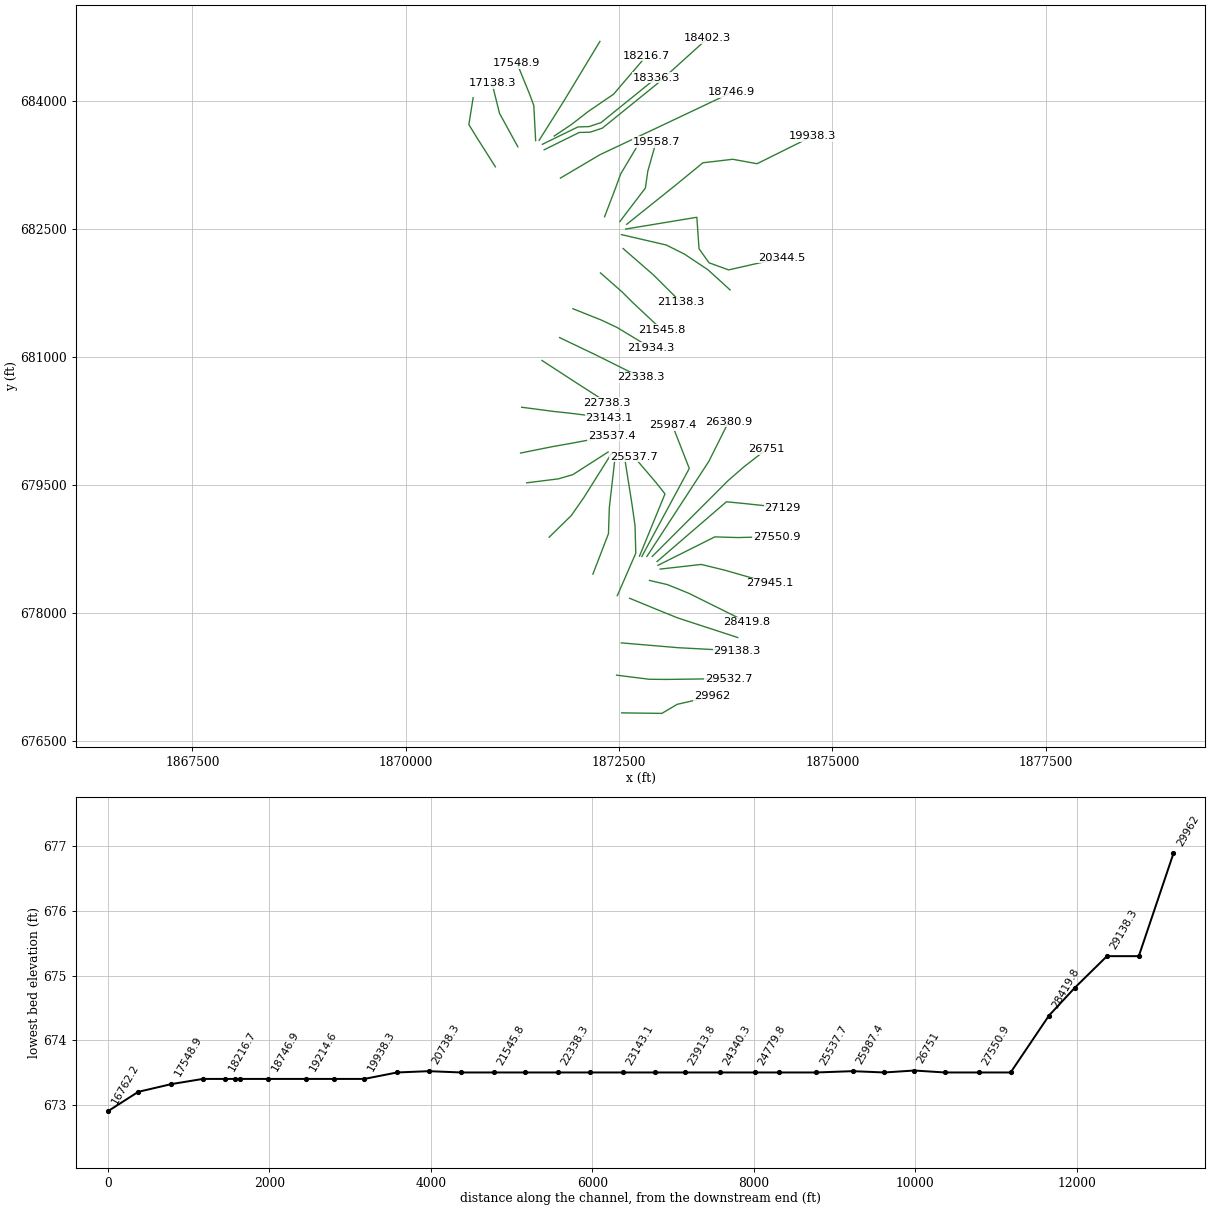
HEC-RAS study SpringCrk2.prj: SpringCrk2

--- SpringCrk2.g01 (geometry) --- (continued)

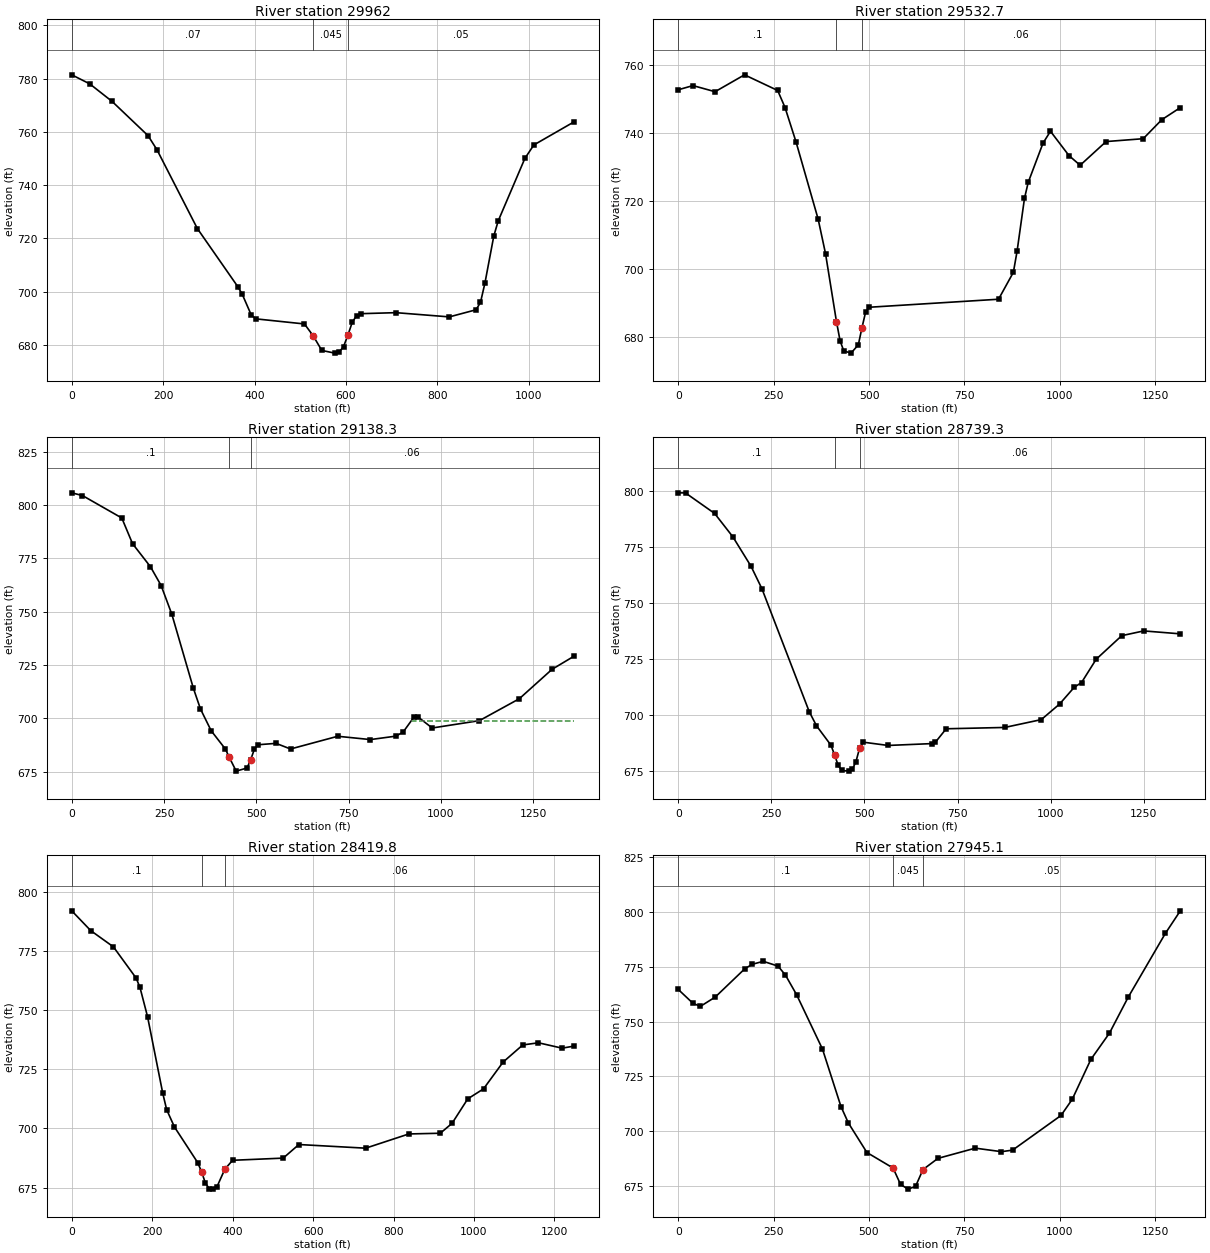
Type RM Length L Ch R = 1 ,29962   ,439.1,429.3,417.6
XS GIS Cut Line= 4
     1872530.002      676831.515     1873001.233      676825.612
     1873181.355      676931.948     1873589.341      677025.264
#Sta/Elev= 30
       0  781.43    39.3  778.04    88.4  771.42   166.9  758.59   186.5  753.29
   274.9  723.68   363.3  701.89   373.1  699.02   392.7  691.29   402.5  689.77
   509.3  687.85   528.3  683.43   547.3   677.9   575.8  676.89   585.4  677.31
   594.9  679.36   604.4  683.64   613.9  688.46   623.4  690.99   632.9  691.71
   709.6  692.09   826.4   690.5   884.8  693.17   894.6  695.91   904.3  703.14
   923.8   720.9   933.5  726.59   991.9  750.06  1011.4  755.08    1099  763.72
#Mann= 3 , 0 , 0
       0     .07       0   528.3    .045       0   604.4     .05       0
Bank Sta=528.3,604.4
XS Rating Curve= 0 ,0
Exp/Cntr=0.3,0.1

Type RM Length L Ch R = 1 ,29532.7 ,396.1,394.4,392.7
XS GIS Cut Line= 4
     1872470.652      677273.664     1872853.664      677225.351
     1873054.162       677223.45     1873783.351      677233.164
#Sta/Elev= 30
       0  752.85    38.6  754.08    96.5  752.28   173.7  757.25   260.6  752.64
   279.9  747.62   308.8  737.46   366.7  714.75     386   704.6   414.7  684.57
   424.2  678.91   433.8  675.96   452.9   675.3     472  677.76   481.5  682.79
   491.1  687.41   500.6  688.81   839.4  691.17   878.3   699.1     888   705.3
   907.4  720.87   917.2  725.59     956  737.14   975.5  740.63  1024.1  733.46
  1053.3  730.62  1121.3   737.6  1218.6  738.44  1267.2  744.03  1315.8   747.6
#Mann= 3 , 0 , 0
       0      .1       0   414.7    .045       0   481.5     .06       0
Bank Sta=414.7,481.5
XS Rating Curve= 0 ,0
Exp/Cntr=0.3,0.1

Type RM Length L Ch R = 1 ,29138.3 ,405.6,399,392.1
XS GIS Cut Line= 4
     1872525.904      677651.979     1872979.281      677613.581
     1873194.606      677595.345     1873882.309      677558.684
#Sta/Elev= 30
       0  805.76      29  804.48   135.5  793.96   164.6  781.92     213  771.14
     242  762.31   271.1  748.79   329.2  714.22   348.5  704.46   377.6  694.21
   416.3   685.6     426  681.95   445.3   675.3   474.6  676.76   484.5  680.61
   494.3  685.45   504.1  687.66   553.2  688.32   592.5  685.68   720.3  691.64
   808.8  690.09   877.7   691.7   897.4   693.6   926.9  700.66   936.7  700.84
   976.1  695.52    1104  698.96  1212.2  709.25  1300.8  723.03  1359.8  729.13
#Mann= 3 , 0 , 0
       0      .1       0     426    .045       0   484.5     .06       0
#XS Ineff= 2 , 0
                          919.66          698.94
Permanent Ineff=
       F       F
Bank Sta=426,484.5
XS Rating Curve= 0 ,0
Exp/Cntr=0.3,0.1

Type RM Length L Ch R = 1 ,28739.3 ,319.1,319.5,320
XS GIS Cut Line= 4
     1872623.908      678174.723     1872994.289      678022.226
     1873189.875      677943.615     1873890.122      677714.934
#Sta/Elev= 30
       0  799.14    19.5   799.1    97.7  789.93   146.5  779.52   195.4  766.34
   224.7  756.29   351.7  701.37   371.2  695.07   410.1  686.38   419.7  682.07
   429.3  677.47   438.9  675.11     458  674.81   467.6  675.65   477.2  679.09
   486.8  685.02   496.4  687.75   563.4  686.28   680.1   687.1   689.9  687.61
   719.4  693.73   876.5  694.32   974.8  697.83  1023.9  704.78  1063.2  712.27
  1082.8  714.38  1122.1  724.79  1190.8  735.33  1249.8  737.45    1348  736.14
#Mann= 3 , 0 , 0
       0      .1       0   419.7    .045       0   486.8     .06       0
Bank Sta=419.7,486.8
XS Rating Curve= 0 ,0
Exp/Cntr=0.3,0.1

Type RM Length L Ch R = 1 ,28419.8 ,470.7,474.7,478.5
XS GIS Cut Line= 4
     1872856.268      678384.205     1873067.205      678334.726
     1873317.205      678233.164     1873999.497      677894.622
#Sta/Elev= 30
       0  791.95    47.1   783.6   103.6  776.72   160.1  763.51   169.6  759.56
   188.4  747.23   226.3  714.81   235.9  707.95   255.2  700.66     313   685.6
   322.7  681.73   332.3  676.87     342  674.58   351.6  674.38   361.2  675.47
   380.5  682.79   399.8  686.56   525.6  687.48   564.6  693.22   730.6  691.68
     838  697.69   916.2  697.99   945.5  702.19   984.5  712.52  1023.6  716.73
  1072.4  728.07  1121.2  735.29  1160.3   736.2  1218.9  733.93  1248.2  734.79
#Mann= 3 , 0 , 0
       0      .1       0   322.7    .045       0   380.5     .06       0
Bank Sta=322.7,380.5
XS Rating Curve= 0 ,0
Exp/Cntr=0.3,0.1

Type RM Length L Ch R = 1 ,27945.1 ,390.8,394.2,398
XS GIS Cut Line= 4
     1872981.268      678517.018     1873463.039      678571.705
      1873739.08      678503.997     1874265.122      678352.955
#Sta/Elev= 30
       0  764.67    38.8   758.3    58.2  756.95      97  761.18   174.6  774.12
     194  776.15     223   777.5   261.8  775.31   281.2  771.19   310.3  762.28
   378.2  737.43   426.7  711.19   446.1   703.7   494.7  690.22   563.3  683.13
   582.9  675.66   602.5   673.5   622.1  674.72   641.7  682.43   680.9  687.54
   778.9  692.21   847.3   690.6   876.6   691.3  1003.6  707.13    1033   714.5
  1081.8   732.7  1130.7  744.75  1179.6  761.08  1277.3  790.29  1316.4  800.56
#Mann= 3 , 0 , 0
       0      .1       0   563.3    .045       0   641.7     .05       0
Bank Sta=563.3,641.7
XS Rating Curve= 0 ,0
Exp/Cntr=0.3,0.1

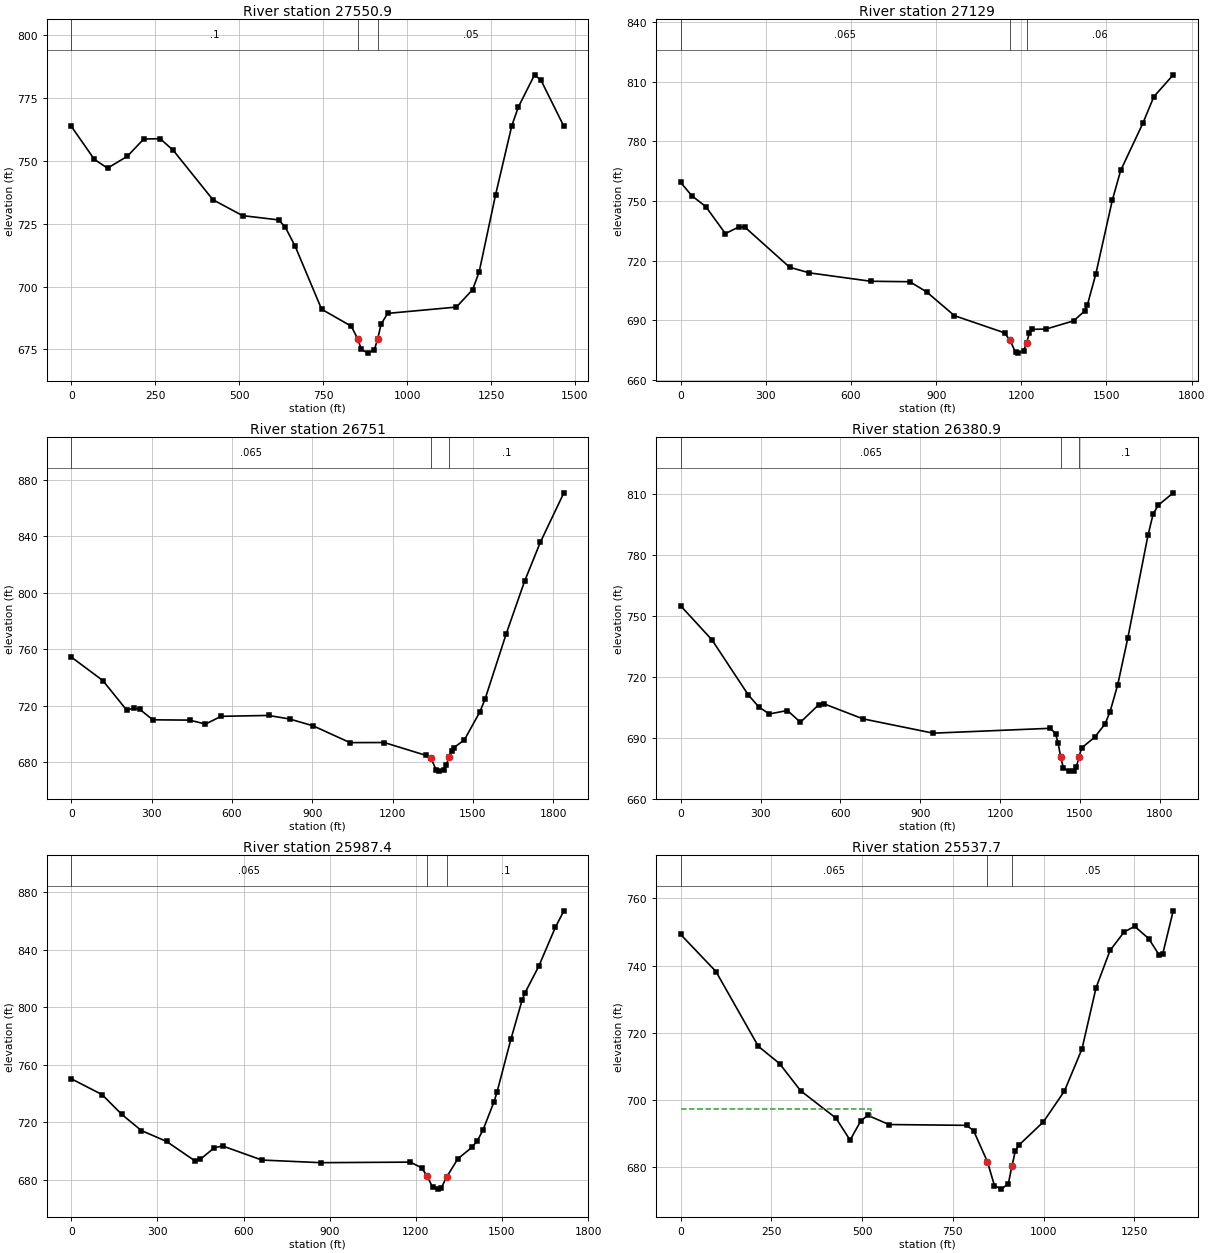
Type RM Length L Ch R = 1 ,27550.9 ,423.2,421.8,420.6
XS GIS Cut Line= 4
     1872955.226      678561.289     1873621.893      678894.622
     1873887.518      678886.809     1874343.247      678897.226
#Sta/Elev= 30
       0  763.73    68.6  750.58   107.9  747.08   166.7  751.79   215.8  758.68
   264.8   758.8     304  754.11   421.7  734.53     510   728.2   617.9  726.49
   637.5  723.55   666.9  715.96   745.4  690.97   833.9   684.2   853.6  678.99
   863.5  675.03   883.2   673.5   902.8  674.94   912.7  679.28   922.5  685.03
   942.2  689.31  1146.9  691.82  1195.4  698.79  1214.8  705.92  1263.3  736.36
  1311.8  763.93  1331.2  771.36  1379.6  784.21    1399     782  1466.9  763.73
#Mann= 3 , 0 , 0
       0      .1       0   853.6    .045       0   912.7     .05       0
Bank Sta=853.6,912.7
XS Rating Curve= 0 ,0
Exp/Cntr=0.3,0.1

Type RM Length L Ch R = 1 ,27129   ,359.3,378,395.8
XS GIS Cut Line= 4
     1872944.809      678605.559     1873757.309       679306.08
     1873960.378      679286.188     1874416.164      679238.372
#Sta/Elev= 30
       0  759.37    39.4  752.67    88.6   747.2   157.5  733.64   206.7   737.1
   226.4  736.85   383.8  716.71   452.7  713.89   669.3  709.66   807.1  709.42
   866.1  704.34   964.5  692.34  1140.8  683.71  1160.2  679.97  1179.7  673.82
  1189.4   673.5  1208.8  674.81  1218.5  678.71  1228.2  683.45    1238  685.48
  1286.6   685.6  1384.1  689.73  1423.1  694.67  1432.8   697.8  1462.1  713.15
  1520.6  750.48  1549.9  765.38  1627.9  789.08  1666.9  802.53  1735.1  813.51
#Mann= 3 , 0 , 0
       0    .065       0  1160.2    .045       0  1218.5     .06       0
Bank Sta=1160.2,1218.5
XS Rating Curve= 0 ,0
Exp/Cntr=0.3,0.1

Type RM Length L Ch R = 1 ,26751   ,361.2,370.1,379
XS GIS Cut Line= 4
     1872888.386      678665.455     1873777.275      679554.344
     1873965.471      679717.998     1874228.664        679922.4
#Sta/Elev= 30
       0   754.4   117.8  737.74   206.2  716.93   235.7  718.19   255.3  717.42
   304.4  709.91   441.9   709.7   500.9  706.89   559.8  712.39   736.6  713.01
   815.1   710.5   903.5  705.63    1041  693.74  1168.7  693.81  1324.2  684.72
  1343.4  682.56  1362.6  674.58  1372.2  673.53  1391.4  674.24    1401  678.04
  1410.6   683.9  1420.2  688.06  1429.7  690.27  1468.1  695.69  1526.1  715.56
  1545.7   724.8  1624.1  770.73  1692.7  808.03  1751.5  835.66  1839.7  870.85
#Mann= 3 , 0 , 0
       0    .065       0  1343.4    .045       0  1410.6      .1       0
Bank Sta=1343.4,1410.6
XS Rating Curve= 0 ,0
Exp/Cntr=0.3,0.1

Type RM Length L Ch R = 1 ,26380.9 ,374.7,393.5,412.1
XS GIS Cut Line= 4
     1872825.886      678665.455      1873551.58      679780.039
     1873669.636       680016.15     1873784.219      680245.316
#Sta/Elev= 30
       0  754.98   117.4  738.23   254.3  711.01   293.4  705.19   332.5  701.66
     401  703.38   449.9   697.6   518.3  706.19   537.9   706.7   684.6  699.27
   948.6  692.21  1388.7  694.61  1408.2  691.97    1418  687.16  1427.8  680.22
  1437.6   675.1  1457.1   673.5  1476.7  673.73  1486.4   675.6  1496.2  680.46
    1506  684.92  1554.9  690.18    1594  696.74    1613  702.85  1641.4  715.93
  1679.4  738.99  1755.3  789.69  1774.3  800.04  1793.3  804.49  1850.2  810.67
#Mann= 3 , 0 , 0
       0    .065       0  1427.8    .045       0  1496.2      .1       0
Bank Sta=1427.8,1496.2
XS Rating Curve= 0 ,0
Exp/Cntr=0.3,0.1

Type RM Length L Ch R = 1 ,25987.4 ,442.8,449.7,456.6
XS GIS Cut Line= 3
     1872766.858      678665.455     1873322.414      679696.705
     1873124.497       680203.65
#Sta/Elev= 30
       0  750.28   107.4  739.24   175.7  725.52     244  714.28   331.9  706.69
   429.5  693.32     449  694.21   497.8  702.28   527.1  703.53   663.8  693.75
   868.8  691.92  1181.1   692.3    1220  688.33  1239.4  682.63  1258.8  674.66
  1278.3  673.52    1288  674.19  1307.4  681.94  1346.3  694.62  1394.9  702.52
  1414.3  707.17  1433.8  714.56  1472.6  734.43  1482.4  740.74  1530.9  777.65
  1569.8  804.76  1579.5  809.75  1628.1  828.54  1686.4   855.8  1715.6  867.11
#Mann= 3 , 0 , 0
       0    .065       0  1239.4    .045       0  1307.4      .1       0
#XS Ineff= 2 , 0
          585.46  699.26
Permanent Ineff=
       F       F
Bank Sta=1239.4,1307.4
XS Rating Curve= 0 ,0
Exp/Cntr=0.3,0.1

Type RM Length L Ch R = 1 ,25537.7 ,471.4,459.3,447.1
XS GIS Cut Line= 4
      1872739.08      678668.928     1873037.691      679398.094
     1872936.997      679526.566     1872673.108      679835.594
#Sta/Elev= 30
       0  749.27    97.3  738.25     214     716   272.4  710.87   330.7  702.76
     428  694.63   466.9  688.08   496.1  693.73   515.6  695.47   573.9  692.72
   787.9  692.48   807.2  690.91   845.6  681.61   864.8  674.54     884   673.5
   903.2  675.16   912.8  680.28   922.4  684.91     932  686.58   999.6   693.5
  1057.6  702.68    1106  715.19  1144.7   733.4  1183.4  744.53  1222.1  750.01
  1251.1  751.69  1289.8  748.06  1318.8  743.15  1328.5  743.46  1357.5  756.31
#Mann= 3 , 0 , 0
       0    .065       0   845.6    .045       0   912.8     .05       0
#XS Ineff= 2 , 0
          524.41  697.25
Permanent Ineff=
       F       F
Bank Sta=845.6,912.8
XS Rating Curve= 0 ,0
Exp/Cntr=0.3,0.1

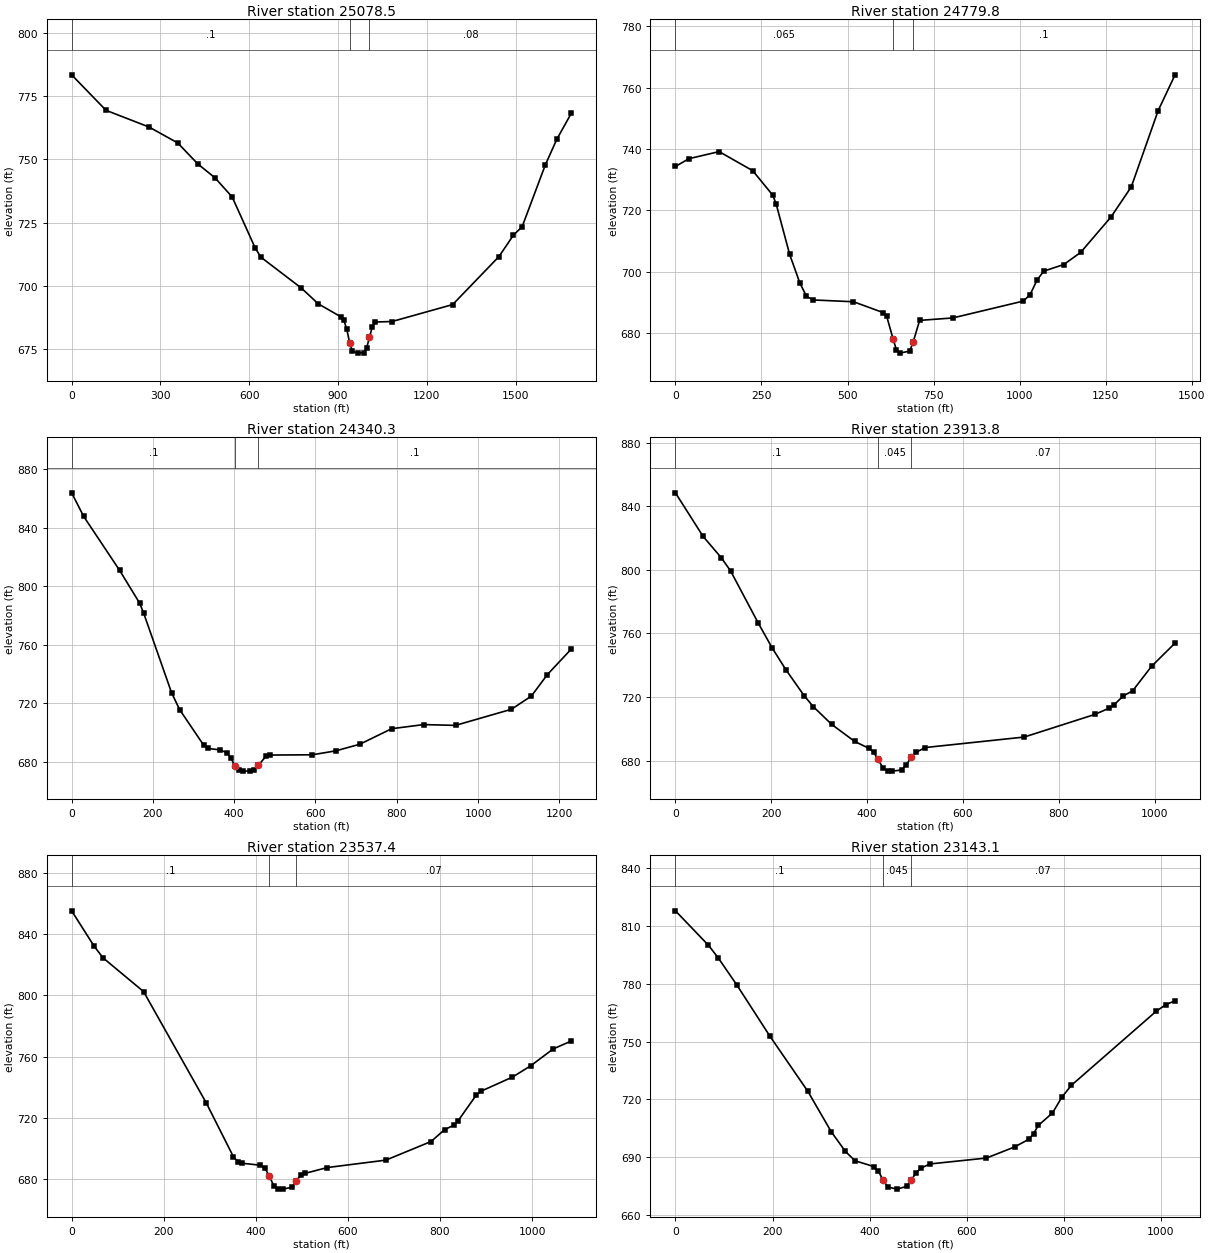
Type RM Length L Ch R = 1 ,25078.5 ,302.2,298.6,295
XS GIS Cut Line= 5
     1872479.137      678205.727     1872695.417      678703.126
     1872686.997      679023.094     1872652.275      679269.622
     1872561.997      679839.066
#Sta/Elev= 30
       0  783.41   116.2  769.38   261.5   762.8   358.4  756.51   426.2  748.22
   484.3  742.74   542.4  735.15     620  715.05   639.4  711.39   775.2  699.27
   833.4  692.97   910.3  687.79   919.9  686.41   929.5  682.93   939.1  677.66
   948.6  674.27   967.8   673.5     987  673.73   996.5  675.51  1006.1  679.68
  1015.7  683.91  1025.2  685.78  1082.7  685.99  1287.3  692.68  1443.7  711.64
  1492.5  720.09  1521.9   723.4    1600  747.74  1639.1  757.97    1688   768.2
#Mann= 3 , 0 , 0
       0      .1       0   939.1    .045       0  1006.1     .08       0
Bank Sta=939.1,1006.1
XS Rating Curve= 0 ,0
Exp/Cntr=0.3,0.1

Type RM Length L Ch R = 1 ,24779.8 ,452.3,439.5,426.7
XS GIS Cut Line= 4
     1872193.073       678457.99     1872375.365      678931.948
     1872385.782       679239.24      1872457.83      679871.647
#Sta/Elev= 30
       0  734.32    39.1  736.86     127  739.17   224.6  732.94   283.2  724.92
     293  721.97     332  705.64   361.3  696.43   380.8  692.01   400.4  690.83
   517.4  690.24   603.9   686.7   613.5   685.7   632.7  677.98   642.3  674.52
   651.9   673.5   680.8  674.16   690.4  676.98   709.6  684.17   805.7  684.96
  1011.1  690.47  1030.7  692.57  1050.3  697.22  1069.9   700.2  1128.6  702.38
  1177.6  706.33  1265.7  717.88  1324.5  727.66  1402.8  752.56  1451.8  764.19
#Mann= 3 , 0 , 0
       0    .065       0   632.7    .045       0   690.4      .1       0
Bank Sta=632.7,690.4
XS Rating Curve= 0 ,0
Exp/Cntr=0.3,0.1

Type RM Length L Ch R = 1 ,24340.3 ,441.7,426.5,411.3
XS GIS Cut Line= 4
     1871680.457      678890.681     1871940.469       679145.49
     1872087.051      679355.894     1872410.955      679871.647
#Sta/Elev= 30
       0  864.02    29.5  847.93   118.1  810.92   167.3  788.49   177.1  781.74
     246  727.08   265.7  715.62   324.7  691.35   334.5  689.04     364  688.09
     383  686.03   392.5  682.26     402  676.76   411.5  674.01     421   673.5
     440  673.59   449.5  674.59     459  677.38     478   683.6   487.5   684.5
     592  684.68     650  687.38   708.9  691.89   787.5  702.54   866.1  705.36
   944.6  704.81  1082.2  715.85  1131.3  724.87  1170.6  739.58  1229.5  757.07
#Mann= 3 , 0 , 0
       0      .1       0     402    .045       0     459      .1       0
Bank Sta=402,459
XS Rating Curve= 0 ,0
Exp/Cntr=0.3,0.1

Type RM Length L Ch R = 1 ,23913.8 ,379,376.4,373.8
XS GIS Cut Line= 4
     1871417.414      679528.277     1871788.559      679574.772
      1871957.83      679624.252     1872371.893      679889.877
#Sta/Elev= 30
       0   848.4    57.6  821.07    95.9  807.52   115.1  799.31   172.6  766.64
   201.4  751.13   230.2  737.33   268.6  720.89   287.7     714   326.1  702.83
     374  692.14   403.4  687.87   413.2  685.51     423  680.81   432.8   675.5
   442.6  673.51   452.4   673.5     472  674.22   481.8  677.47   491.6  682.08
   501.4  685.21     521  688.32   727.5  694.91   875.1  709.15   904.6  713.05
   914.4  714.96   934.1  720.73   953.8  723.96   993.2  739.36  1042.3  753.98
#Mann= 3 , 0 , 0
       0      .1       0     423    .045       0   491.6     .07       0
Bank Sta=423,491.6
XS Rating Curve= 0 ,0
Exp/Cntr=0.3,0.1

Type RM Length L Ch R = 1 ,23537.4 ,400.6,394.3,388
XS GIS Cut Line= 4
     1871345.052      679877.526     1871718.247      679952.377
      1871947.59       679993.08     1872410.955      680079.981
#Sta/Elev= 30
       0  855.12    48.8  832.04    68.3   824.4   156.2  802.41   292.8  729.51
   351.4  694.56   361.1   691.4   370.9  690.36   409.7  689.12   419.4  687.41
   429.2  682.01   438.9  675.74   448.6  673.58   458.3   673.5   477.7  674.67
   487.4   678.6   497.1  682.44   506.8  683.79   555.3  687.59   682.3  692.42
   780.5  704.57     810  712.34   829.6  715.17   839.4  718.17   878.7   734.9
   888.6  737.35   957.3  746.63   996.6  753.93  1045.7  764.99    1085  770.15
#Mann= 3 , 0 , 0
       0      .1       0   429.2    .045       0   487.4     .07       0
Bank Sta=429.2,487.4
XS Rating Curve= 0 ,0
Exp/Cntr=0.3,0.1

Type RM Length L Ch R = 1 ,23143.1 ,415.4,404.8,394.2
XS GIS Cut Line= 4
      1871358.48      680414.448     1871744.289      680363.835
     1871907.314      680346.729     1872379.705      680288.314
#Sta/Elev= 30
       0  817.77    68.1  799.89    87.6  793.56   126.5  779.32   194.6  752.78
   272.4  724.32     321  703.21   350.2  693.01   369.7  688.23   408.4  685.21
     418  682.77   427.7  678.22   437.3   674.6   456.6   673.5   475.9  674.91
   485.5  678.08   495.2  681.81   504.8  684.28   524.1  686.55   640.5  689.61
   698.8   695.4   727.9  699.35   737.6  702.28   747.3   706.5   776.5  712.97
   795.9  721.15   815.3  727.28   990.2  765.72  1009.6  769.07    1029  771.15
#Mann= 3 , 0 , 0
       0      .1       0   427.7    .045       0   485.5     .07       0
Bank Sta=427.7,485.5
XS Rating Curve= 0 ,0
Exp/Cntr=0.3,0.1

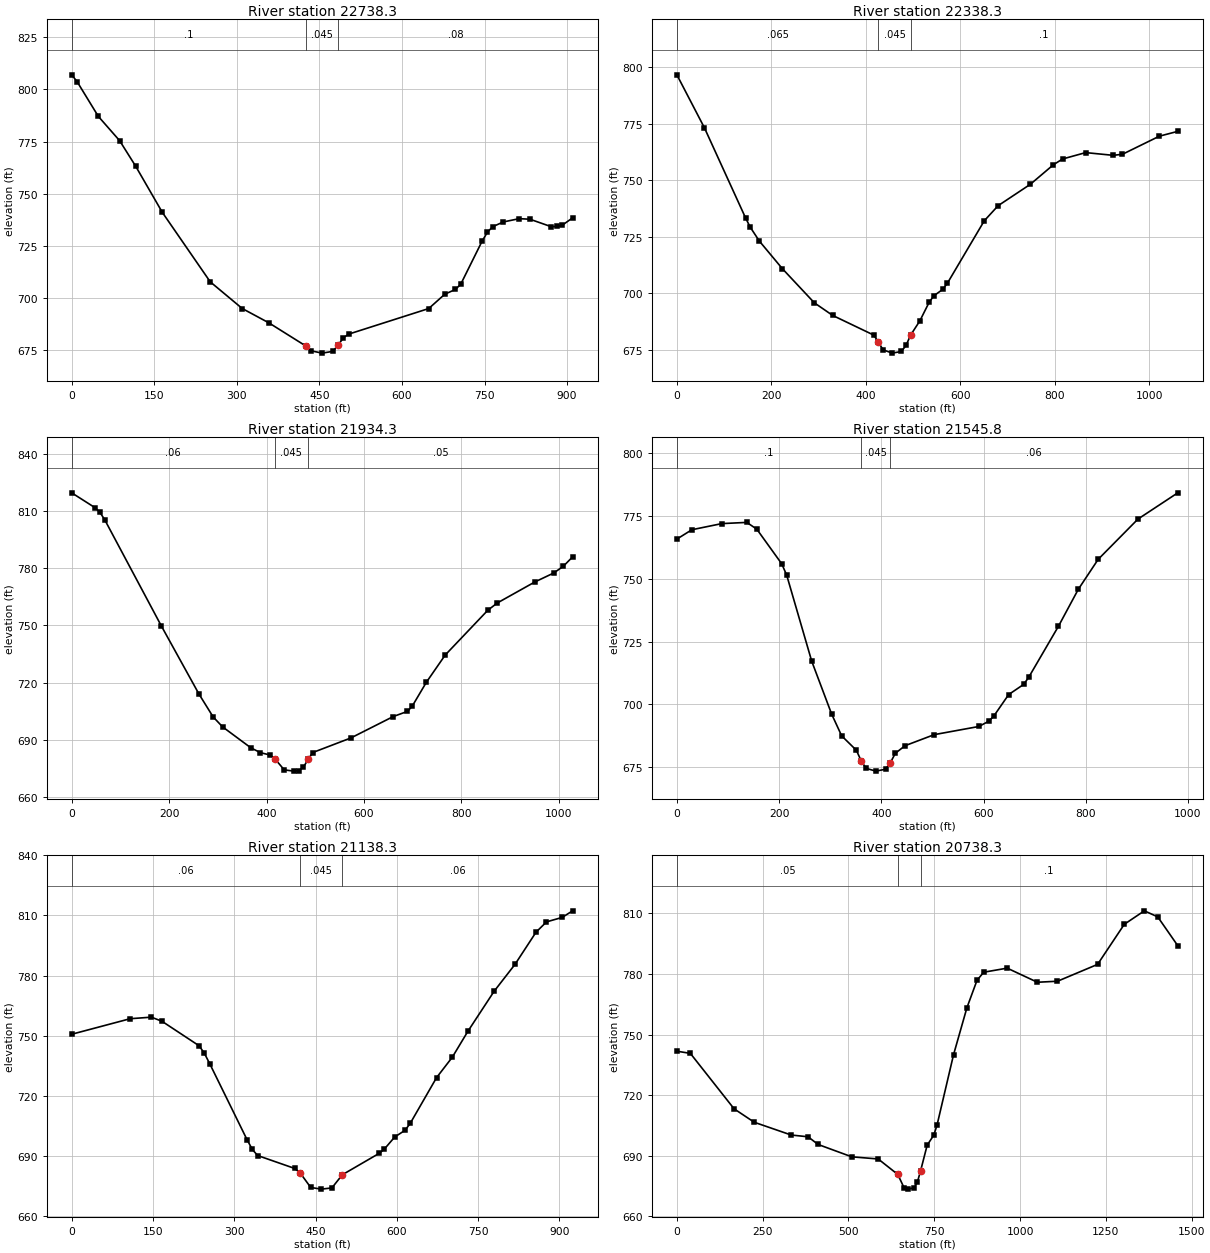
Type RM Length L Ch R = 1 ,22738.3 ,397,400,402.4
XS GIS Cut Line= 3
     1871596.188      680962.981     1871977.429      680714.607
     1872360.178      680468.585
#Sta/Elev= 30
       0  807.04     9.7   803.8    48.4  787.08    87.1  775.43   116.2  763.19
   164.6  741.04   251.7   707.7   309.8  694.91   358.2  688.03     426  676.81
   435.6  674.57     455   673.5   474.4  674.35     484  677.35   493.7  680.91
   503.4  682.64   648.6  694.89   677.7  701.75     697  704.06   706.7  706.53
   745.4  727.14   755.1  731.49   764.8  734.17   784.2  736.45   813.2  738.03
   832.6  737.74   871.3  734.16     881  734.32   890.6  734.77     910  738.41
#Mann= 3 , 0 , 0
       0      .1       0     426    .045       0     484     .08       0
Bank Sta=426,484
XS Rating Curve= 0 ,0
Exp/Cntr=0.3,0.1

Type RM Length L Ch R = 1 ,22338.3 ,403.9,404,404.5
XS GIS Cut Line= 3
     1871802.771      681230.779     1872222.577       681029.96
     1872754.705      680764.877
#Sta/Elev= 30
       0  796.73    58.2  773.31   145.4  733.34   155.1   729.3   174.5  723.12
     223  710.94   290.8  695.79   329.6   690.2   416.9  681.45   426.6  678.26
   436.3  674.98   455.7   673.5   475.1  674.24   484.9  676.91   494.6   681.5
   514.1  687.77   533.6  695.92   543.3   698.8   562.8  701.78   572.6  704.52
   650.5  732.11   679.8  738.79     748  748.27   796.7  756.91   816.2  759.47
     865  762.29   923.4  761.08   942.9  761.56  1020.9  769.56  1059.9   771.7
#Mann= 3 , 0 , 0
       0    .065       0   426.6    .045       0   494.6      .1       0
Bank Sta=426.6,494.6
XS Rating Curve= 0 ,0
Exp/Cntr=0.3,0.1

Type RM Length L Ch R = 1 ,21934.3 ,395.8,388.5,380.4
XS GIS Cut Line= 4
     1871958.552      681569.212     1872291.164      681436.752
     1872476.877      681349.235     1872874.497      681108.627
#Sta/Elev= 30
       0  819.65    48.4  811.76    58.1  809.32    67.7  805.54   183.8  749.82
   261.3  713.93   290.3  701.97   309.6  696.76   367.8  685.72   387.4  683.19
   406.9  681.98   416.7  680.07   436.2  674.16   455.8   673.5   465.6  673.78
   475.3  675.43   485.1  679.65   494.9  683.28     573  690.92   660.1  702.18
   689.2  704.88   698.9   707.6   727.9  720.15   766.6  734.46   853.8  757.92
   873.2  761.76   950.6  772.84   989.3  777.54  1008.7     781  1028.1  786.01
#Mann= 3 , 0 , 0
       0     .06       0   416.7    .045       0   485.1     .05       0
Bank Sta=416.7,485.1
XS Rating Curve= 0 ,0
Exp/Cntr=0.3,0.1

Type RM Length L Ch R = 1 ,21545.8 ,406,407.5,407.5
XS GIS Cut Line= 4
     1872281.789      681988.835     1872531.355      681769.651
     1872659.696      681642.143     1873000.105      681322.602
#Sta/Elev= 30
       0  765.78    29.3   769.5    87.9  771.94   136.8  772.42   156.3  769.74
   205.2  755.93   214.9   751.4   263.8  717.23   302.8  696.18   322.4  687.53
   351.2  681.79   360.7  677.52   370.2  674.61   389.3   673.5   408.3  674.26
   417.8  676.88   427.4   680.6   446.4  683.61   503.5  688.01   590.9  691.26
   610.3  693.36   620.1  695.41   649.2  703.96   678.4  707.98   688.2  710.76
   746.5   731.1   785.4  745.82   824.3  757.74   902.1  773.74     980  784.18
#Mann= 3 , 0 , 0
       0      .1       0   360.7    .045       0   417.8     .06       0
Bank Sta=360.7,417.8
XS Rating Curve= 0 ,0
Exp/Cntr=0.3,0.1

Type RM Length L Ch R = 1 ,21138.3 ,394.3,400,407.2
XS GIS Cut Line= 3
     1872546.861      682275.071     1872901.804      681966.251
     1873223.299       681645.89
#Sta/Elev= 30
       0  750.73   107.8  758.47     147  759.25   166.6  757.19   235.2  744.96
     245  741.13   254.8  735.98   323.5  698.17   333.3  693.29   343.1  690.25
   411.7  683.79   421.5  681.58   441.1  674.32   460.7   673.5   480.1   674.1
   499.4  680.67     567  691.28   576.7   693.4     596  699.48   615.3  702.87
     625  706.45   673.3  729.12   702.2  739.24   731.2  752.26   779.5  772.17
   818.1  785.61   856.8  801.62   876.1  806.76     905  808.98   924.3  812.27
#Mann= 3 , 0 , 0
       0     .06       0   421.5    .045       0   499.4     .06       0
Bank Sta=421.5,499.4
XS Rating Curve= 0 ,0
Exp/Cntr=0.3,0.1

Type RM Length L Ch R = 1 ,20738.3 ,381.5,393.8,406
XS GIS Cut Line= 5
     1872527.014      682438.054     1873052.188      682316.526
     1873264.861      682210.189     1873541.369      682025.917
     1873800.542      681789.994
#Sta/Elev= 30
       0  741.79    39.2  740.72   166.6  713.29   225.4  706.62   333.2   700.3
   382.2  699.43   411.6  695.62   509.6  689.51   586.6  688.45   643.7  680.79
   662.7  673.94   672.2  673.52   691.2  674.14   700.7  676.96   710.2  682.59
   729.3  695.26   748.3  700.16   757.8  705.02   806.2  740.06   845.2  763.33
   874.6  776.88   894.1  780.88   962.5   782.9  1050.5  775.92  1109.1  776.42
  1225.9  784.76  1303.8  804.61  1362.2  811.27  1401.2  808.28  1459.6  794.01
#Mann= 3 , 0 , 0
       0     .05       0   643.7    .045       0   710.2      .1       0
Bank Sta=643.7,710.2
XS Rating Curve= 0 ,0
Exp/Cntr=0.3,0.1

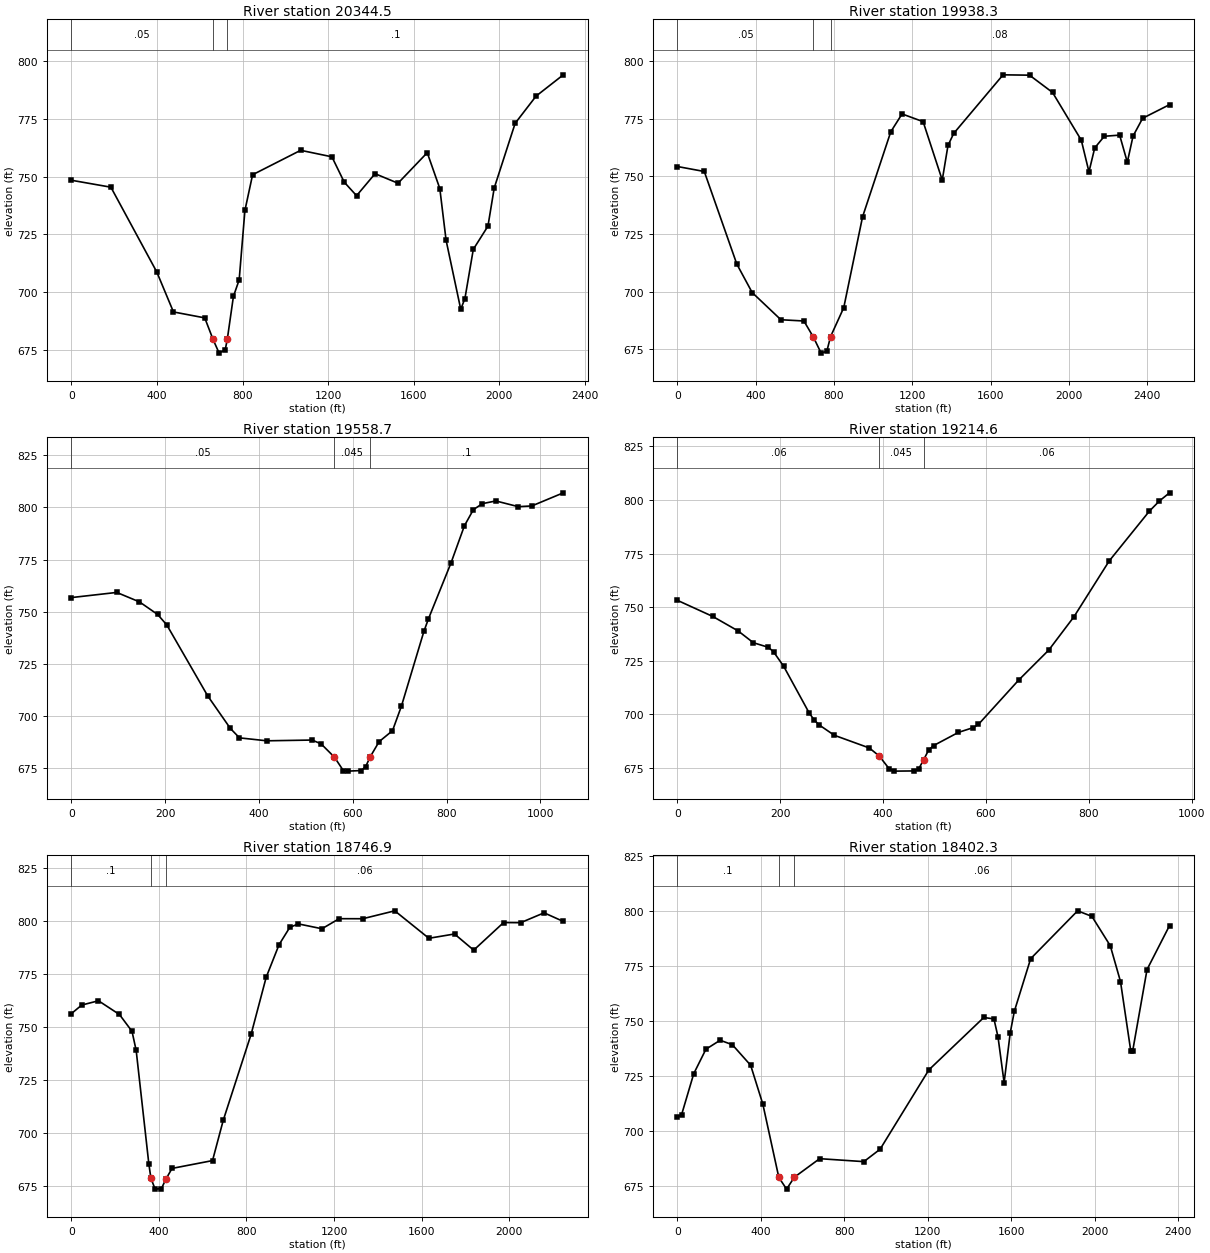
Type RM Length L Ch R = 1 ,20344.5 ,392.7,406.2,420
XS GIS Cut Line= 6
     1872576.927      682503.158     1873410.831      682641.345
     1873436.826      682271.764     1873554.014      682107.702
     1873783.181      682024.369     1874402.972      682164.994
#Sta/Elev= 30
       0  748.45   185.1  745.43   399.5  708.68   477.4  691.35   623.6  688.78
   662.2  679.47   690.8   673.5   719.4  675.02   728.9  679.49   757.5  698.07
   784.4  705.28   811.2  735.34   847.1  750.83  1071.7  761.42  1217.6   758.6
  1275.2  747.62  1332.8  741.75  1419.2  751.28  1526.5  747.15    1663  760.39
  1721.7  744.86    1751  722.45  1819.5  692.51    1839  697.15  1878.2   718.5
  1946.6  728.54  1975.9  745.08  2073.7  773.13  2171.5  784.92  2298.6  794.14
#Mann= 3 , 0 , 0
       0     .05       0   662.2    .045       0   728.9      .1       0
Bank Sta=662.2,728.9
XS Rating Curve= 0 ,0
Exp/Cntr=0.3,0.1

Type RM Length L Ch R = 1 ,19938.3 ,362.7,379.6,396.1
XS GIS Cut Line= 6
     1872589.344      682558.898     1873169.855      683024.162
     1873481.997      683280.331     1873831.792      683321.244
     1874116.514       683269.16      1874765.82      683592.077
#Sta/Elev= 30
       0  754.23     137  752.08   303.4  711.94   381.8  699.64   528.6  687.86
   646.1  687.32     695  680.28   734.2   673.4   763.2   674.2   782.4  680.55
   849.7  693.08   945.8   732.4  1090.1  769.28  1147.8  777.01  1255.4  773.66
  1353.2  748.36  1382.5  763.35  1411.9  768.59    1664  793.95  1799.2   793.8
  1916.8  786.32  2063.8  765.63    2103  751.93  2132.4  762.28  2181.4  767.34
  2259.8  767.83    2299   756.1  2328.4  767.44  2377.4  775.14  2514.6  781.02
#Mann= 3 , 0 , 0
       0     .05       0     695    .045       0   782.4     .08       0
Bank Sta=695,782.4
XS Rating Curve= 0 ,0
Exp/Cntr=0.3,0.1

Type RM Length L Ch R = 1 ,19558.7 ,348.6,344.1,339.7
XS GIS Cut Line= 4
     1872508.447      682590.751      1872807.83      682983.916
     1872836.476      683181.833      1872932.83      683522.978
#Sta/Elev= 30
       0  756.72    96.9   759.2   145.4  754.65   184.1  748.61   203.5  743.62
   290.7  709.55   339.1  693.89   358.5  689.37   416.7  687.96   513.2  688.32
   532.3  686.51   560.8  680.12   579.9  673.64   589.4   673.4     618  673.68
   627.5   675.6     637  680.23   656.1  687.56   684.6  692.81   703.7  704.66
   751.6  740.55   761.2  746.51   809.1  773.25   837.9  791.22     857  798.95
   876.2  801.83   904.9  803.12   952.8  800.37   981.6  800.73  1048.6  807.02
#Mann= 3 , 0 , 0
       0     .05       0   560.8    .045       0     637      .1       0
Bank Sta=560.8,637
XS Rating Curve= 0 ,0
Exp/Cntr=0.3,0.1

Type RM Length L Ch R = 1 ,19214.6 ,482.4,467.7,452.8
XS GIS Cut Line= 4
     1872329.966      682647.544     1872452.795      682969.159
     1872518.768      683149.715     1872734.045      683510.826
#Sta/Elev= 30
       0  753.13    68.8   745.6     118  738.85   147.6  733.35     177   731.2
   186.9  729.08   206.6  722.32   255.7  700.75   265.6  697.34   275.4     695
   304.9  690.15   373.1  684.21   392.3  680.48   411.6  674.54   421.2   673.4
   459.6  673.49   469.2  674.47   478.8  678.74   488.4   683.2   498.1  685.33
   546.3  691.48   575.6  693.75   585.4  695.25   663.6  715.91   722.3  729.98
   771.2  745.52   839.6  771.53   917.8   794.8   937.4  799.56   956.9  803.34
#Mann= 3 , 0 , 0
       0     .06       0   392.3    .045       0   478.8     .06       0
Bank Sta=392.3,478.8
XS Rating Curve= 0 ,0
Exp/Cntr=0.3,0.1

Type RM Length L Ch R = 1 ,18746.9 ,356.7,344.6,332.4
XS GIS Cut Line= 5
     1871813.039      683101.103      1872084.74      683261.694
     1872275.561      683374.831      1873020.07      683726.103
     1873821.375      684105.966
#Sta/Elev= 30
       0  756.19    47.8  760.28   124.3   762.3     220  755.82   277.4  747.89
   296.5  738.83   354.2  685.41   363.8  678.52   383.1   673.4   412.1  673.69
   431.4  677.97   460.3  683.18   645.2  686.87   694.2   705.9   821.7  746.57
   890.3   773.4   949.1  788.77   998.1  796.94  1037.3  798.58  1145.1  796.29
  1223.5  801.04  1331.3  801.02  1477.6  804.75  1633.5  791.79  1750.5  793.82
  1838.2  786.19  1974.6  799.21  2052.6  799.15  2159.8  803.81  2247.4  799.74
#Mann= 3 , 0 , 0
       0      .1       0   363.8    .045       0   431.4     .06       0
Bank Sta=363.8,431.4
XS Rating Curve= 0 ,0
Exp/Cntr=0.3,0.1

Type RM Length L Ch R = 1 ,18402.3 ,65.9,65.9,65.9
XS GIS Cut Line= 6
     1871622.066      683432.484     1872032.657      683635.392
     1872162.865      683639.298     1872304.389      683686.725
     1872955.834      684214.168     1873537.087      684739.068
#Sta/Elev= 30
       0  706.38    19.5  707.24      78  726.02   136.4  737.16   204.6  741.25
   263.1  739.21   350.8  729.85   409.3  712.11   485.9  678.73   523.1   673.4
   560.3  678.82   681.6  687.28   893.5  685.93   971.4  691.58  1205.4  727.76
  1468.5  751.62  1517.2  750.98  1536.7  742.78    1566  721.93  1595.3  744.61
  1614.9  754.41  1693.2  778.41  1918.4  800.23  1986.9   797.7    2075  784.31
  2123.9  768.02  2172.9  736.57  2182.7  736.55  2251.2  773.47  2358.9  793.48
#Mann= 3 , 0 , 0
       0      .1       0   485.9    .045       0   560.3     .06       0
Bank Sta=485.9,560.3
XS Rating Curve= 0 ,0
Exp/Cntr=0.3,0.1

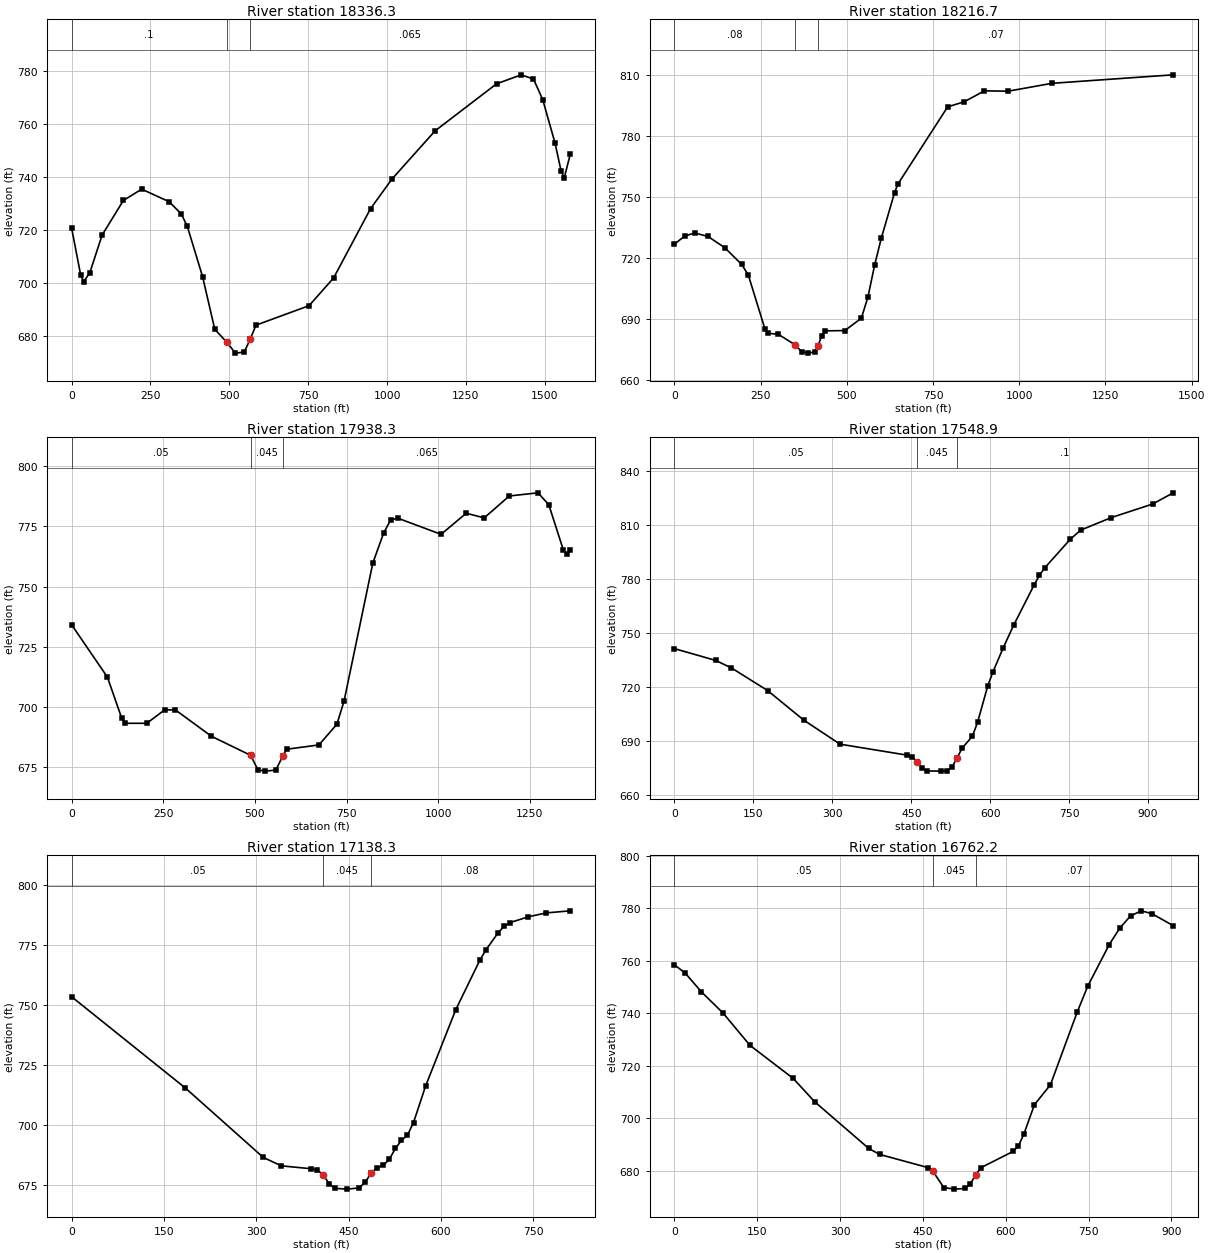
Type RM Length L Ch R = 1 ,18336.3 ,105.3,119.7,134
XS GIS Cut Line= 5
     1871601.233       683496.72     1872017.466      683700.496
     1872147.674      683704.402     1872289.198      683751.829
     1872940.643      684279.272
#Sta/Elev= 30
       0  720.65      29  702.75    38.6  700.44    57.9  703.82    96.6  717.98
   164.1  731.06   222.1  735.34     309  730.61   347.6     726   366.9  721.25
   415.2  702.29   453.8  682.42   491.4  677.58   519.3   673.4   547.2  673.81
   565.8  678.56   584.4  683.96   752.7  691.32   830.7  701.82   947.6  727.96
  1015.9  739.21  1152.3  757.37  1347.2  775.14  1425.2  778.53  1464.2  776.94
  1493.4   769.2  1532.4  752.79  1551.9  742.12  1561.7   739.6  1581.2  748.76
#Mann= 3 , 0 , 0
       0      .1       0   491.4    .045       0   565.8    .065       0
Bank Sta=491.4,565.8
XS Rating Curve= 0 ,0
Exp/Cntr=0.3,0.1

Type RM Length L Ch R = 1 ,18216.7 ,270.6,278.4,286.7
XS GIS Cut Line= 5
     1871740.122      683593.942     1871942.379      683729.359
     1872140.295      683883.005     1872434.566      684083.525
     1872822.587       684536.65
#Sta/Elev= 30
       0  727.01    29.2  730.91    58.4  732.52    97.4  730.77     146  725.25
   194.7  717.06   214.2  711.82   262.7  685.13   272.3  683.15   301.2  682.67
   349.4  677.52   368.7  674.17     388   673.4   407.2     674   416.9  677.04
   426.5  681.88   436.1  684.36     494  684.49   542.1  690.57   561.3  701.12
   580.6  716.74   599.8  729.89   638.3  752.28     648  756.54   792.3  794.52
   840.4  797.03     899  802.41   967.4  802.22  1094.6   806.1  1446.6  810.28
#Mann= 3 , 0 , 0
       0     .08       0   349.4    .045       0   416.9     .07       0
Bank Sta=349.4,416.9
XS Rating Curve= 0 ,0
Exp/Cntr=0.3,0.1

Type RM Length L Ch R = 1 ,17938.3 ,368.3,389.4,409.5
XS GIS Cut Line= 3
     1871563.039      683544.029     1871844.374       683990.26
     1872275.278      684702.883
#Sta/Elev= 30
       0  734.19    97.7  712.41   136.8   695.3   146.5  693.26   205.1  693.26
     254  698.87   283.3   698.8     381   687.9   488.4  679.95     508  673.96
   527.5   673.4   556.9  673.82   576.5  679.83   586.3  682.48   674.5  684.28
   723.5  692.88   743.1  702.54   821.4  759.73   850.8  772.21   870.4  777.78
     890   778.4  1007.6  771.72  1076.2  780.48  1125.2  778.54  1193.7  787.64
  1272.1  788.95  1301.5  783.97  1340.7  765.38  1350.5  763.57  1360.3  765.34
#Mann= 3 , 0 , 0
       0     .05       0   488.4    .045       0   576.5    .065       0
Bank Sta=488.4,576.5
XS Rating Curve= 0 ,0
Exp/Cntr=0.3,0.1

Type RM Length L Ch R = 1 ,17548.9 ,407.3,410.6,407.7
XS GIS Cut Line= 4
      1871522.24      683539.689     1871500.539      683952.015
     1871450.625      684086.564     1871302.737       684448.91
#Sta/Elev= 30
       0  741.34    78.6  734.78   108.1  730.65     177  718.08   245.8  701.63
   314.6  688.29   441.6  682.22   451.2  681.28   460.7  678.65   470.3   675.2
   479.9  673.44   506.5  673.32   518.1  673.57   527.7  675.68   537.3  680.83
   546.8  686.14   566.2  692.72     576  700.48   595.5  720.82   605.3  728.51
   624.9  741.94   644.5  754.32   683.6  776.81   693.4  781.99   703.2  786.06
   752.1  802.07   771.7  807.14   830.4  814.16   908.6  821.64   947.8  827.87
#Mann= 3 , 0 , 0
       0     .05       0   460.7    .045       0   537.3      .1       0
Bank Sta=460.7,537.3
XS Rating Curve= 0 ,0
Exp/Cntr=0.3,0.1

Type RM Length L Ch R = 1 ,17138.3 ,374.9,376.1,383.4
XS GIS Cut Line= 3
     1871313.694      683467.591     1871098.865      683860.156
     1871011.389      684211.998
#Sta/Elev= 30
       0  753.44   184.8  715.37   311.3  686.42   340.5  682.92   389.1   681.7
   398.9  681.15   408.6  679.19   418.3  675.44     428  673.52   447.5   673.2
   467.1  673.71   476.9  676.16   486.7  679.96   496.5   682.2   506.3  683.11
   516.1   685.7   525.9  690.15   535.7  693.53   545.5  695.72   555.3  700.97
   574.9  716.19   623.9  748.03   663.1  768.72   672.9  772.99   692.5  780.03
   702.3   782.8   712.1  784.37   741.5  786.77   770.9  788.42   810.1  789.28
#Mann= 3 , 0 , 0
       0     .05       0   408.6    .045       0   486.7     .08       0
Bank Sta=408.6,486.7
XS Rating Curve= 0 ,0
Exp/Cntr=0.3,0.1

Type RM Length L Ch R = 1 ,16762.2 ,402,405.9,409.8
XS GIS Cut Line= 4
     1871050.452      683232.831     1870836.042      683571.373
     1870739.688      683727.623     1870790.035      684042.727
#Sta/Elev= 30
       0  758.49    19.6  755.32    48.9  748.16      88   740.1   136.8  727.76
     215  715.16   254.1  706.21   351.9  688.42   371.4  686.16   458.7  681.14
   468.4  679.65   487.7  673.52     507   672.9   526.3  673.15     536  674.88
   545.6  678.44   555.3  681.11   613.3  687.28     623   689.4   632.6  693.76
     652  705.13     681  712.72   729.3  740.38   748.7  750.42   787.4  766.19
   806.7  772.53     826  777.16   845.4   779.1   864.7  778.02   903.4  773.43
#Mann= 3 , 0 , 0
       0     .05       0   468.4    .045       0   545.6     .07       0
Bank Sta=468.4,545.6
XS Rating Curve= 0 ,0
Exp/Cntr=0.3,0.1