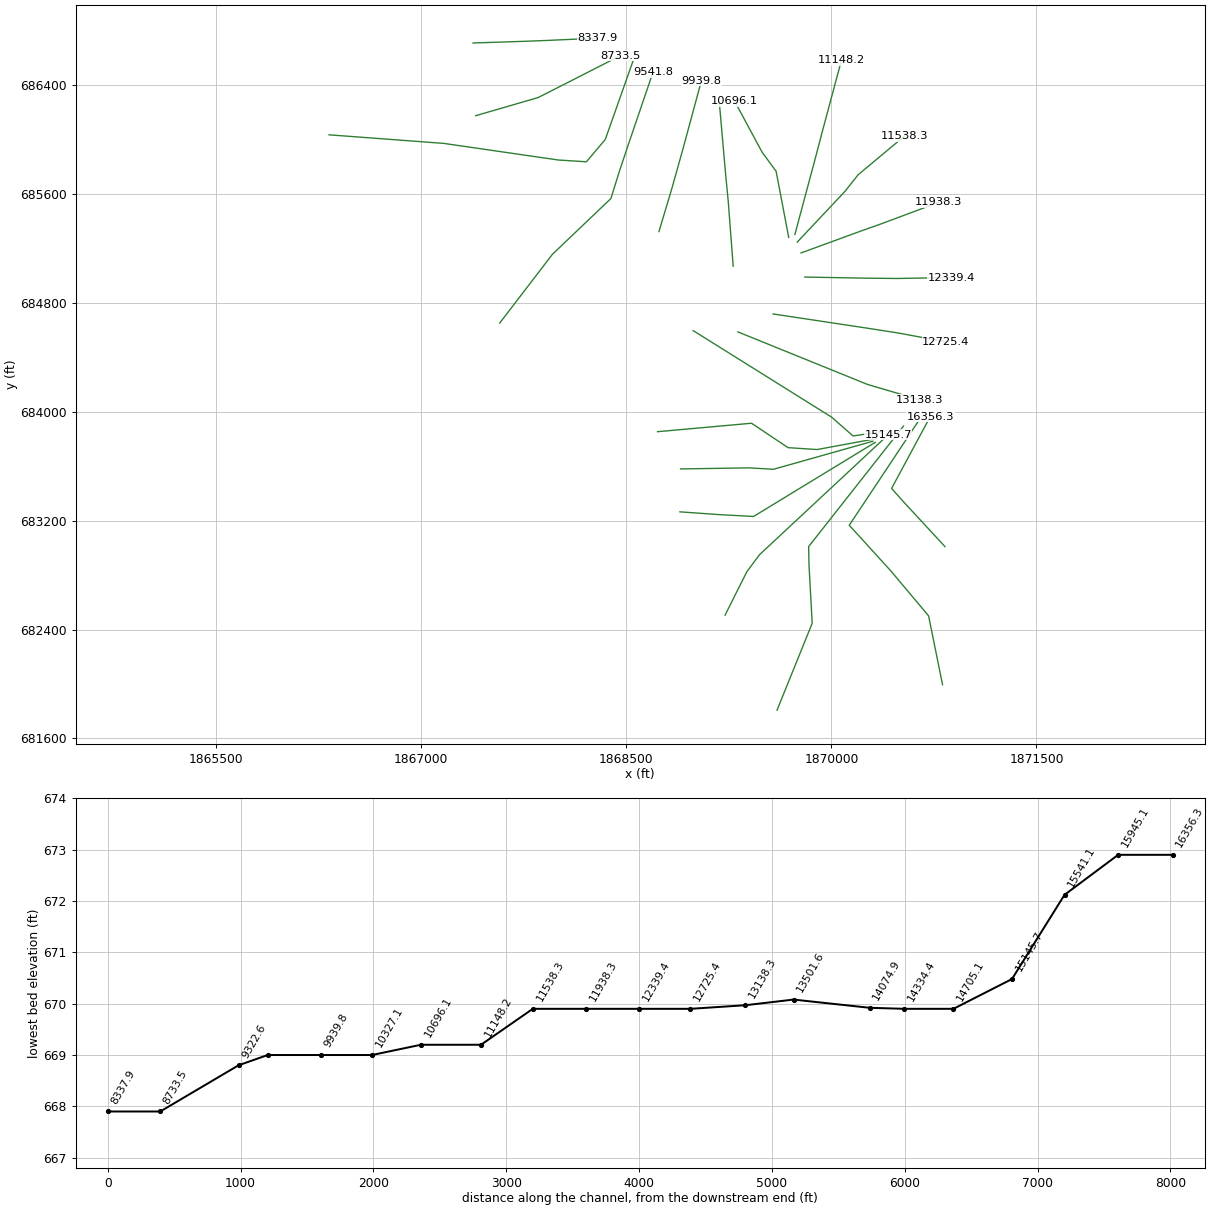
HEC-RAS study SpringCrk2.prj: SpringCrk2

--- SpringCrk2.g01 (geometry) --- (continued)

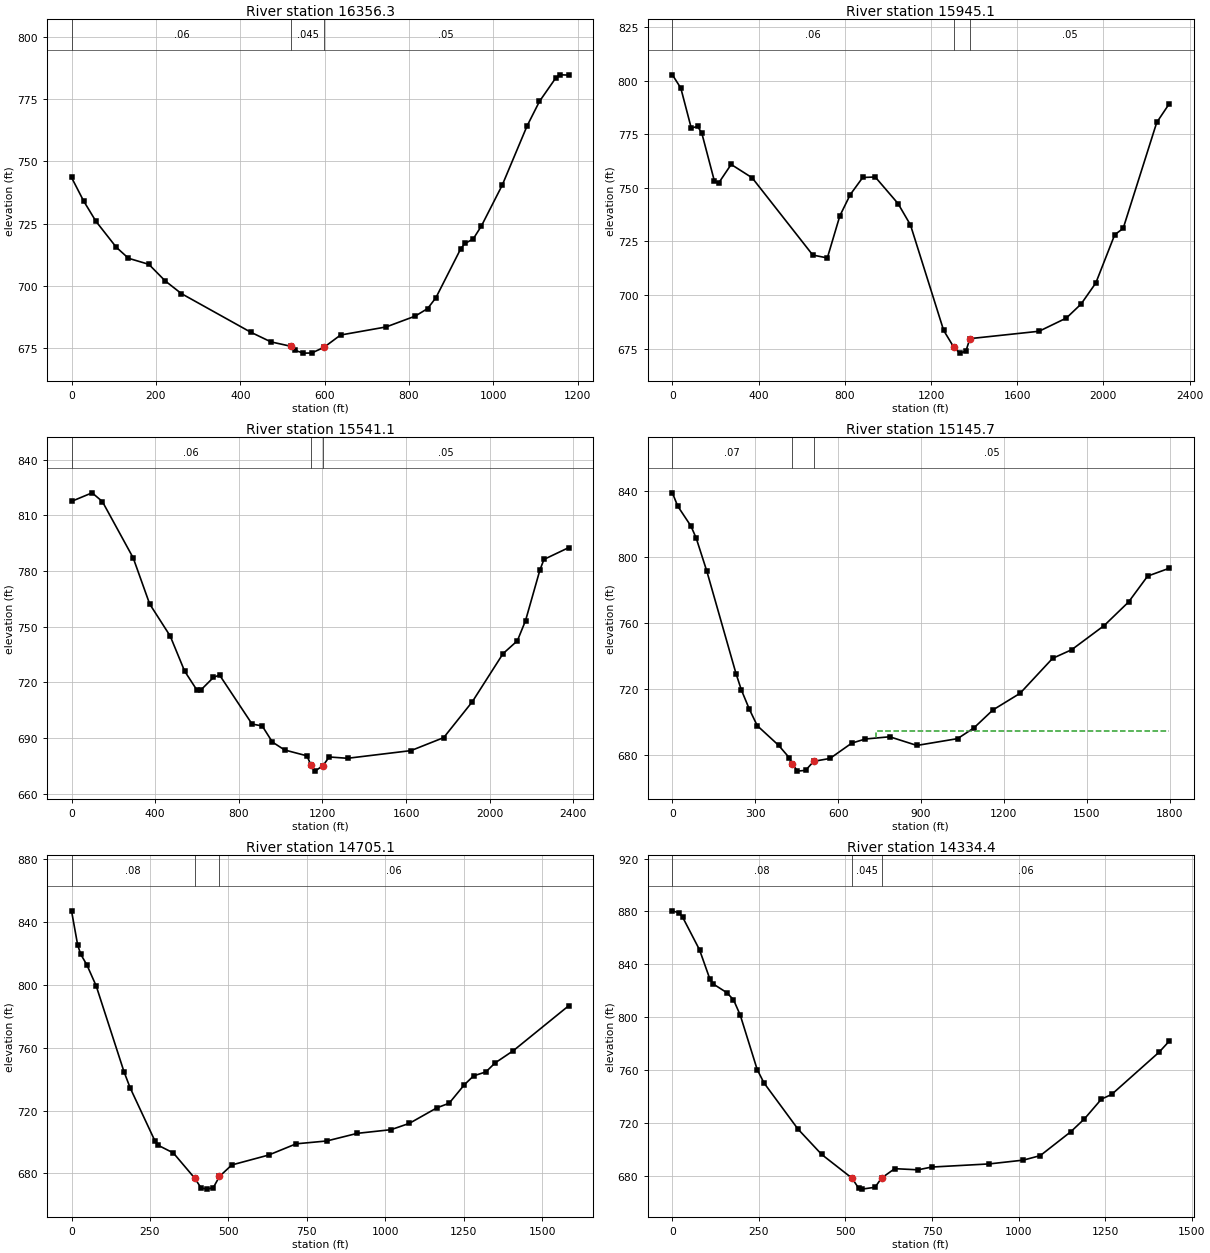
Type RM Length L Ch R = 1 ,16356.3 ,410.8,411.2,411.6
XS GIS Cut Line= 4
     1870830.834      683008.873     1870523.542      683342.206
     1870440.209      683435.956     1870723.501      683963.972
#Sta/Elev= 30
       0  743.54    28.9  734.02    57.9   725.9   106.1  715.47     135  711.04
   183.3   708.6   221.9  701.96   260.4  696.84   424.4  681.35   472.7  677.42
   520.9  675.62   530.6  673.96   549.8   672.9   569.2  672.94   598.4  675.23
   637.7  680.18   745.8  683.43   814.6  687.78     844   690.8   863.7  695.18
   922.6  714.87   932.4  716.98   952.1  718.79   971.7  724.07  1020.8   740.4
  1079.8  764.24  1109.2  774.12  1148.5  783.71  1158.4   784.8    1178   784.7
#Mann= 3 , 0 , 0
       0     .06       0   520.9    .045       0   598.4     .05       0
Bank Sta=520.9,598.4
XS Rating Curve= 0 ,0
Exp/Cntr=0.3,0.1

Type RM Length L Ch R = 1 ,15945.1 ,420.4,403.9,387.4
XS GIS Cut Line= 6
     1870813.129      681994.276     1870711.111      682500.255
     1870438.315      682826.207     1870218.855      683068.768
     1870130.313      683165.123     1870630.768      683921.485
#Sta/Elev= 30
       0  802.77      39  796.62    87.6  777.92   116.9   778.7   136.3  775.65
   194.8  753.27   214.3  752.21   272.7  760.96   370.1  754.72   651.4  718.67
     719  717.32     777  736.94   825.3  746.87   883.2  754.86   941.2   755.1
    1047   742.7  1104.8  732.71  1258.7  683.52  1305.7  675.68  1333.7   672.9
  1361.8  673.78  1380.5  679.66  1701.5  683.11  1828.3  689.28  1896.5  695.81
  1964.8  705.63  2052.6  728.18  2091.6  731.06  2247.6  780.57  2306.1  789.34
#Mann= 3 , 0 , 0
       0     .06       0  1305.7    .045       0  1380.5     .05       0
Bank Sta=1305.7,1380.5
XS Rating Curve= 0 ,0
Exp/Cntr=0.3,0.1

Type RM Length L Ch R = 1 ,15541.1 ,410.5,395.5,380.4
XS GIS Cut Line= 5
     1869602.191      681807.644     1869859.517      682446.211
     1869836.042      682873.456     1869833.438      683008.873
     1870527.821      683894.219
#Sta/Elev= 30
       0   817.5    98.4  822.11   147.5  817.43   295.1  787.02   373.7  762.22
   472.1   744.9   540.9  726.03     600  715.76   619.6  715.95   678.6  722.59
   707.9  723.94   863.5  697.49   912.1  696.46   960.8  687.78  1019.1  683.53
    1126  680.36  1145.4  675.34  1164.7  672.12  1203.4  675.15  1232.4  679.75
  1320.3  679.04  1623.6  683.18  1780.1  690.18  1917.1  709.54  2063.9  735.44
  2132.4  742.37  2171.5  753.23    2240  780.42  2259.6  786.23    2377  792.52
#Mann= 3 , 0 , 0
       0     .06       0  1145.4    .045       0  1203.4     .05       0
Bank Sta=1145.4,1203.4
XS Rating Curve= 0 ,0
Exp/Cntr=0.3,0.1

Type RM Length L Ch R = 1 ,15145.7 ,462.4,440.5,418.3
XS GIS Cut Line= 4
     1869222.327      682506.268     1869381.181      682823.977
     1869474.262      682949.625     1870414.601      683829.185
#Sta/Elev= 30
       0  838.94    19.2  830.92    67.2  818.82    86.4  811.45   124.8  791.44
   230.4   729.5   249.6  719.68   278.4  708.05   307.2     698   384.5  686.11
   423.6  678.51   433.4  675.08   452.9  670.48   482.3  670.96   511.6  676.41
   570.6  678.16   649.2  687.42   698.3  689.92   786.8  691.27   885.1  686.03
  1032.5  690.15  1091.5  696.62  1160.3   707.5  1258.6  717.57  1376.5  738.75
  1445.3  743.94  1563.3  758.61  1651.7  772.89  1720.5  788.53  1799.2  793.31
#Mann= 3 , 0 , 0
       0     .07       0   433.4    .045       0   511.6     .05       0
#XS Ineff= 2 , 0
                          735.79          694.85
Permanent Ineff=
       F       F
Bank Sta=433.4,511.6
XS Rating Curve= 0 ,0
Exp/Cntr=0.3,0.1

Type RM Length L Ch R = 1 ,14705.1 ,370.8,370.7,370.8
XS GIS Cut Line= 4
     1868891.598      683264.081     1869185.868      683243.248
      1869430.66      683230.227     1870320.851      683774.498
#Sta/Elev= 30
       0  847.23    19.7  825.35    29.5  819.52    49.2  812.66    78.7  799.34
   167.2  744.72   186.8  734.44   265.5  700.73   275.3  697.91   324.4  692.96
   393.1  676.75   412.7  670.66   432.3   669.9   451.9   670.9   471.5  678.01
   510.7   685.3   627.9   691.6   715.7  698.77   813.2  700.58   910.7  705.45
    1018  707.78  1076.5  711.81  1164.2  721.71  1203.2  724.63    1252  736.49
  1281.2  742.08  1320.2  744.58  1349.5  750.29    1408  758.16  1583.5  786.64
#Mann= 3 , 0 , 0
       0     .08       0   393.1    .045       0   471.5     .06       0
Bank Sta=393.1,471.5
XS Rating Curve= 0 ,0
Exp/Cntr=0.3,0.1

Type RM Length L Ch R = 1 ,14334.4 ,271.8,259.6,247.4
XS GIS Cut Line= 4
     1868896.372      683579.185     1869396.372      683586.998
     1869576.059      683576.581     1870303.056       683782.31
#Sta/Elev= 30
       0  880.44    19.6  878.84    29.4  875.74    78.4  850.97   107.9  829.11
   117.7  825.14   156.9   818.6   176.5   813.2   196.1  801.48   245.1  760.29
   264.7  750.22   362.8  715.33   431.4   696.1     519  678.17     538   670.6
   547.4   669.9   585.3  671.29   604.3  678.28   642.2  685.38   709.5  684.51
   748.7  686.59   915.5  688.98  1013.7  691.84  1062.7  695.26    1151  713.34
  1190.3  723.07  1239.4  738.02  1268.8  741.52  1406.2  773.57  1435.6  781.96
#Mann= 3 , 0 , 0
       0     .08       0     519    .045       0   604.3     .06       0
Bank Sta=519,604.3
XS Rating Curve= 0 ,0
Exp/Cntr=0.3,0.1

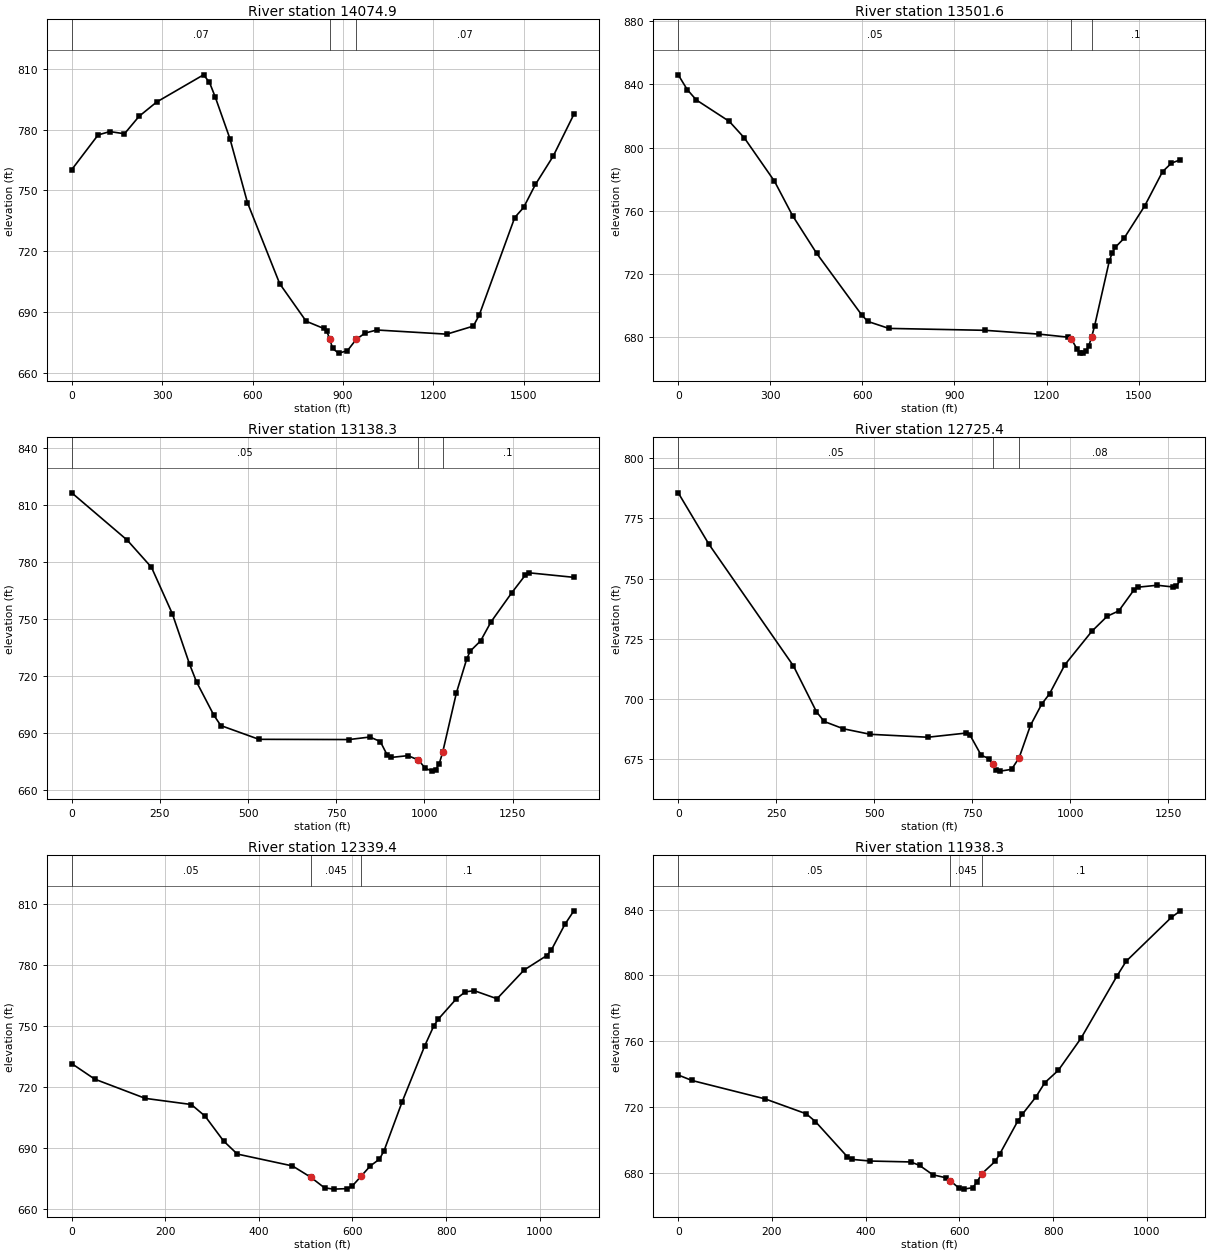
Type RM Length L Ch R = 1 ,14074.9 ,576.3,573.3,570
XS GIS Cut Line= 5
     1868728.403      683852.623     1869415.469      683914.689
      1869682.83      683735.435      1869895.07      683721.546
     1870329.098      683801.841
#Sta/Elev= 30
       0  760.29    87.4  777.35   126.3     779   174.9  777.92   223.5  786.54
   281.8  793.56   437.2  806.94   456.7  803.29   476.1  795.98   524.7  775.54
     583  743.98   689.9   704.1   777.6  685.63   836.2  682.05   845.9   680.7
   855.7  677.03   865.4   672.2     885  669.92   914.2  671.06   943.5  676.64
   972.7  679.77  1011.8  681.31  1244.1  679.26  1332.3  683.22    1352   688.7
  1469.7  736.69  1499.1  741.62  1538.3  752.95  1597.2  766.88  1665.8  787.46
#Mann= 3 , 0 , 0
       0     .07       0   855.7    .045       0   943.5     .07       0
Bank Sta=855.7,943.5
XS Rating Curve= 0 ,0
Exp/Cntr=0.3,0.1

Type RM Length L Ch R = 1 ,13501.6 ,355.7,363.3,373.2
XS GIS Cut Line= 4
      1868988.82       684594.81     1870001.631      683959.264
     1870158.091      683821.373     1870387.257      683855.227
#Sta/Elev= 30
       0  846.01    29.4  836.64    58.8  830.15   166.6  816.54   215.6  806.07
   313.6  778.74   372.4  757.04   450.8  733.22   597.8  694.23   617.4  690.14
   686.1  685.71   999.7   684.5  1176.1  682.08  1271.5  680.14    1281  679.03
    1300  672.39  1309.5   670.4  1318.9  670.08  1328.4  671.25  1337.9  674.84
  1347.4  680.54  1356.9  687.54  1404.2  728.03  1413.9  733.42  1423.6  736.89
  1452.5  742.65  1520.1  763.21    1578  784.79    1607  790.19  1635.9   792.3
#Mann= 3 , 0 , 0
       0     .05       0    1281    .045       0  1347.4      .1       0
Bank Sta=1281,1347.4
XS Rating Curve= 0 ,0
Exp/Cntr=0.3,0.1

Type RM Length L Ch R = 1 ,13138.3 ,407.7,412.9,415.9
XS GIS Cut Line= 3
     1869316.077      684585.261     1870262.838       684200.05
     1870647.674       684086.13
#Sta/Elev= 30
       0  816.55   157.2  791.63     226  777.31     285  752.92   334.2  726.17
   353.8  716.94     403  699.37   422.6  693.97   530.7  686.72   786.2   686.6
   845.2  687.94   874.7  685.57   894.4  678.42   904.2  677.16   953.3  678.12
   982.8  675.82  1002.5  671.44  1022.1  669.97  1031.9  670.75  1041.7  673.82
  1051.5  679.84  1090.6  711.25    1120  729.16  1129.8  733.19  1159.2  738.58
  1188.5  748.53  1247.3  763.87  1286.4  773.32  1296.2  774.43  1423.5  772.04
#Mann= 3 , 0 , 0
       0     .05       0   982.8    .045       0  1051.5      .1       0
Bank Sta=982.8,1051.5
XS Rating Curve= 0 ,0
Exp/Cntr=0.3,0.1

Type RM Length L Ch R = 1 ,12725.4 ,382.6,385.9,389.2
XS GIS Cut Line= 4
     1869573.021      684717.206     1870260.521      684613.039
     1870489.647      684577.227      1870836.91      684512.345
#Sta/Elev= 30
       0  785.67    78.4  764.25   293.8  713.67   352.6  694.58   372.2  690.56
   421.1  687.52   489.7  685.22   636.6     684     734  685.73   743.7  685.03
   772.6  676.51     792  675.14   801.6  672.66   811.3  670.48     821   669.9
     850  670.63   869.3  675.41   898.3  688.92   927.2  697.82   946.9  702.05
   986.1  714.16  1054.8  728.06  1094.1  734.34  1123.5  736.55  1162.8  745.39
  1172.6  746.42  1221.6  747.22  1260.9  746.53  1270.7  747.01  1280.5  749.22
#Mann= 3 , 0 , 0
       0     .05       0   801.6    .045       0   869.3     .08       0
Bank Sta=801.6,869.3
XS Rating Curve= 0 ,0
Exp/Cntr=0.3,0.1

Type RM Length L Ch R = 1 ,12339.4 ,393.1,401.1,409.4
XS GIS Cut Line= 4
      1869805.66      684988.039     1870267.466      684979.725
     1870482.743      684977.623     1870878.577      684984.567
#Sta/Elev= 30
       0   731.5    49.1  723.88   157.2  714.44   255.5  711.43     285   705.7
   324.3  693.57   353.8  687.11   471.7  681.28   510.8  675.74   540.2  670.53
   559.7   669.9   589.1  670.15   598.9  671.27   618.4  676.24     638  681.27
   657.6  684.61   667.4  688.72   706.1  712.73   754.4  740.23   773.7  749.98
   783.4  753.34     822  763.32   841.3  766.76   860.6  767.27   908.9  763.34
   966.8  777.44  1015.1  784.52  1024.8  787.16  1053.8  799.79  1073.1  806.49
#Mann= 3 , 0 , 0
       0     .05       0   510.8    .045       0   618.4      .1       0
Bank Sta=510.8,618.4
XS Rating Curve= 0 ,0
Exp/Cntr=0.3,0.1

Type RM Length L Ch R = 1 ,11938.3 ,387.3,400,407.6
XS GIS Cut Line= 4
     1869777.882      685165.123     1870217.247       685326.53
     1870358.857      685376.736      1870782.89      685535.838
#Sta/Elev= 30
       0  739.36    29.2  736.03   185.3  724.82     273  715.76   292.6  711.05
   360.8  689.59   370.6     688   409.6     687   496.2  686.44     515  684.32
   543.2  678.63   571.4   676.8   580.8  674.91   599.5  670.39   608.9   669.9
     628  670.76   637.6  674.26   647.2  679.13   676.1  686.76   685.8  691.19
   724.3  711.26     734   715.4   762.9  725.92   782.1  734.68     811  742.23
   859.2  761.66   936.3  799.72   955.6  808.58    1052  835.25  1071.2  839.28
#Mann= 3 , 0 , 0
       0     .05       0   580.8    .045       0   647.2      .1       0
Bank Sta=580.8,647.2
XS Rating Curve= 0 ,0
Exp/Cntr=0.3,0.1

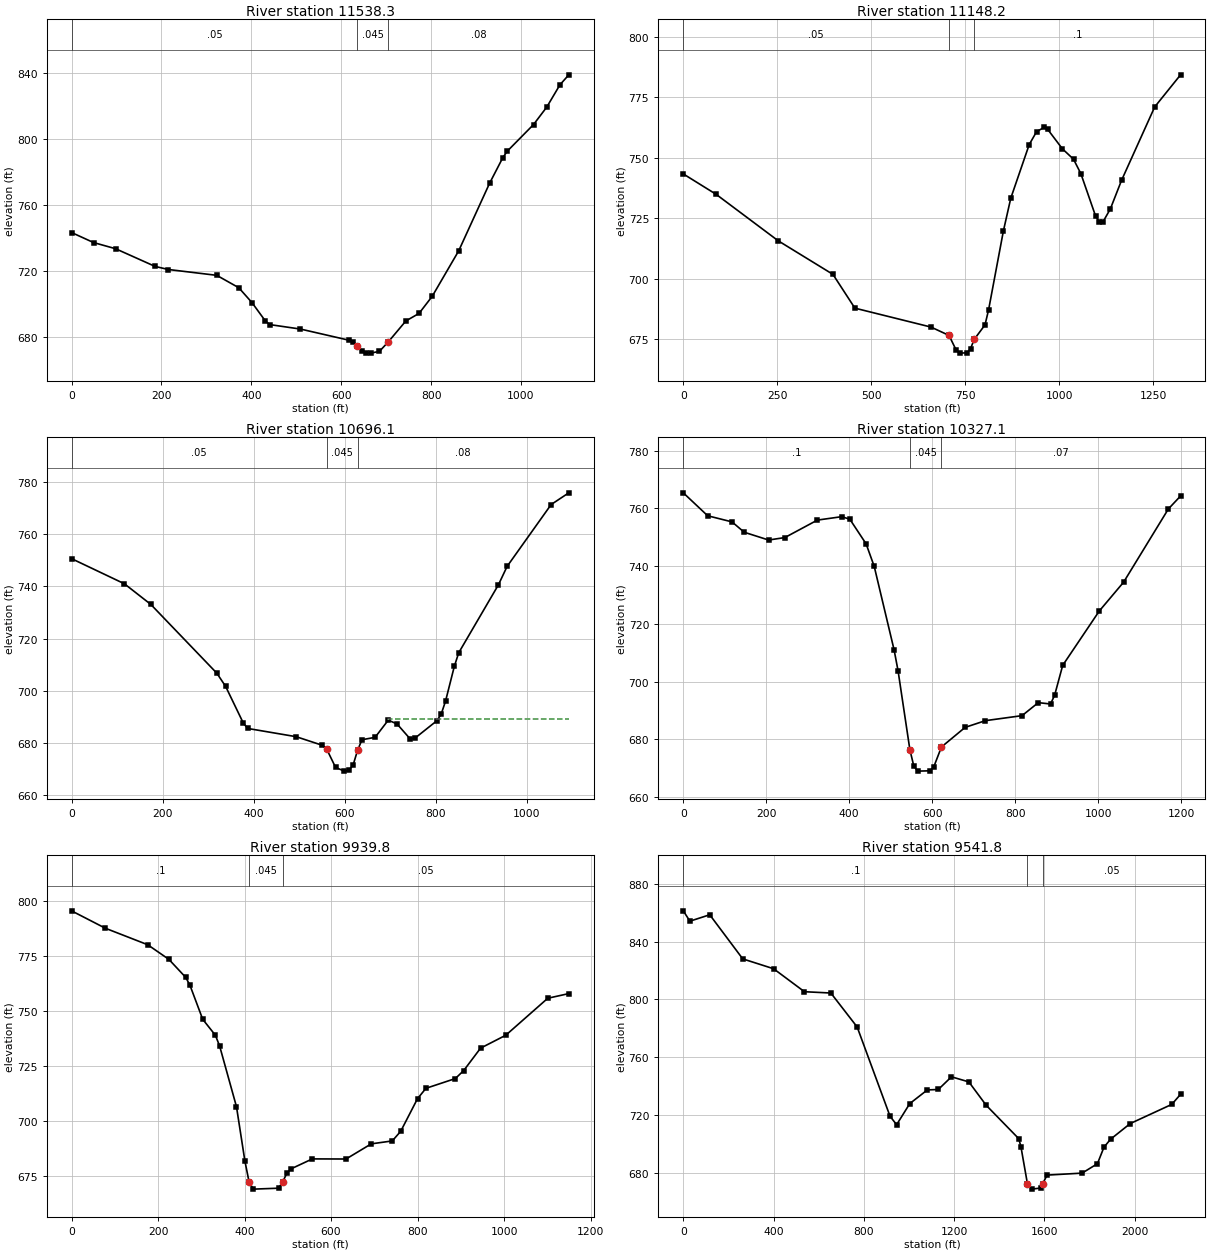
Type RM Length L Ch R = 1 ,11538.3 ,380.6,390.1,404.2
XS GIS Cut Line= 4
     1869750.105      685244.984     1870098.451      685616.356
     1870195.228      685738.957     1870533.341       686022.06
#Sta/Elev= 30
       0  743.27      49  737.16    97.9  733.42     186  722.64   215.4  720.77
   323.1  717.22   372.1  709.69   401.5  700.63   430.8  689.64   440.6  687.27
   509.2  684.55   616.6   677.8   626.3  676.97   636.1  674.52   645.8  671.43
   655.6  670.09   665.4   669.9     685  670.96   704.6  676.68   743.8  689.45
   773.2  694.06   802.6   704.5   861.4  732.11     930  773.14   959.4   788.7
   969.2  792.66    1028  808.96  1057.4  819.58  1086.8  833.16  1106.4  839.19
#Mann= 3 , 0 , 0
       0     .05       0   636.1    .045       0   704.6     .08       0
Bank Sta=636.1,704.6
XS Rating Curve= 0 ,0
Exp/Cntr=0.3,0.1

Type RM Length L Ch R = 1 ,11148.2 ,431.9,452.1,471.9
XS GIS Cut Line= 4
     1869732.743      685300.539     1869875.616      685835.155
     1869941.077      686085.261     1870073.021      686578.317
#Sta/Elev= 30
       0  743.35    87.4   734.9   252.4  715.68     398  701.78   456.3  687.81
   658.7  679.98   706.6  676.53   725.7  670.43   735.3   669.2   754.5  669.33
     764  671.11   773.6  674.88   802.3  680.89   811.9  687.16   851.2  719.75
   870.8  733.27   919.9  755.51   939.5  760.84   959.1  762.57     969  761.78
  1008.2  753.72  1037.7  749.43  1057.3  743.42  1096.6  725.81  1106.4  723.54
  1116.2  723.55  1135.8  728.93  1165.3  740.66  1253.6  771.08  1322.3  784.35
#Mann= 3 , 0 , 0
       0     .05       0   706.6    .045       0   773.6      .1       0
Bank Sta=706.6,773.6
XS Rating Curve= 0 ,0
Exp/Cntr=0.3,0.1

Type RM Length L Ch R = 1 ,10696.1 ,381.2,369,357
XS GIS Cut Line= 4
     1869687.605      685279.706     1869595.554       685764.62
      1869493.16      685904.706     1869291.771      686279.706
#Sta/Elev= 30
       0  750.64   116.1  741.01   174.2   733.1   319.4  706.72   338.7  701.65
   377.4  687.66   387.1  685.56   493.6   682.4   551.4  679.09     561  677.55
   580.3  670.61   599.6   669.2   609.2  669.47   618.9  671.59   628.5  677.11
   638.2  681.23   667.1  682.15   696.1  688.75   715.5  687.25   744.5  681.48
   754.2  681.76   802.5  688.46   812.2  690.96   821.9  696.01   841.2  709.33
   850.9  714.56     938  740.56   957.3  747.68    1054  771.37  1092.8  775.86
#Mann= 3 , 0 , 0
       0     .05       0     561    .045       0   628.5     .08       0
#XS Ineff= 2 , 0
                          696.32          689.12
Permanent Ineff=
       F       F
Bank Sta=561,628.5
XS Rating Curve= 0 ,0
Exp/Cntr=0.3,0.1

Type RM Length L Ch R = 1 ,10327.1 ,395.5,387.2,378.9
XS GIS Cut Line= 4
     1869281.355        685067.9     1869245.861      685536.654
     1869225.799      685744.984      1869180.66      686262.345
#Sta/Elev= 30
       0  765.42    58.8  757.47   117.5  755.35   146.9  751.76   205.7  749.07
   244.8  749.92   323.2  755.97     382  757.16   401.5  756.27   440.7  747.74
   460.3  739.91   508.2  710.99   517.7   703.8   546.2  676.43   555.7  670.73
   565.2     669   593.8  669.11   603.3  670.28   622.3  677.36   679.4  684.16
   728.4  686.49   816.6  688.22   855.8  692.73   885.2  692.26     895  695.22
   914.6  705.64  1002.7  724.46  1061.5  734.48  1169.3  759.83  1198.7  764.32
#Mann= 3 , 0 , 0
       0      .1       0   546.2    .045       0   622.3     .07       0
Bank Sta=546.2,622.3
XS Rating Curve= 0 ,0
Exp/Cntr=0.3,0.1

Type RM Length L Ch R = 1 ,9939.8  ,399.1,398.1,397
XS GIS Cut Line= 4
     1868738.393      685322.037     1868833.438      685640.817
     1868912.146      685922.401     1869048.716      686429.011
#Sta/Elev= 30
       0  795.32    78.3  787.41   176.1  779.93     225   773.3   264.2  765.07
     274  761.43   303.3  746.08   332.6  738.85   342.4  733.97   381.4  706.39
   400.9  681.67   410.6  672.18   420.4     669   478.8  669.42   488.6  672.43
   498.3  676.42   508.1  678.26   556.8  682.72   634.7  682.67     693  689.55
   741.6  690.88   761.1  695.26   799.9  710.05   819.4  714.76   887.4  719.19
   906.8  722.84   945.7  732.99    1004  738.85  1101.1  755.64  1149.7  757.75
#Mann= 3 , 0 , 0
       0      .1       0   410.6    .045       0   488.6     .05       0
Bank Sta=410.6,488.6
XS Rating Curve= 0 ,0
Exp/Cntr=0.3,0.1

Type RM Length L Ch R = 1 ,9541.8  ,227.9,219.1,210.2
XS GIS Cut Line= 6
     1867573.545      684650.526     1867958.681      685154.814
     1868386.824      685564.831     1868443.455      685747.732
     1868510.521      685949.845     1868694.549      686491.511
#Sta/Elev= 30
       0  861.22    29.3  854.07   117.2   858.5   263.6  828.02   400.2  821.22
   536.9  805.35     654  804.45   770.6  780.98   916.4  719.28   945.5  713.51
  1003.8  728.08  1081.6  737.52  1130.2  737.82  1188.5  746.58  1265.6  743.06
  1342.2  726.95  1486.6  703.87  1496.2  698.44  1525.3  672.64  1544.6     669
  1583.4  669.75    1593  672.85  1612.4  678.69  1767.5  680.06  1835.4  686.56
  1864.5  697.98  1893.6  703.46  1980.8  714.29    2165  727.54  2203.8  734.48
#Mann= 3 , 0 , 0
       0      .1       0  1525.3    .045       0    1593     .05       0
Bank Sta=1525.3,1593
XS Rating Curve= 0 ,0
Exp/Cntr=0.3,0.1

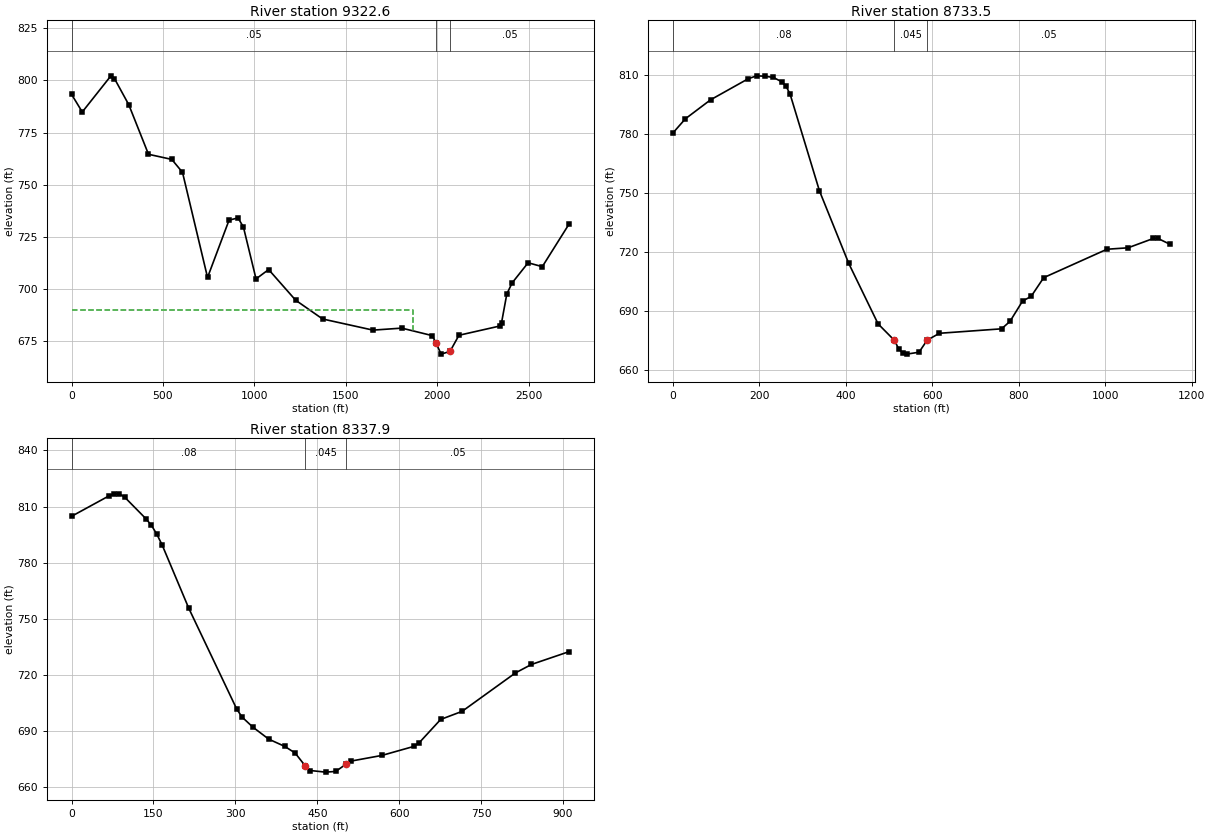
Type RM Length L Ch R = 1 ,9322.6  ,597.9,589.2,580.1
XS GIS Cut Line= 6
     1866324.413       686032.47     1867163.867       685969.52
      1868001.39      685847.635      1868207.57      685834.393
     1868345.591      685998.456     1868548.716      686574.845
#Sta/Elev= 30
       0  793.37    58.7   784.9   215.4  802.24   234.9  800.91   313.2  788.37
   420.9  764.62   548.2  762.17   606.9  755.96   743.9  705.55   861.5  733.04
   910.7  734.12   940.2   729.7  1009.1  704.86    1078  709.35  1225.6  694.66
  1373.2  685.65  1648.8  680.31  1806.2  681.27  1972.7  677.68  1992.2  674.37
  2021.4   668.8  2070.2  670.11  2118.9  677.84    2342  682.27  2351.7  683.77
  2380.8  697.66  2409.9  702.96  2497.2   712.6  2574.8  710.74  2720.3  731.05
#Mann= 3 , 0 , 0
       0     .05       0  1992.2    .045       0  2070.2     .05       0
#XS Ineff= 2 , 0
         1866.22   689.8
Permanent Ineff=
       F       F
Bank Sta=1992.2,2070.2
XS Rating Curve= 0 ,0
Exp/Cntr=0.3,0.1

Type RM Length L Ch R = 1 ,8733.5  ,405.1,395.5,385.7
XS GIS Cut Line= 4
     1867397.674      686172.935     1867853.403      686305.748
     1868055.777       686408.68     1868454.966      686613.039
#Sta/Elev= 30
       0  780.41    29.1  787.68    87.2  797.32   174.4  808.06   193.8  809.54
   213.1  809.33   232.5  808.72   251.9   806.5   261.6  804.38   271.2  800.21
   339.1  750.99   406.9  714.03   474.7  683.29   512.5  674.89     522  670.74
   531.4  668.45   540.9   667.9   569.3  668.87   588.2  675.01   616.6  678.51
   760.2  680.78   779.7  684.55     809  694.97   828.5  697.24   857.7  706.82
    1004  721.28  1052.7  722.01  1111.2  726.77  1120.9  726.88  1150.2  723.75
#Mann= 3 , 0 , 0
       0     .08       0   512.5    .045       0   588.2     .05       0
Bank Sta=512.5,588.2
XS Rating Curve= 0 ,0
Exp/Cntr=0.3,0.1

Type RM Length L Ch R = 1 ,8337.9  ,223.9,221.1,218.3
XS GIS Cut Line= 4
      1867377.98      686706.789     1867777.882       686719.81
     1867926.398      686725.873     1868287.987      686742.063
#Sta/Elev= 30
       0  804.76    68.3  815.66    78.1  816.78    87.8   816.8    97.6  814.92
   136.6  803.35   146.4   799.9   156.1  795.22   165.9  789.45   214.7  755.55
   302.5  701.62   312.3  697.34   331.8  692.03   361.1  685.54   390.4  681.67
   409.4  678.13     428  671.21   437.3  668.76   465.1   667.9   483.7  668.26
   502.3   672.1   511.6   673.8   568.3  676.84     627  681.68   636.8  683.69
   675.9  696.09   715.1  700.41   812.9     721   842.2  725.52   910.7  732.33
#Mann= 3 , 0 , 0
       0     .08       0     428    .045       0   502.3     .05       0
Bank Sta=428,502.3
XS Rating Curve= 0 ,0
Exp/Cntr=0.3,0.1