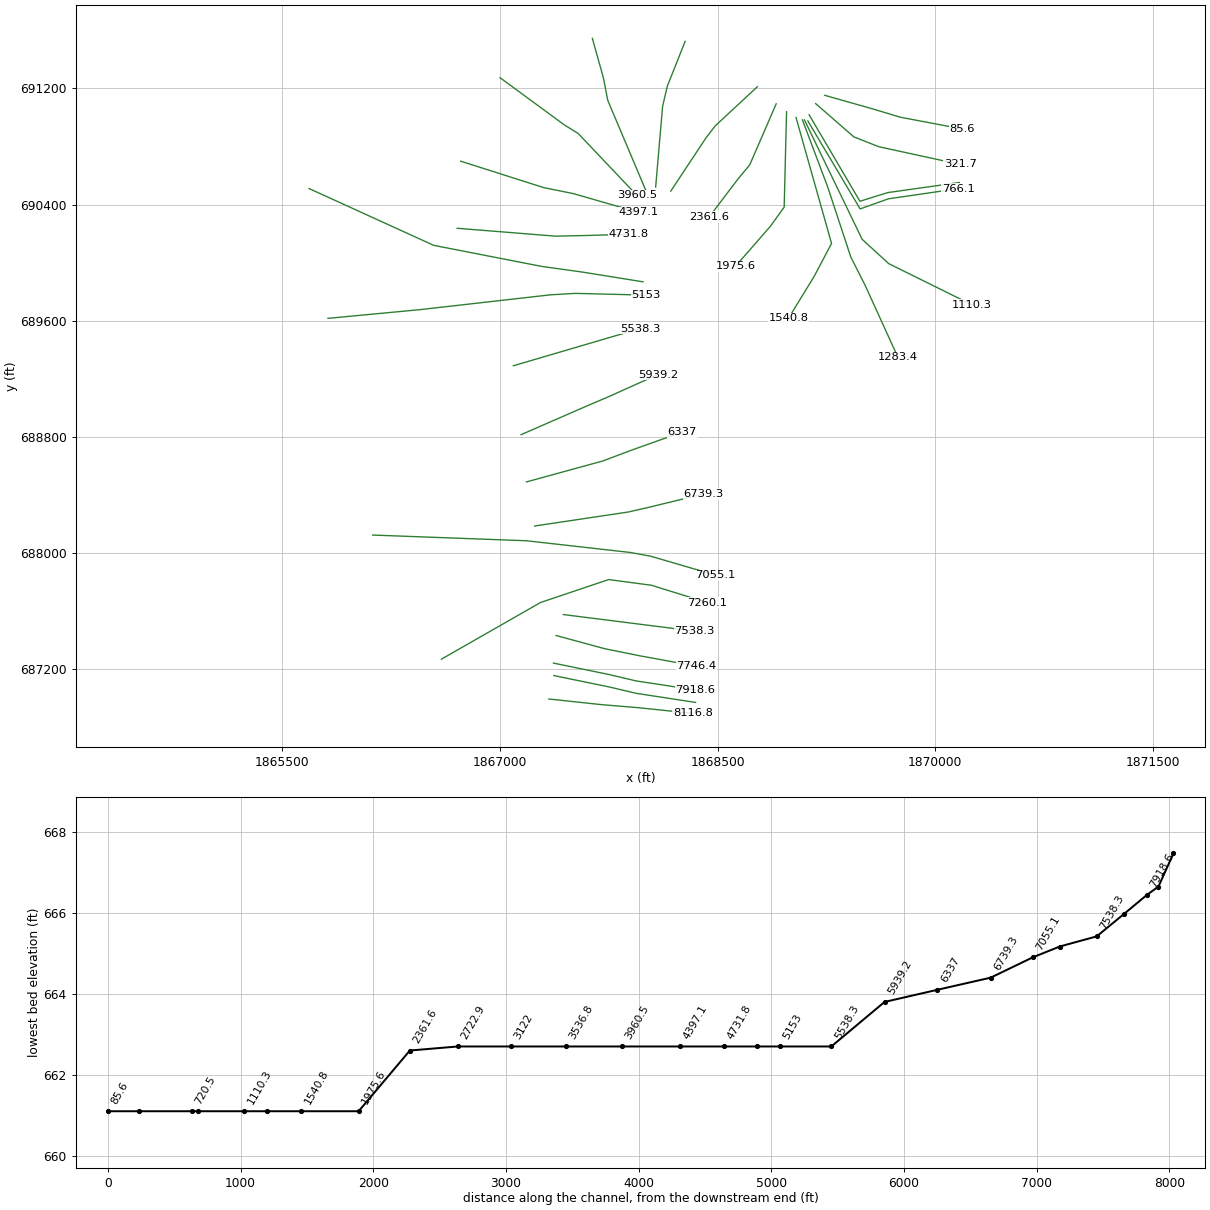
HEC-RAS study SpringCrk2.prj: SpringCrk2

--- SpringCrk2.g01 (geometry) --- (continued)

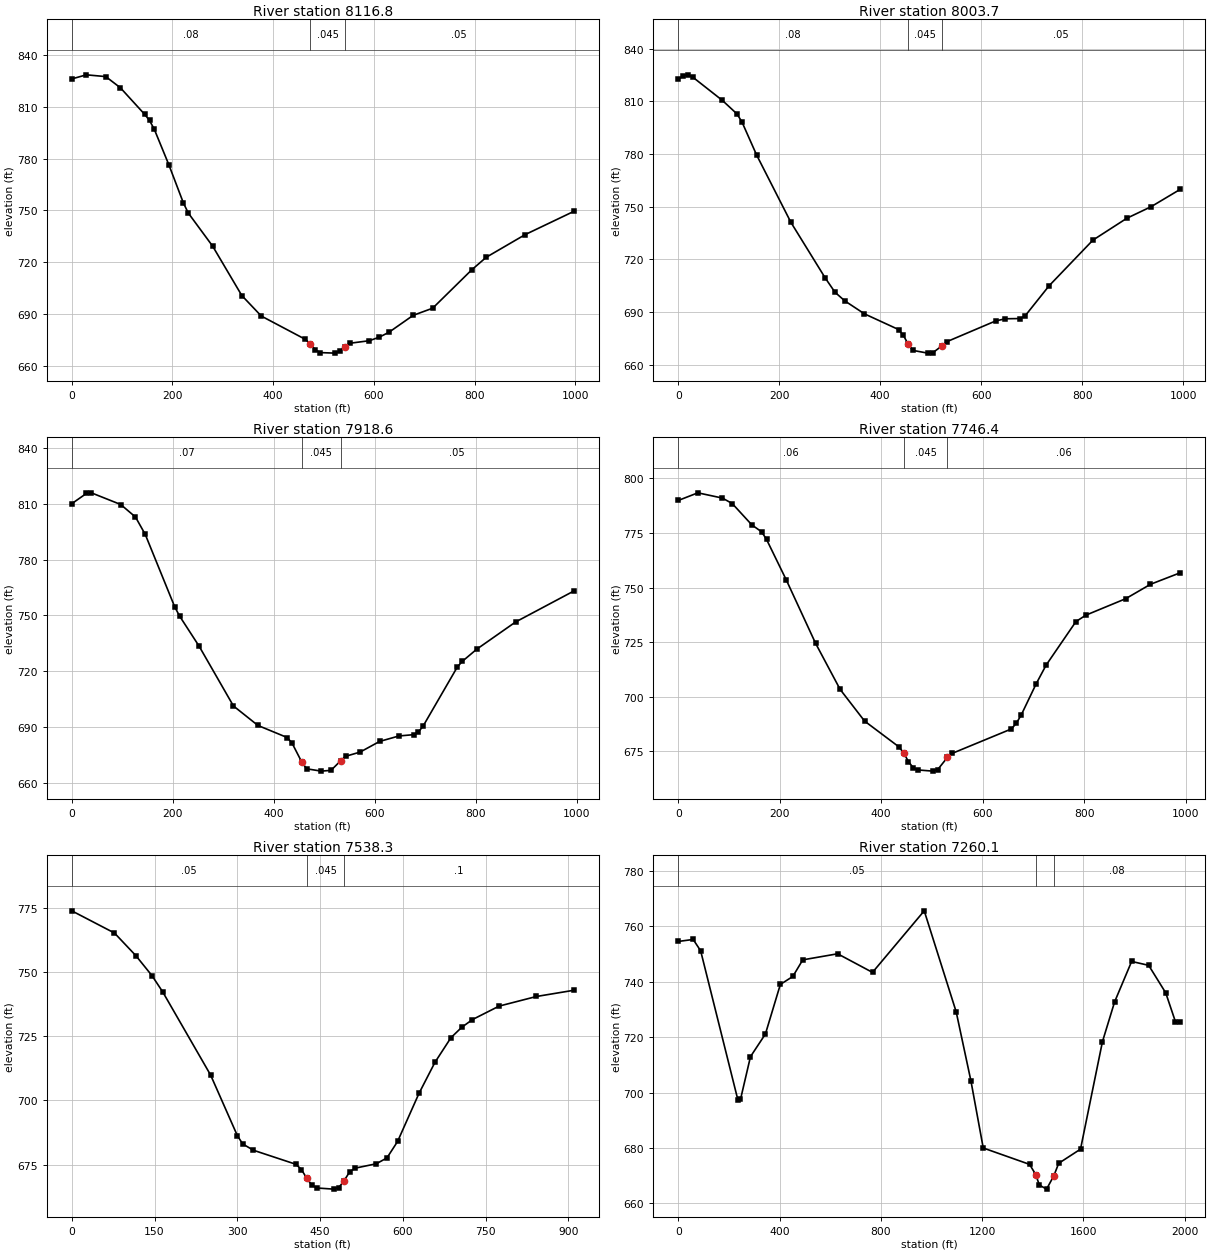
Type RM Length L Ch R = 1 ,8116.8  ,116.6,113.1,109.7
XS GIS Cut Line= 4
     1867337.778      686993.248     1867702.361      686954.185
     1867954.966      686933.352     1868329.966      686894.289
#Sta/Elev= 30
       0  826.12      29  828.49    67.5  827.47    96.5  821.02   144.7  805.65
   154.4   802.1     164  796.92     193  776.32   221.9  754.21   231.6  748.45
   279.8  729.36   337.7  700.81   376.4  688.93   464.2   675.4   473.9  672.78
   483.6  669.43   493.4  667.78   522.6  667.47   532.4  668.54   542.1  671.16
   551.9  673.17   590.9  674.65   610.4  676.66   629.8   679.5   678.1  689.34
   716.8  693.46   794.2  715.61   823.2  722.93   900.5  736.04   997.2  749.49
#Mann= 3 , 0 , 0
       0     .08       0   473.9    .045       0   542.1     .05       0
Bank Sta=473.9,542.1
XS Rating Curve= 0 ,0
Exp/Cntr=0.3,0.1

Type RM Length L Ch R = 1 ,8003.7  ,85,85.1,85.2
XS GIS Cut Line= 4
     1867371.632      687154.706     1867751.841      687076.581
     1867939.341       687032.31     1868348.195       686969.81
#Sta/Elev= 30
       0  822.53     9.7  824.65    19.4  825.13    29.1  823.74    87.3  810.59
   116.4  802.85   126.2  798.29   155.3  779.43   223.2  741.09   291.1  709.46
   310.5  701.31   329.9   696.4   368.7  689.03   436.3  680.09     446  676.74
   455.6  671.64   465.2  668.19   494.1  666.65   503.8   666.8     523  670.93
   532.6  673.24   628.9  685.01   648.1  686.22     677  686.34   686.6  687.72
   734.7  705.06   821.3     731   888.6  743.47   936.7  750.06   994.4  759.95
#Mann= 3 , 0 , 0
       0     .08       0   455.6    .045       0     523     .05       0
Bank Sta=455.6,523
XS Rating Curve= 0 ,0
Exp/Cntr=0.3,0.1

Type RM Length L Ch R = 1 ,7918.6  ,171.5,172.2,173
XS GIS Cut Line= 4
     1867369.028      687240.643     1867749.236      687162.518
     1867936.736      687118.248     1868345.591      687055.748
#Sta/Elev= 30
       0  810.02    29.1  815.54    38.8  815.85      97  809.57   126.2  802.85
   145.6  793.49   203.8  754.69   213.5   749.7   252.3  733.48   320.2  701.43
   368.7  690.97   426.7  684.48   436.3  681.48   455.6  671.27   465.2   667.7
   494.1  666.45   513.4  666.86   532.6  672.02   542.3   674.4   571.2  676.69
   609.7  682.39   648.1  685.33     677  686.02   686.6  687.42   696.2  690.79
   763.6  722.32   773.2  725.32     802  731.89     879  746.51   994.4  763.14
#Mann= 3 , 0 , 0
       0     .07       0   455.6    .045       0   532.6     .05       0
Bank Sta=455.6,532.6
XS Rating Curve= 0 ,0
Exp/Cntr=0.3,0.1

Type RM Length L Ch R = 1 ,7746.4  ,206.5,208.1,209.8
XS GIS Cut Line= 4
     1867387.257      687430.748     1867723.195      687339.602
     1867967.986      687290.123     1868353.403       687219.81
#Sta/Elev= 30
       0   789.9    38.7   793.4      87     791   106.4   788.5     145  778.74
   164.4  775.53     174  772.08   212.7  753.65   270.7   724.5   319.1   703.4
   367.3  688.89   434.5  677.17   444.1  674.46   453.7  670.35   463.4  667.46
     473  666.51   501.8  665.98   511.4  666.68   530.6  672.28   540.2  674.13
   656.6  685.29   666.4   687.9   676.2  691.76   705.6  706.02   725.2  714.55
   783.9  734.46   803.5  737.39   881.9  744.92   930.8  751.52   989.6  756.81
#Mann= 3 , 0 , 0
       0     .06       0   444.1    .045       0   530.6     .06       0
Bank Sta=444.1,530.6
XS Rating Curve= 0 ,0
Exp/Cntr=0.3,0.1

Type RM Length L Ch R = 1 ,7538.3  ,278.3,278.2,278
XS GIS Cut Line= 3
      1867437.36      687575.092     1867888.776      687518.098
     1868340.192      687461.105
#Sta/Elev= 30
       0  773.84    77.4  765.19   116.2  756.37   145.2  748.64   164.6  742.34
   251.7  709.84   300.1  686.27   309.8  683.02   329.2  680.57   406.6  675.07
   416.3  673.03     426  669.62   435.6  666.84   445.3  665.85   474.4  665.42
     484  666.04   493.7  668.74   503.4  672.05   513.1  673.57   551.8  675.29
   571.2  677.57   590.5  683.98   629.3  702.71   658.3  714.83   687.3  724.43
   706.7  728.44   726.1  731.46   774.5  736.72   842.2  740.47     910  742.89
#Mann= 3 , 0 , 0
       0     .05       0     426    .045       0   493.7      .1       0
Bank Sta=426,493.7
XS Rating Curve= 0 ,0
Exp/Cntr=0.3,0.1

Type RM Length L Ch R = 1 ,7260.1  ,206.2,205.1,203.9
XS GIS Cut Line= 5
     1866596.983      687267.714     1867279.936      687658.135
     1867749.236      687816.164     1868043.507      687777.102
     1868428.924       687657.31
#Sta/Elev= 30
       0  754.53      59  755.25    88.5  751.15     236  697.17   245.8  697.54
   285.2  712.96   344.2  721.14   403.2  739.03   452.3  741.89   491.7  747.89
   629.3  750.08     767  743.37   971.2  765.58  1097.4  729.13  1155.6  704.22
  1204.2  680.01  1387.2   674.1 1411.95  670.35  1425.5  666.66  1454.2  665.17
    1483  669.99  1502.1  674.48  1588.3   679.6  1674.8  718.35  1722.9  732.73
  1790.1  747.32  1857.4  745.91  1924.7  735.99  1963.1  725.56  1982.3  725.44
#Mann= 3 , 0 , 0
       0     .05       0 1411.95    .045       0    1483     .08       0
Bank Sta=1411.95,1483
XS Rating Curve= 0 ,0
Exp/Cntr=0.3,0.1

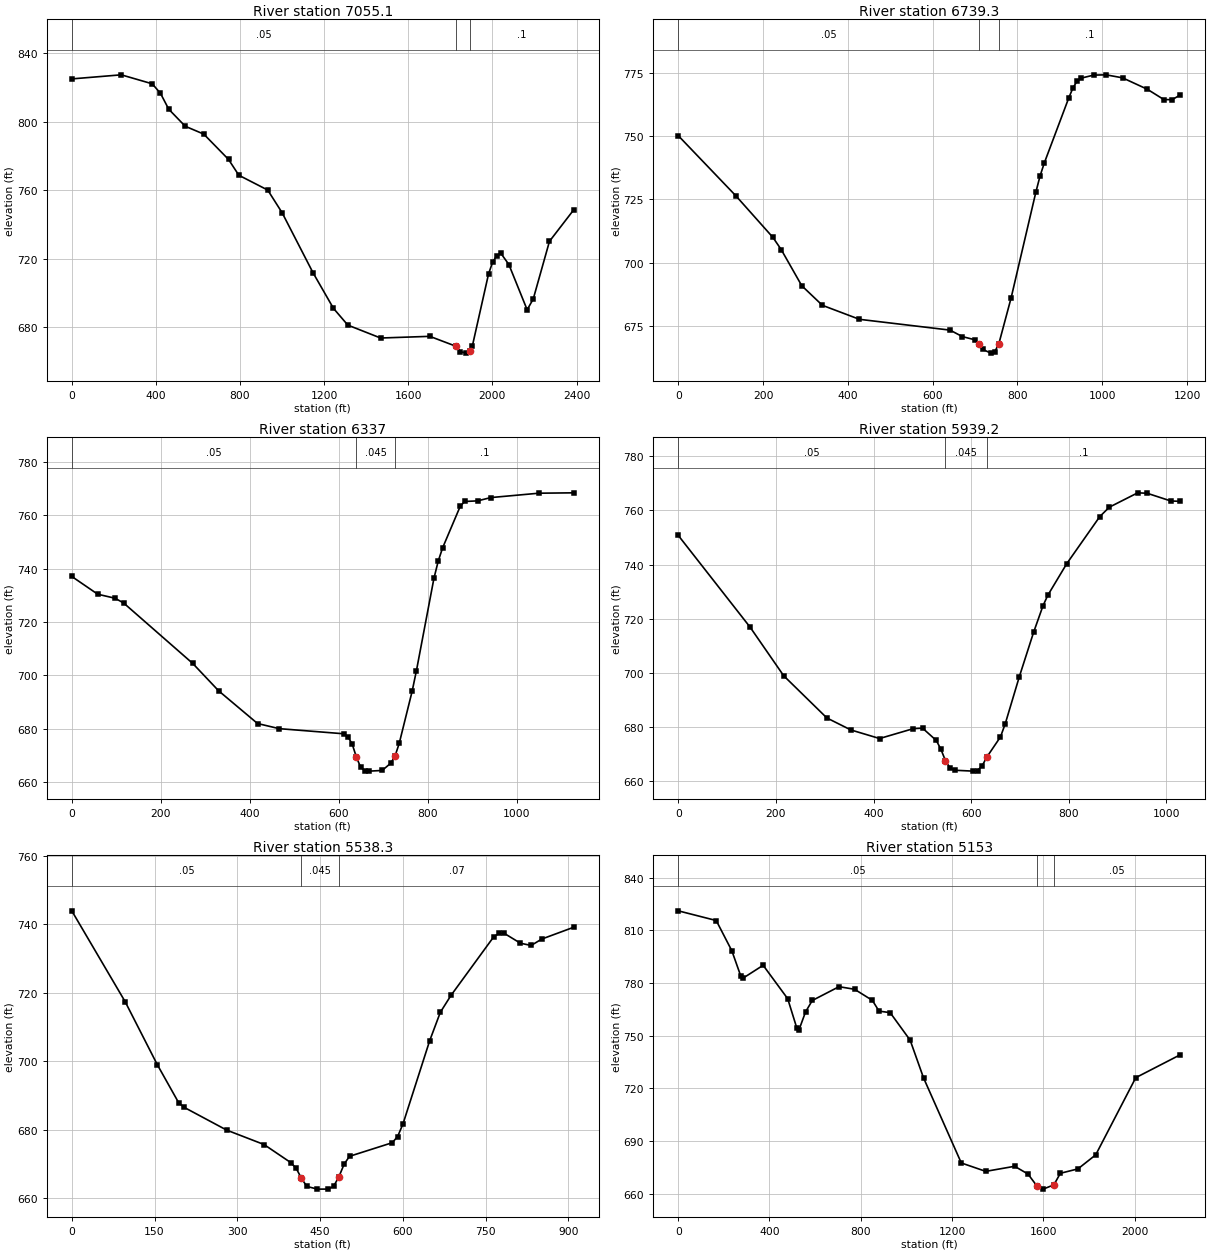
Type RM Length L Ch R = 1 ,7055.1  ,306.6,315.8,324.9
XS GIS Cut Line= 5
     1866123.892      688122.748     1867182.417      688083.564
     1867898.976      688002.796     1868040.035      687976.755
     1868484.914      687846.546
#Sta/Elev= 30
       0  824.99   235.4  827.37   382.5  822.13   421.7  816.59     461  807.31
   539.4  797.35   627.7  792.76   745.4  777.97   794.4  768.75   931.8  760.09
  1000.4  746.81    1147  711.85  1244.4  691.02  1312.6  681.26  1468.5  673.72
  1702.4   674.7  1828.2  668.84  1847.3  665.77    1876   664.9  1895.1  665.87
  1904.7  669.04  1981.7  711.14    2001  717.99  2020.4  721.79  2039.7  723.27
  2078.3  716.64  2165.2  690.22  2194.2  696.48  2271.4  730.18  2387.3  748.66
#Mann= 3 , 0 , 0
       0     .05       0  1828.2    .045       0  1895.1      .1       0
Bank Sta=1828.2,1895.1
XS Rating Curve= 0 ,0
Exp/Cntr=0.3,0.1

Type RM Length L Ch R = 1 ,6739.3  ,399.2,402.3,405.4
XS GIS Cut Line= 4
     1867239.254      688185.088     1867882.982      688281.376
     1868013.993      688310.956     1868401.739      688405.619
#Sta/Elev= 30
       0  750.15     136  726.41   223.4  710.01   242.9  705.22   291.4  690.97
     340  683.25   427.4  677.73   641.2  673.47   670.1  670.92   698.9  669.69
   708.4  667.88     718   665.9   737.2   664.4   746.8  664.98   756.4  668.19
   785.2  686.18   843.6   727.9   853.3  734.14   863.1   739.2   921.5  765.16
   931.2  769.01     941  771.69   950.7  772.83   979.9  774.01  1009.1  774.12
    1048  772.94  1106.4  768.44  1145.4  764.38  1164.9  764.31  1184.3   766.2
#Mann= 3 , 0 , 0
       0     .05       0   708.4    .045       0   756.4      .1       0
Bank Sta=708.4,756.4
XS Rating Curve= 0 ,0
Exp/Cntr=0.3,0.1

Type RM Length L Ch R = 1 ,6337    ,396.7,397.7,398.7
XS GIS Cut Line= 4
      1867182.83      688488.907     1867707.237      688632.618
     1867914.167      688710.261     1868256.599      688832.424
#Sta/Elev= 30
       0  737.06    58.3   730.4    97.1   728.9   116.5  727.12   271.9  704.45
   330.1  694.19   417.5  681.94   466.1  680.02     611   678.1   620.6  676.97
   630.2  674.23   639.8  669.27   649.4  665.46   659.1  664.21   668.7   664.1
   697.5  664.35   716.7  667.05   726.3  669.67   735.9  674.52   764.8  693.96
   774.6   701.8   813.9  736.37   823.7  742.92   833.5  747.83   872.8  763.28
   882.7  765.15   912.2  765.39   941.6  766.62  1049.7  768.26  1128.3   768.4
#Mann= 3 , 0 , 0
       0     .05       0   639.8    .045       0   726.3      .1       0
Bank Sta=639.8,726.3
XS Rating Curve= 0 ,0
Exp/Cntr=0.3,0.1

Type RM Length L Ch R = 1 ,5939.2  ,403.6,401,398.3
XS GIS Cut Line= 4
     1867145.938      688814.428     1867595.928      689010.749
     1867751.407      689077.015     1868087.238      689228.283
#Sta/Elev= 30
       0  750.79   147.3  716.89     216  698.99   304.4  683.42   353.5     679
   412.4  675.83   481.1  679.46   500.3  679.67   528.5  675.12   537.9   671.9
   547.3  667.65   556.7  664.93   566.1  664.13   603.6   663.8     613  664.03
   622.4  665.74   631.8  668.93     660  676.44   669.7  681.25   698.7  698.71
   727.8  715.02   747.2  724.88   756.9  728.68   795.7  740.35   863.5  757.75
   882.9  761.19     941  766.49   960.4  766.33  1008.9  763.48  1028.3  763.35
#Mann= 3 , 0 , 0
       0     .05       0   547.3    .045       0   631.8      .1       0
Bank Sta=547.3,631.8
XS Rating Curve= 0 ,0
Exp/Cntr=0.3,0.1

Type RM Length L Ch R = 1 ,5538.3  ,389.8,385.3,380.5
XS GIS Cut Line= 3
     1867092.593      689289.219     1867529.189      689417.316
     1867965.785      689545.413
#Sta/Elev= 30
       0  743.96    96.8  717.42   154.9  699.08   193.6  687.97   203.3  686.61
   280.7  679.94   348.5  675.72   396.9  670.45   406.6  668.81   416.3  665.86
     426  663.49   445.3   662.7   464.7  662.71   474.4  663.49     484  666.23
   493.7  670.01   503.4  672.28   580.8  676.25   590.5  678.03   600.2  681.68
   648.6  705.99     668  714.33   687.3  719.26   764.8  736.38   774.5  737.37
   784.2  737.35   813.2   734.5   832.6  733.85   851.9  735.72     910  739.18
#Mann= 3 , 0 , 0
       0     .05       0   416.3    .045       0     484     .07       0
Bank Sta=416.3,484
XS Rating Curve= 0 ,0
Exp/Cntr=0.3,0.1

Type RM Length L Ch R = 1 ,5153    ,182.3,177.4,172.3
XS GIS Cut Line= 5
     1865815.733      689615.804     1866449.503      689675.779
     1867349.931       689777.97     1867519.677      689787.757
     1868007.483        689775.8
#Sta/Elev= 30
       0  821.09   166.5  815.57     235  798.35   274.2  783.94     284  782.77
   372.2   790.1   479.9  771.06   519.1  754.64   528.9  753.21   558.2   763.6
   587.6  770.06   704.8  777.92     773  776.44     851  770.12   880.2     764
   928.9  763.15  1016.6  747.46  1075.1  726.06  1240.7   677.6  1347.9  672.81
  1474.6   675.7  1533.1  671.29  1571.2  664.67  1599.5   662.7  1646.7  665.15
    1675  671.72  1751.9  674.21    1830  682.21  2005.6  726.14  2200.8  739.19
#Mann= 3 , 0 , 0
       0     .05       0  1571.2    .045       0  1646.7     .05       0
Bank Sta=1571.2,1646.7
XS Rating Curve= 0 ,0
Exp/Cntr=0.3,0.1

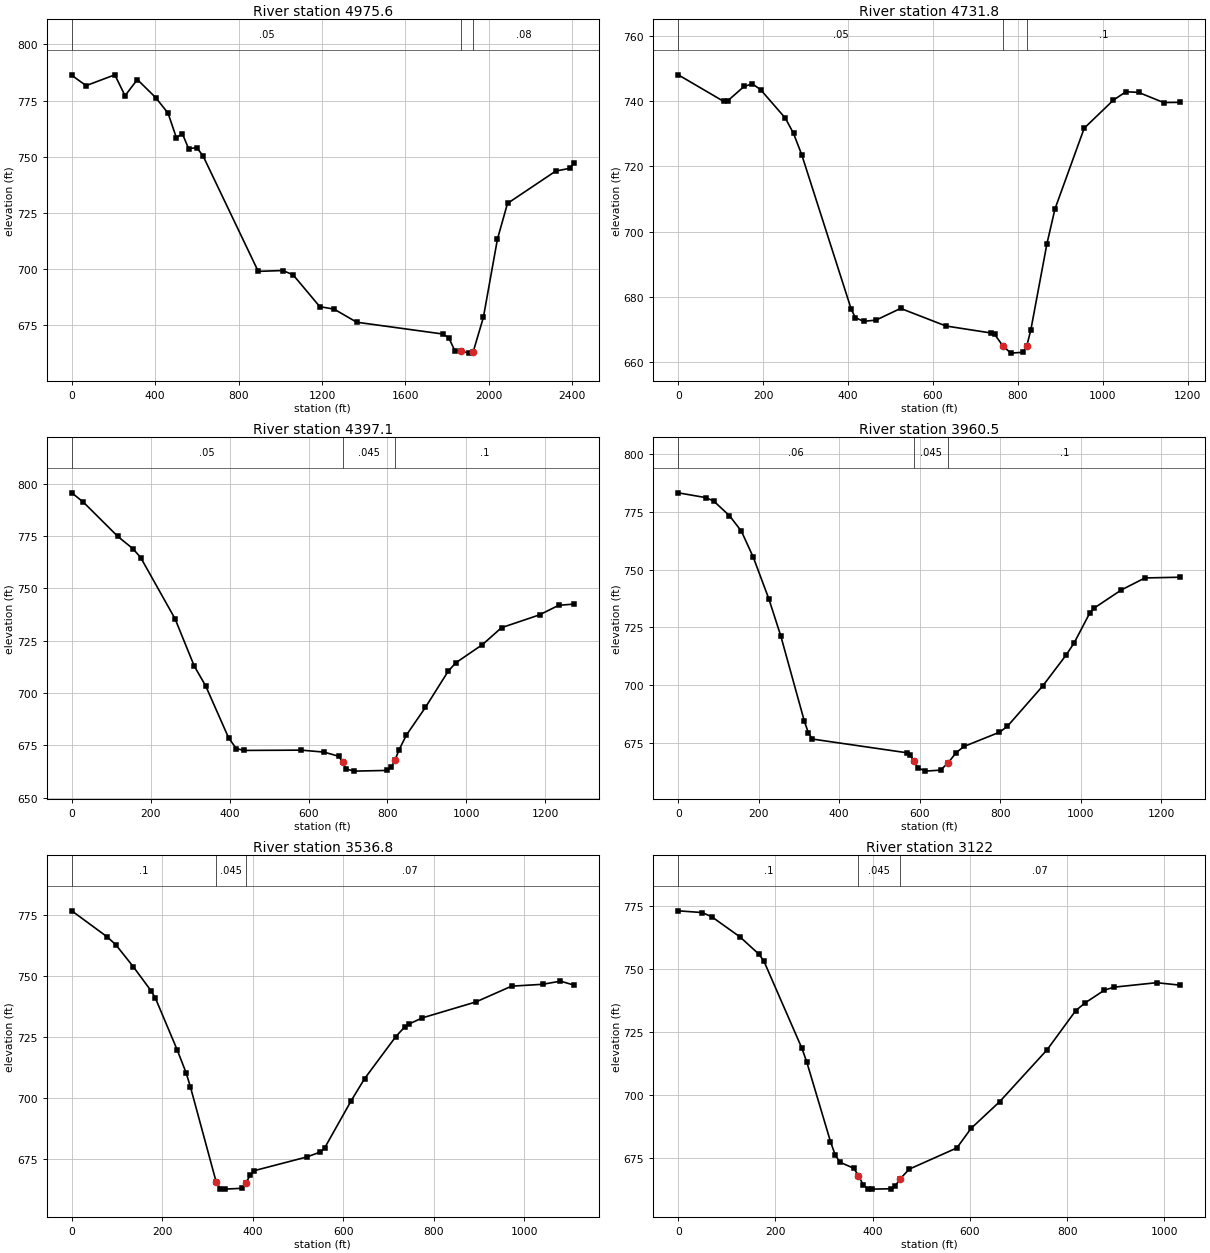
Type RM Length L Ch R = 1 ,4975.6  ,240.2,243.8,247.3
XS GIS Cut Line= 5
     1865685.524      690509.901     1866543.938      690118.687
     1867287.431      689973.716     1867567.379      689934.654
     1867986.216       689867.38
#Sta/Elev= 30
       0  786.27    68.8  781.68   206.4  786.49   255.5  777.18   314.4   784.4
   402.9  776.31   461.8  769.43   501.2  758.61   530.6  760.27   560.1  753.69
   599.4  754.08   628.9  750.54   894.2  699.07  1012.2  699.44  1061.4  697.53
  1189.3  683.38  1258.2  682.26  1366.4  676.45  1778.8  671.21  1808.1  669.55
  1837.3  663.68  1866.6  663.67  1905.5   662.7    1925  663.29  1973.8  678.57
  2041.4  713.45  2089.6   729.3    2321  743.68  2388.4  744.92  2407.7  747.09
#Mann= 3 , 0 , 0
       0     .05       0  1866.6    .045       0    1925     .08       0
Bank Sta=1866.6,1925
XS Rating Curve= 0 ,0
Exp/Cntr=0.3,0.1

Type RM Length L Ch R = 1 ,4731.8  ,339.5,334.7,329.6
XS GIS Cut Line= 4
     1866705.834      690236.303     1867382.917       690182.05
      1867591.25       690186.39     1867886.389       690195.07
#Sta/Elev= 30
       0  748.14   106.7  740.01   116.4  740.14   155.3  744.59   174.7  745.36
   194.1  743.58   252.3  734.85   271.7  730.13   291.1  723.55   407.6  676.17
   417.3  673.59   436.7  672.46   465.8  672.83     524  676.43   630.7  671.03
   736.1   668.9   745.6  668.43   764.5  664.98   783.4   662.7   811.9  662.96
   821.3  664.95   830.8  669.88   868.7  696.31   887.6  706.97   956.5  731.76
  1025.4   740.4    1055  742.95  1084.5  742.75  1143.5  739.63  1182.9  739.69
#Mann= 3 , 0 , 0
       0     .05       0   764.5    .045       0   821.3      .1       0
Bank Sta=764.5,821.3
XS Rating Curve= 0 ,0
Exp/Cntr=0.3,0.1

Type RM Length L Ch R = 1 ,4397.1  ,444.5,436.6,428.2
XS GIS Cut Line= 4
     1866729.705      690698.543     1867302.622      690516.251
     1867506.615      690475.018     1867951.493       690346.98
#Sta/Elev= 30
       0  795.68    29.1  791.27   116.4  774.89   155.2  768.93   174.6  764.76
   261.8  735.46   310.3  712.94   339.4  703.39   397.6  678.54     417  673.47
   436.4  672.59   581.8  672.73   639.1  671.79   676.9  669.79   686.4  666.85
   695.8  663.74   714.7   662.7   799.9  663.04   809.3  664.46     819  667.85
   828.6  672.58   847.9  679.91   896.1  693.13     954  710.47   973.3  714.48
  1040.8  723.17    1089  731.24  1185.5  737.38  1233.7  741.92  1272.3  742.52
#Mann= 3 , 0 , 0
       0     .05       0   686.4    .045       0     819      .1       0
Bank Sta=686.4,819
XS Rating Curve= 0 ,0
Exp/Cntr=0.3,0.1

Type RM Length L Ch R = 1 ,3960.5  ,442.5,423.6,405.5
XS GIS Cut Line= 4
     1867000.973       691273.63     1867443.335      690948.976
     1867539.167      690889.515     1867942.813      690464.168
#Sta/Elev= 30
       0  783.38    68.6   781.3    88.2   779.8   127.4  773.45   156.8   766.8
   186.2  755.59   225.4   737.3   254.8  721.36   313.6  684.27   323.4  679.33
   333.2  676.61   567.5  670.68   576.9   669.6   586.3  667.12   595.7  664.13
   614.5   662.7   652.1  663.14   671.3   666.4   690.8  670.72   710.4   673.4
   798.3  679.56   817.9  682.09   905.8   699.6   964.5  713.13     984   718.3
  1023.1  731.33  1032.9   733.3  1101.3  741.26  1159.9  746.47  1247.9  746.79
#Mann= 3 , 0 , 0
       0     .06       0   586.3    .045       0   671.3      .1       0
Bank Sta=586.3,671.3
XS Rating Curve= 0 ,0
Exp/Cntr=0.3,0.1

Type RM Length L Ch R = 1 ,3536.8  ,424.3,414.8,405.2
XS GIS Cut Line= 4
     1867636.823      691544.897     1867712.778       691273.63
      1867743.16       691117.38     1868003.577       690501.06
#Sta/Elev= 30
       0  776.79    77.7   766.2    97.1  762.94     136  753.89   174.8  744.12
   184.6  741.13   233.1  719.78   252.6  710.48   262.3  704.63   319.2  665.69
   328.5  662.95   337.9   662.7   375.3  663.03   384.7  665.12   394.1  668.35
   403.4  670.27   519.6  675.88   549.1  677.87     559  679.57     618  699.02
   647.5  708.02   716.4  725.23   736.1   729.2   745.9  730.42   775.4  732.93
   893.5  739.44   972.2   745.9  1041.1  746.67  1080.4  747.96    1110  746.36
#Mann= 3 , 0 , 0
       0      .1       0   319.2    .045       0   384.7     .07       0
Bank Sta=319.2,384.7
XS Rating Curve= 0 ,0
Exp/Cntr=0.3,0.1

Type RM Length L Ch R = 1 ,3122    ,408.6,399.2,389.5
XS GIS Cut Line= 4
     1868276.211      691524.234     1868153.316      691215.036
     1868120.873      691076.077     1868073.021      690520.591
#Sta/Elev= 30
       0  773.04    48.9  772.36    68.5  770.75   127.2  762.68   166.4  755.78
   176.2  753.12   254.4  718.56   264.2  713.26   313.2  681.58   322.9  676.26
   332.7  673.38   361.3  670.95   370.8  668.02   380.3   664.5   389.8   662.9
   399.3   662.7   437.4  662.84   446.9  664.06   456.4  666.75   475.4  670.63
   573.2  679.03   602.6   686.8   661.3  697.37   759.1  717.99   817.8  733.47
   837.3  736.56   876.5  741.55     896  742.76   984.1  744.55    1033  743.56
#Mann= 3 , 0 , 0
       0      .1       0   370.8    .045       0   456.4     .07       0
Bank Sta=370.8,456.4
XS Rating Curve= 0 ,0
Exp/Cntr=0.3,0.1

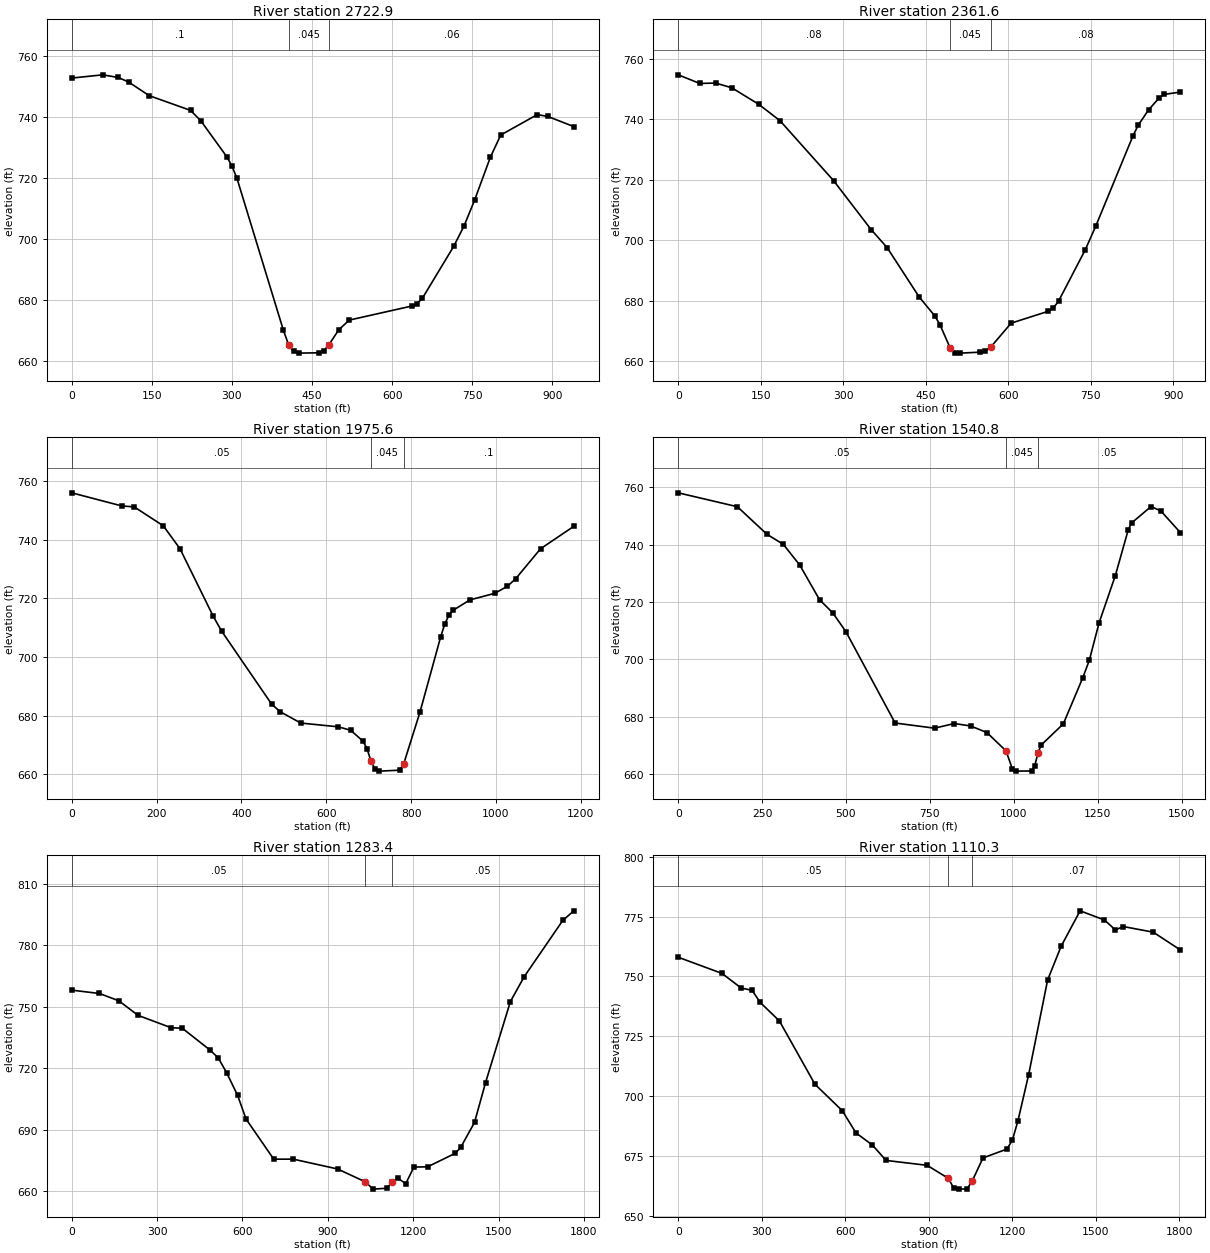
Type RM Length L Ch R = 1 ,2722.9  ,362,361.2,360.4
XS GIS Cut Line= 4
     1868773.695      691211.341     1868483.177      690941.598
     1868420.001      690859.238     1868177.188       690492.38
#Sta/Elev= 30
       0  752.92      58  753.98      87  753.11   106.4  751.62     145  747.15
   222.4  742.32   241.7   738.9   290.1  727.16   299.7  724.17   309.4     720
   396.4  670.13   405.9  665.52   415.3  663.26   424.8   662.7   462.5  662.81
   471.9  663.49   481.4  665.42   500.2  670.41   519.8  673.54   637.1  678.16
   646.9  678.94   656.7  680.73   715.3  697.75   734.9  704.54   754.4  712.91
   783.8  726.92   803.3  734.24   871.7  740.93   891.3  740.34   940.2     737
#Mann= 3 , 0 , 0
       0      .1       0   405.9    .045       0   481.4     .06       0
Bank Sta=405.9,481.4
XS Rating Curve= 0 ,0
Exp/Cntr=0.3,0.1

Type RM Length L Ch R = 1 ,2361.6  ,384.6,386.1,387.4
XS GIS Cut Line= 4
     1868903.551      691093.577     1868721.341      690673.682
     1868639.427      690574.845     1868441.945      690314.428
#Sta/Elev= 30
       0  754.79      39  751.94    68.2  752.06    97.4  750.49   146.1  745.06
     185   739.6   282.4  719.75   350.6  703.55   379.8  697.56   438.2  681.17
   466.9  674.84   476.1  671.92   494.4  664.31   503.6  662.76   512.7   662.6
   549.4  662.92   558.6   663.3   567.8  664.52   605.3  672.53   672.6  676.45
   682.2  677.55   691.8  679.92   739.9  696.77   759.1  704.64   826.4   734.4
     836  738.02   855.2  743.17   874.5  747.17   884.1  748.32   912.9  749.08
#Mann= 3 , 0 , 0
       0     .08       0   494.4    .045       0   567.8     .08       0
Bank Sta=494.4,567.8
XS Rating Curve= 0 ,0
Exp/Cntr=0.3,0.1

Type RM Length L Ch R = 1 ,1975.6  ,431.3,434.7,438.2
XS GIS Cut Line= 4
     1868974.852      691039.122     1868958.438      690381.702
     1868862.952      690249.324     1868624.236      689975.886
#Sta/Elev= 30
       0  756.03   117.8  751.56   147.2  751.23   215.9  744.77   255.2  736.95
   333.7  713.87   353.4  708.84   471.1  683.98   490.8  681.42   539.8   677.5
   628.2  676.22   657.6  675.04   686.4  671.35     696  668.81   705.6  664.48
   715.2  661.77   724.8   661.1   772.8  661.42   782.4  663.47   820.8  681.13
   869.9  706.96   879.7  711.38   889.5  714.35   899.3  715.97   938.6   719.5
   997.4  721.75  1026.9  724.14  1046.5   726.7  1105.3  736.95  1183.8  744.61
#Mann= 3 , 0 , 0
       0     .05       0   705.6    .045       0   782.4      .1       0
Bank Sta=705.6,782.4
XS Rating Curve= 0 ,0
Exp/Cntr=0.3,0.1

Type RM Length L Ch R = 1 ,1540.8  ,235.8,257.4,279
XS GIS Cut Line= 4
     1869040.331       690998.86     1869284.827      690131.558
     1869165.035      689904.995     1868987.952      689615.933
#Sta/Elev= 30
       0  758.02   176.3  753.18   264.4  743.58   313.4  740.06   362.4  732.82
   421.2  720.78   460.4  716.24   499.5  709.72   646.4  677.85     764  676.06
   822.8  677.68   871.7  676.82   920.1  674.52     977  668.14     996  661.81
  1005.5   661.1    1053  661.16  1062.5  662.95    1072  667.33  1081.4  670.14
  1147.9  677.59  1205.8  693.64  1225.2   699.7  1254.2  712.72  1302.7  729.17
  1341.4  745.23  1351.1  747.53  1409.2  753.24  1438.3  751.73  1496.4  744.19
#Mann= 3 , 0 , 0
       0     .05       0     977    .045       0    1072     .05       0
Bank Sta=977,1072
XS Rating Curve= 0 ,0
Exp/Cntr=0.3,0.1

Type RM Length L Ch R = 1 ,1283.4  ,164.9,173.1,181.3
XS GIS Cut Line= 5
     1869084.306       690983.12     1869258.785      690519.579
     1869417.639      690037.808     1869516.598      689842.495
     1869741.858      689348.065
#Sta/Elev= 30
       0  758.21    97.1  756.58   165.1  753.04   233.1   745.9   349.6  739.85
   388.5  739.63   485.6  729.01   514.8  725.17   544.1  717.96   583.1   706.8
   612.4  695.35   709.9  675.72   778.2  675.73   934.3  670.94  1031.1   664.7
  1059.7   661.1  1107.3  661.53  1126.3  664.54  1145.4  666.56  1173.9  663.73
  1202.5  671.87  1250.6  671.98  1347.7  678.56  1367.1  681.46  1415.6  693.65
  1454.4  713.06  1541.7  752.62  1590.2  764.76    1726  792.24  1764.8  796.92
#Mann= 3 , 0 , 0
       0     .05       0  1031.1    .045       0  1126.3     .05       0
Bank Sta=1031.1,1126.3
XS Rating Curve= 0 ,0
Exp/Cntr=0.3,0.1

Type RM Length L Ch R = 1 ,1110.3  ,319.6,344.2,368.8
XS GIS Cut Line= 4
     1869098.195      690982.614     1869495.764      690160.204
     1869678.643      689992.782     1870254.011      689708.308
#Sta/Elev= 30
       0  758.01   157.2  751.25   225.9  745.16   265.2  744.18   294.7   739.1
   363.4  731.38   491.1  704.91   589.3  693.87   638.4  684.59   697.4  679.52
   746.5  673.09   893.8  671.05   970.7  665.56   989.8  661.42  1008.8   661.1
  1037.4  661.18  1056.5  664.66  1094.6  674.14  1180.9  677.86  1200.3  681.64
  1219.8   689.5  1258.7     709  1326.7  748.51  1375.4  762.64  1443.4  777.41
    1531  773.57  1569.9  769.45    1599  770.83    1706  768.49  1803.3  761.08
#Mann= 3 , 0 , 0
       0     .05       0   970.7    .045       0  1056.5     .07       0
Bank Sta=970.7,1056.5
XS Rating Curve= 0 ,0
Exp/Cntr=0.3,0.1

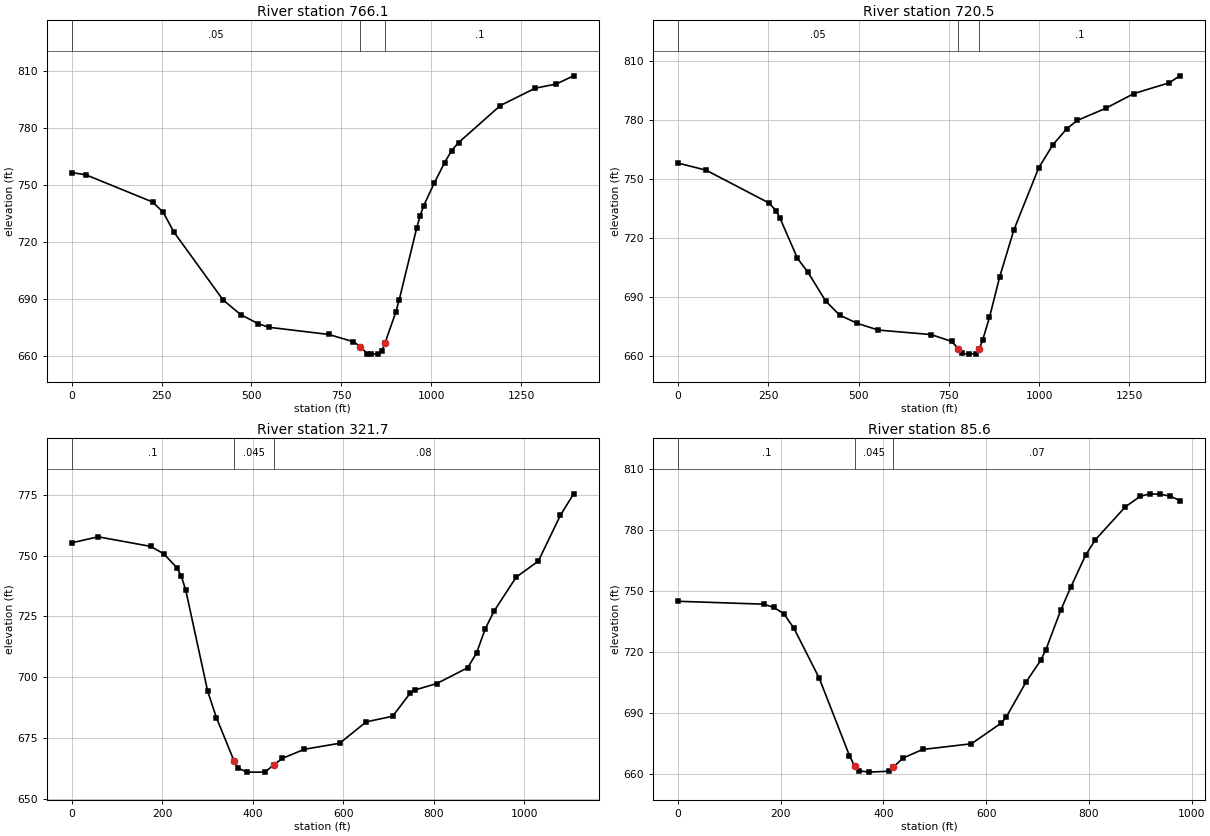
Type RM Length L Ch R = 1 ,766.1   ,46.5,45.6,44.7
XS GIS Cut Line= 4
     1869121.632      690975.669     1869481.875      690369.767
      1869676.32      690439.211     1870156.355       690509.09
#Sta/Elev= 30
       0  756.46    39.2  755.32   225.2  740.99   254.6  735.61   283.9  725.31
     421  689.58   469.9  681.86   518.9  677.09   548.3  675.21   714.7  671.45
   783.6  667.64   803.2  665.02   822.9  661.15   832.7   661.1   852.4  661.17
   862.2  662.54     872  667.13   901.6   683.1   911.4  689.78   959.9  727.36
   969.6  733.88   979.3  739.05  1008.4  750.83  1037.5  761.72  1056.9  767.99
  1076.3  772.21  1192.7  791.69  1289.8  800.82    1348  802.97  1396.5   807.3
#Mann= 3 , 0 , 0
       0     .05       0   803.2    .045       0     872      .1       0
Bank Sta=803.2,872
XS Rating Curve= 0 ,0
Exp/Cntr=0.3,0.1

Type RM Length L Ch R = 1 ,720.5   ,414.5,398.8,383
XS GIS Cut Line= 4
     1869130.313      691018.204     1869480.356      690422.356
     1869671.328      690482.035     1870165.035      690551.624
#Sta/Elev= 30
       0  758.26    77.9  754.64   253.1  737.85   272.5  733.76   282.3  730.33
   330.9  709.82   360.1   702.7   408.8  688.15   447.7  680.95   496.4  676.75
   554.8  673.33   700.6  671.06   757.8  667.58   776.8  663.79   786.3  661.46
   805.4   661.1   824.4  661.33     834  663.54   843.5  668.16   862.6  679.75
   891.1  700.53   930.2  724.27   998.7  755.72  1037.8  767.47  1076.9  775.76
  1106.2  779.98  1184.4   786.1  1262.6  793.61  1360.4  799.07  1389.7  802.62
#Mann= 3 , 0 , 0
       0     .05       0   776.8    .045       0     834      .1       0
Bank Sta=776.8,834
XS Rating Curve= 0 ,0
Exp/Cntr=0.3,0.1

Type RM Length L Ch R = 1 ,321.7   ,234,236.1,238.5
XS GIS Cut Line= 4
     1869175.452      691095.099     1869438.473      690865.933
     1869610.348      690798.224     1870172.848      690675.829
#Sta/Elev= 30
       0  755.22    58.1   757.7   174.4  753.76   203.5   750.7   232.6  744.96
   242.3  741.48     252  735.76   300.4  694.31   319.8  683.42   358.6  665.75
   368.3  662.69   387.7   661.1   426.6   661.1   446.1  663.98   465.5  666.75
   514.1  670.47   592.1  672.95   650.7  681.72   709.2  684.04   748.2  693.54
     758   694.8   806.8  697.46   875.1  703.95   894.6  709.96   914.1  720.02
   933.6  727.26   982.4  741.16  1031.2   747.7    1080  766.52  1109.2  775.34
#Mann= 3 , 0 , 0
       0      .1       0   358.6    .045       0   446.1     .08       0
Bank Sta=358.6,446.1
XS Rating Curve= 0 ,0
Exp/Cntr=0.3,0.1

Type RM Length L Ch R = 1 ,85.6    ,92.1,85.6,78.9
XS GIS Cut Line= 4
     1869237.952      691152.391     1869568.681      691058.641
     1869758.785      691001.349     1870185.868       690920.62
#Sta/Elev= 30
       0  745.02     167   743.6   186.6  741.98   206.3  738.84   225.9  731.71
     275  707.26   333.9  669.18   343.8  664.08   353.2  661.72   372.1   661.1
   409.9  661.54   419.4  663.62   438.3  668.03   476.1  672.22   571.3  675.03
   629.2  685.17   638.9  688.06   677.5   705.3   706.5   716.1   716.2  721.23
   745.1  740.57   764.5  751.82   793.4   767.6   812.8  775.31   870.7  791.33
   899.7  796.57     919   797.8   938.3  797.52   957.6  796.77     977  794.51
#Mann= 3 , 0 , 0
       0      .1       0   343.8    .045       0   419.4     .07       0
Bank Sta=343.8,419.4
XS Rating Curve= 0 ,0
Exp/Cntr=0.3,0.1

Chan Stop Cuts=-1
Use User Specified Reach Order=0
Composite Channel Slope=5